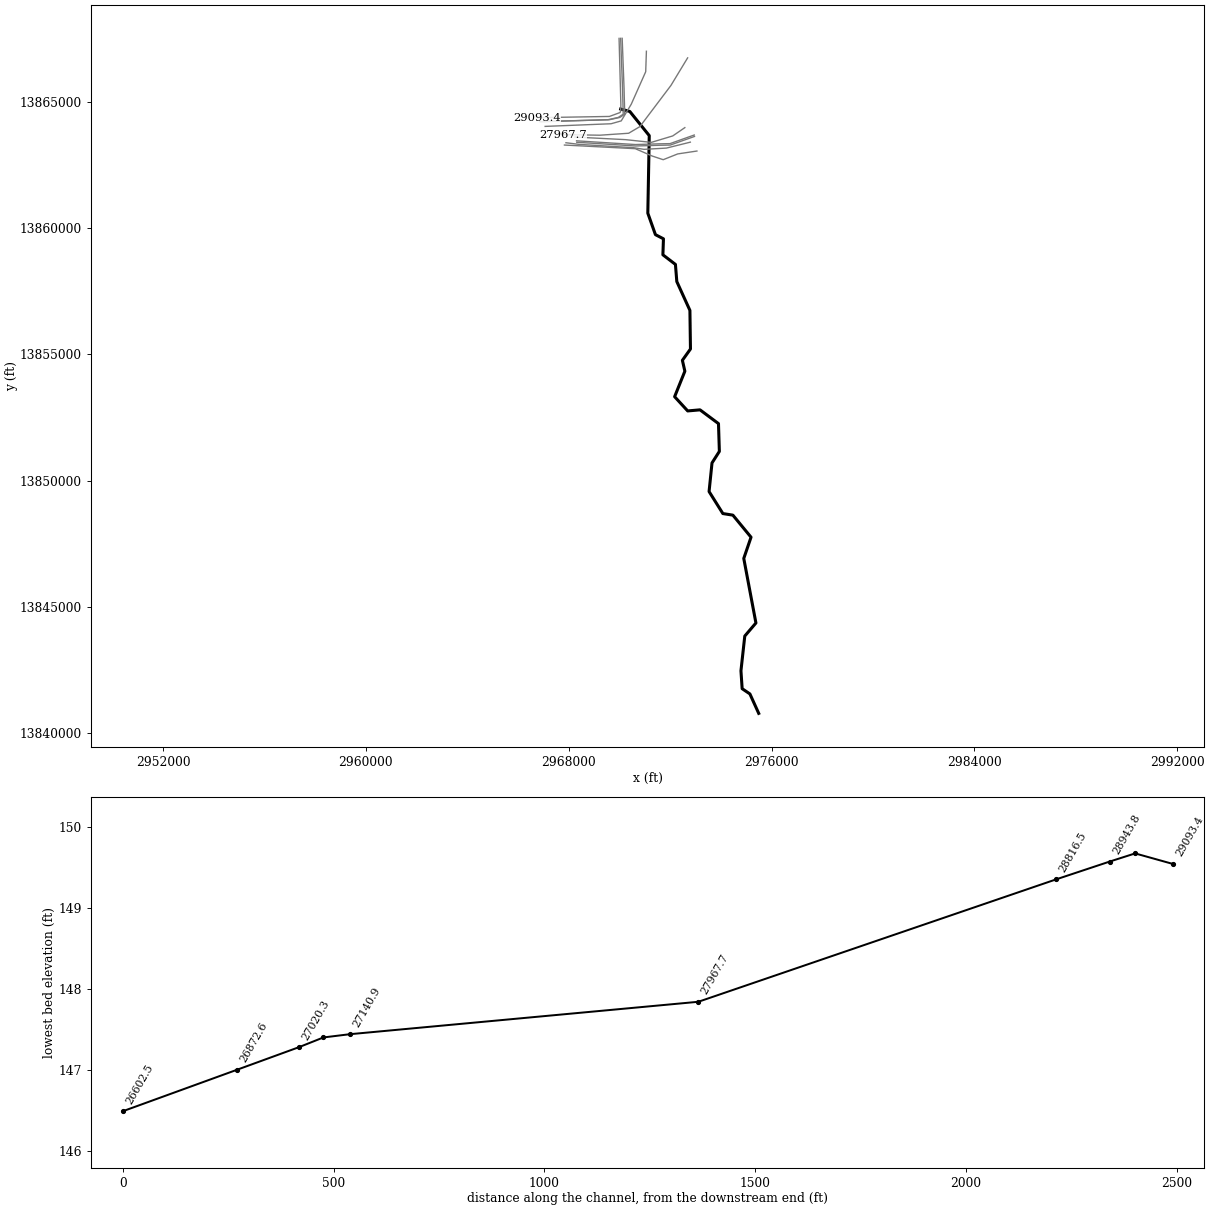
--- T100-00-00.PRJ (project) ---

Proj Title=T100-00-00
Current Plan=p01
Default Exp/Contr=.3,.1
English Units
Geom File=g01
Flow File=f02
Flow File=f01
Plan File=p02
Plan File=p01
Y Axis Title=Elevation
X Axis Title(PF)=Main Channel Distance
X Axis Title(XS)=Station
BEGIN DESCRIPTION:
Barker Reservoir Watershed
Cane Island Branch
HCFCD Unit T100-00-00
Flood Hazard Model
10, 2, 1, 0.2% Event
Filename T100-00-00.prj
Prepared by:  Watershed Concepts  Date:
Reviewed by:                      Date:
STATUS FINAL
END DESCRIPTION:
DSS Export Rating Curves= 0
DSS Export Rating Curve Sorted= 0
DSS Export Volume Flow Curves= 0
DXF OffsetX= 0
DXF OffsetY= 0
DXF ScaleX= 1
DXF ScaleY= 10

--- T100-00-00.p01 (plan) ---

Plan Title=FEMA Effective June 2007
Program Version=3.13
Short Identifier=FEMAeff0607
Geom File=g01
Flow File=f01
Subcritical Flow
K Sum by GR= 0
Std Step Tol= 0.01
Critical Tol= 0.01
Num of Std Step Trials= 20
Max Error Tol= 0.3
Flow Tol Ratio= 0.001
Split Flow NTrial= 30
Split Flow Tol= 0.02
Split Flow Ratio= 0.02
Log Output Level= 0
Friction Slope Method= 1
Unsteady Friction Slope Method= 2
Unsteady Bridges Friction Slope Method= 1
Parabolic Critical Depth
Global Vel Dist= 0 , 0 , 0
Global Log Level= 0
CheckData=True
Encroach Param=-1 ,0,0, 0
Computation Interval=1HOUR
Output Interval=1HOUR
Run HTab= 0
Run UNet= 0
Run PostProcess= 0
UNET Theta= 1
UNET Theta Warmup= 1
UNET ZTol= 0.02
UNET ZSATol= 0.05
UNET MxIter= 20
UNET MaxInSteps= 0
UNET DtIC= 0
UNET DtMin= 0
UNET MaxCRTS= 20
UNET WFStab= 2
UNET SFStab= 1
UNET WFX= 1
UNET SFX= 1
UNET DSS MLevel= 4
UNET DZMax Abort= 100
UNET Convert EG Bridges=-1
UNET Use Existing IB Tables=-1
UNET Froude Reduction=False
UNET Froude Limit= 1
UNET Froude Power= 10
Instantaneous Interval=1HOUR
Write IC File= 0
Echo Input=False
Echo Output=False
Write Detailed= 0
Detailed Automatic Start=False, 10

--- T100-00-00.p02 (plan) ---

Plan Title=Floodway
Version=Version 3.0.1  Mar 2001
Short Identifier=Floodway0607
Geom File=g01
Flow File=f02
Subcritical Flow
K Sum by GR= 0
Std Step Tol= 0.01
Critical Tol= 0.01
Num of Std Step Trials= 20
Max Error Tol= 0.3
Flow Tol Ratio= 0.001
Split Flow NTrial= 30
Split Flow Tol= 0.02
Split Flow Ratio= 0.02
Log Output Level= 0
Friction Slope Method= 1
Unsteady Friction Slope Method= 2
Parabolic Critical Depth
Global Vel Dist= 0 , 0 , 0
Global Log Level= 0
CheckData=True
Encroach Param=-1 ,0,0, 2
Encroach River=T100-00-00
Encroach Reach=Reach - 1
Encroach Node=29093.4
       1    4450    5300
Encroach Node=29003.8
       1    4450    5300
Encroach Node=28973.8
       1    4450    5300
Encroach Node=28943.8
       1    4450    5300
Encroach Node=28816.5
       1    4500    5335
Encroach Node=27967.7
       1    4650    5350
Encroach Node=27140.9
       1    4705    5310
Encroach Node=27078.3
       1    4700    5315
Encroach Node=27049.3
       1    4700    5315
Encroach Node=27020.3
       1    4700    5315
Encroach Node=26872.6
       1    4705    5380
Encroach Node=26602.5
       1    4720    5450
Encroach Node=26205.9
       1    4850    5500
Encroach Node=25326.9
       1    4810    5200
Encroach Node=24264.1
       1    4910    5160
Encroach Node=23183.4
       1    4815    5100
Encroach Node=22196.0
       1    4700    5200
Encroach Node=21175.8
       1    4670    5150
Encroach Node=21097.7
       1    4670    5150
Encroach Node=21068.2
       1    4670    5150
Encroach Node=21038.7
       1    4670    5150
Encroach Node=20771.1
       1    4800    5045
Encroach Node=20143.3
       1    4900    5100
Encroach Node=19118.4
       1    4915    5150
Encroach Node=18217.7
       1    4930    5175
Encroach Node=17776.0
       1    4955    5135
Encroach Node=16771.6
       1    4950    5150
Encroach Node=16357.5
       1    4740    5200
Encroach Node=16303.9
       1    4700    5200
Encroach Node=16288.9
       1    4700    5200
Encroach Node=16273.9
       1    4700    5200
Encroach Node=16032.5
       1    4700    5200
Encroach Node=15766.5
       1    4740    5160
Encroach Node=15154.9
       1    4740    5050
Encroach Node=15108.5
       1    4820    5080
Encroach Node=15093.5
       1    4820    5080
Encroach Node=15078.5
       1    4820    5080
Encroach Node=14688.6
       1    4800    5100
Encroach Node=14162.4
       1    4800    5100
Encroach Node=13743.1
       1    4845    5305
Encroach Node=13714.1
       1    4845    5305
Encroach Node=13685.1
       1    4845    5305
Encroach Node=13458.2
       1    4780    5225
Encroach Node=12591.2
       1    4780    5250
Encroach Node=11622.2
       1    4770    5200
Encroach Node=11568.9
       1    4795    5200
Encroach Node=11542.4
       1    4795    5200
Encroach Node=11515.9
       1    4795    5200
Encroach Node=11303.6
       1    4870    5200
Encroach Node=10517.0
       1    4930    5060
Encroach Node=9516.0
       1    4870  5052.4
Encroach Node=8507.4
       1  4971.3  5038.7
Encroach Node=7600.4
       1    4845    5105
Encroach Node=7550.7
       1    4840    5110
Encroach Node=7523.2
       1    4840    5110
Encroach Node=7495.7
       1    4840    5110
Encroach Node=7424.9
       1    4935    5064
Encroach Node=7408.4
       1    4935    5064
Encroach Node=7391.9
       1    4935    5064
Encroach Node=7348.0
       1    4930    5070
Encroach Node=7301.5
       1    4930    5070
Encroach Node=7255.0
       1    4930    5070
Encroach Node=6777.2
       1    4845    5090
Encroach Node=5961.2
       1    4900    5200
Encroach Node=5085.1
       1    4958    5250
Encroach Node=4820.4
       1    4972    5250
Encroach Node=4771.6
       1    4950    5250
Encroach Node=4746.1
       1    4950    5250
Encroach Node=4720.6
       1    4950    5250
Encroach Node=4258.4
       1  4910.6    5068
Encroach Node=4117.6
       1  4921.8  5061.4
Encroach Node=3975.1
       1  4921.8  5061.4
Encroach Node=3832.6
       1  4921.8  5061.4
Encroach Node=3345.4
       1    4775    5225
Encroach Node=2882.8
       1    4775    5225
Encroach Node=2518.6
       1    4775    5225
Encroach Node=1593.6
       1    4750    5250
Encroach Node=449.4
       1    4845    5155
Encroach Reach=T100-00-00_0004
Encroach Node=29093.4
       1    4450    5300
Encroach Node=29003.8
       1    4450    5300
Encroach Node=28973.8
       1    4450    5300
Encroach Node=28943.8
       1    4450    5300
Encroach Node=28816.5
       1    4500    5335
Encroach Node=27967.7
       1    4650    5350
Encroach Node=27140.9
       1    4705    5310
Encroach Node=27078.3
       1    4700    5315
Encroach Node=27049.3
       1    4700    5315
Encroach Node=27020.3
       1    4700    5315
Encroach Node=26872.6
       1    4705    5380
Encroach Node=26602.5
       1    4720    5450
Encroach Node=26205.9
       1    4850    5500
Encroach Node=25326.9
       1    4810    5200
Encroach Node=24264.1
       1    4910    5160
Encroach Node=23183.4
       1    4815    5100
Encroach Node=22196.0
       1    4700    5200
Encroach Node=21175.8
       1    4670    5150
Encroach Node=21097.7
       1    4670    5150
Encroach Node=21068.2
       1    4670    5150
Encroach Node=21038.7
       1    4670    5150
Encroach Node=20771.1
       1    4800    5045
Encroach Node=20143.3
       1    4900    5100
Encroach Node=19118.4
       1    4915    5150
Encroach Node=18217.7
       1    4930    5175
Encroach Node=17776.0
       1    4955    5135
Encroach Node=16771.6
       1    4950    5150
Encroach Node=16357.5
       1    4740    5200
Encroach Node=16303.9
       1    4700    5200
Encroach Node=16288.9
       1    4700    5200
Encroach Node=16273.9
       1    4700    5200
Encroach Node=16032.5
       1    4700    5200
Encroach Node=15766.5
       1    4740    5160
Encroach Node=15154.9
       1    4740    5050
Encroach Node=15108.5
       1    4820    5080
Encroach Node=15093.5
       1    4820    5080
Encroach Node=15078.5
       1    4820    5080
Encroach Node=14688.6
       1    4800    5100
Encroach Node=14162.4
       1    4800    5100
Encroach Node=13743.1
       1    4845    5305
Encroach Node=13714.1
       1    4845    5305
Encroach Node=13685.1
       1    4845    5305
Encroach Node=13458.2
       1    4780    5225
Encroach Node=12591.2
       1    4780    5250
Encroach Node=11622.2
       1    4770    5200
Encroach Node=11568.9
       1    4795    5200
Encroach Node=11542.4
       1    4795    5200
Encroach Node=11515.9
       1    4795    5200
Encroach Node=11303.6
       1    4870    5200
Encroach Node=10517.0
       1    4930    5060
Encroach Node=9516.0
       1    4870  5052.4
Encroach Node=8507.4
       1  4971.3  5038.7
Encroach Node=7600.4
       1    4845    5105
Encroach Node=7550.7
       1    4840    5110
Encroach Node=7523.2
       1    4840    5110
Encroach Node=7495.7
       1    4840    5110
Encroach Node=7424.9
       1    4935    5064
Encroach Node=7408.4
       1    4935    5064
Encroach Node=7391.9
       1    4935    5064
Encroach Node=7348.0
       1    4930    5070
Encroach Node=7301.5
       1    4930    5070
Encroach Node=7255.0
       1    4930    5070
Encroach Node=6777.2
       1    4845    5090
Encroach Node=5961.2
       1    4900    5200
Encroach Node=5085.1
       1    4958    5250
Encroach Node=4820.4
       1    4972    5250
Encroach Node=4771.6
       1    4950    5250
Encroach Node=4746.1
       1    4950    5250
Encroach Node=4720.6
       1    4950    5250
Encroach Node=4258.4
       1  4910.6    5068
Encroach Node=4117.6
       1  4921.8  5061.4
Encroach Node=3975.1
       1  4921.8  5061.4
Encroach Node=3832.6
       1  4921.8  5061.4
Encroach Node=3345.4
       1    4775    5225
Encroach Node=2882.8
       1    4775    5225
Encroach Node=2518.6
       1    4775    5225
Encroach Node=1593.6
       1    4750    5250
Encroach Node=449.4
       1    4845    5155
Computation Interval=1HOUR
Output Interval=1HOUR
Run HTab= 0
Run UNet= 0
Run PostProcess= 0
UNET Theta= 1
UNET ZTol= 0.02
UNET ZSATol= 0.1
UNET MxIter= 20
UNET MaxInSteps= 20
UNET DtIC= 0
UNET DtMin= 0
UNET MaxCRTS= 20
UNET WFStab= 2
UNET SFStab= 1
UNET WFX= 1
UNET SFX= 1
UNET Convert EG Bridges=-1
UNET Use Existing IB Tables=-1
Instantaneous Interval=1HOUR
DSS File=dss
Write IC File= 0
IC Time=0
Write Velocity= 0
Write Detailed= 0

--- T100-00-00.f01 (steady flow) ---

Flow Title=FEMA Effective June 2007
Program Version=3.13
Number of Profiles= 4
Profile Names=10PCT_10yr,2PCT_50yr,1PCT_100yr,0.2PCT_500yr
River Rch & RM=T100-00-00,T100-00-00_0004 ,29093.4
     890    2171    3034    5764
River Rch & RM=T100-00-00,T100-00-00_0004 ,27967.7
     897    2184    3049    5795
River Rch & RM=T100-00-00,T100-00-00_0004 ,27078.3
     904    2196    3063    5826
River Rch & RM=T100-00-00,T100-00-00_0004 ,26205.9
     910    2206    3076    5852
River Rch & RM=T100-00-00,T100-00-00_0004 ,25326.9
     916    2217    3089    5880
River Rch & RM=T100-00-00,T100-00-00_0004 ,24264.1
     924    2230    3105    5914
River Rch & RM=T100-00-00,T100-00-00_0004 ,23183.4
     931    2244    3121    5948
River Rch & RM=T100-00-00,T100-00-00_0004 ,22196
     939    2257    3136    5980
River Rch & RM=T100-00-00,T100-00-00_0004 ,21097.7
     947    2271    3154    6017
River Rch & RM=T100-00-00,T100-00-00_0004 ,20143.3
     953    2283    3168    6046
River Rch & RM=T100-00-00,T100-00-00_0004 ,19118.4
     961    2296    3183    6078
River Rch & RM=T100-00-00,T100-00-00_0004 ,14688.6
     993    2352    3250    6220
River Rch & RM=T100-00-00,T100-00-00_0004 ,13743.1
     999    2364    3265    6250
River Rch & RM=T100-00-00,T100-00-00_0004 ,12591.2
    1015    2380    3285    6279
River Rch & RM=T100-00-00,T100-00-00_0004 ,11568.9
    1030    2395    3304    6306
River Rch & RM=T100-00-00,T100-00-00_0004 ,10517
    1045    2411    3325    6335
River Rch & RM=T100-00-00,T100-00-00_0004 ,9516
    1057    2423    3340    6357
River Rch & RM=T100-00-00,T100-00-00_0004 ,8507.4
    1071    2437    3358    6382
River Rch & RM=T100-00-00,T100-00-00_0004 ,7348
    1230    2458    3383    6420
Boundary for River Rch & Prof#=T100-00-00,T100-00-00_0004 , 1
Up Type= 0
Dn Type= 3
Dn Slope=0.0012
Boundary for River Rch & Prof#=T100-00-00,T100-00-00_0004 , 2
Up Type= 0
Dn Type= 3
Dn Slope=0.0012
Boundary for River Rch & Prof#=T100-00-00,T100-00-00_0004 , 3
Up Type= 0
Dn Type= 3
Dn Slope=0.0012
Boundary for River Rch & Prof#=T100-00-00,T100-00-00_0004 , 4
Up Type= 0
Dn Type= 3
Dn Slope=0.0012
DSS Import GetInterval= 0
DSS Import GetPeak= 0
DSS Import FillOption= 0

--- T100-00-00.f02 (steady flow) ---

Flow Title= Floodway
Program Version=3.13
Number of Profiles= 2
Profile Names=1PCT_100yr,1PCTFloodway_100yrFW
River Rch & RM=T100-00-00,T100-00-00_0004 ,29093.4
    3034    3034
River Rch & RM=T100-00-00,T100-00-00_0004 ,27967.7
    3049    3049
River Rch & RM=T100-00-00,T100-00-00_0004 ,27078.3
    3063    3063
River Rch & RM=T100-00-00,T100-00-00_0004 ,26205.9
    3076    3076
River Rch & RM=T100-00-00,T100-00-00_0004 ,25326.9
    3089    3089
River Rch & RM=T100-00-00,T100-00-00_0004 ,24264.1
    3105    3105
River Rch & RM=T100-00-00,T100-00-00_0004 ,23183.4
    3121    3121
River Rch & RM=T100-00-00,T100-00-00_0004 ,22196
    3136    3136
River Rch & RM=T100-00-00,T100-00-00_0004 ,21097.7
    3154    3154
River Rch & RM=T100-00-00,T100-00-00_0004 ,20143.3
    3168    3168
River Rch & RM=T100-00-00,T100-00-00_0004 ,19118.4
    3183    3183
River Rch & RM=T100-00-00,T100-00-00_0004 ,14688.6
    3250    3250
River Rch & RM=T100-00-00,T100-00-00_0004 ,13743.1
    3265    3265
River Rch & RM=T100-00-00,T100-00-00_0004 ,12591.2
    3285    3285
River Rch & RM=T100-00-00,T100-00-00_0004 ,11568.9
    3304    3304
River Rch & RM=T100-00-00,T100-00-00_0004 ,10517
    3325    3325
River Rch & RM=T100-00-00,T100-00-00_0004 ,9516
    3340    3340
River Rch & RM=T100-00-00,T100-00-00_0004 ,8507.4
    3358    3358
River Rch & RM=T100-00-00,T100-00-00_0004 ,7348
    3383    3383
Boundary for River Rch & Prof#=T100-00-00,T100-00-00_0004 , 1
Up Type= 0
Dn Type= 3
Dn Slope=0.0012
Boundary for River Rch & Prof#=T100-00-00,T100-00-00_0004 , 2
Up Type= 0
Dn Type= 3
Dn Slope=0.0012
DSS Import GetInterval= 0
DSS Import GetPeak= 0
DSS Import FillOption= 0

--- T100-00-00.g01 (geometry) ---

Geom Title=T100-00-00 June 2007
Program Version=3.13

River Reach=T100-00-00      ,T100-00-00_0004
Reach XY= 30
      2970049.92     13864724.45       2970409.5       13864628.
      2971176.25       13863672.      2971119.75       13860598.
      2971420.08     13859747.63       2971736.5       13859583.
      2971714.59     13858949.22      2972209.04     13858568.25
       2972263.5       13857889.      2972780.25       13856747.
        2972802.       13855218.       2972483.5       13854769.
        2972581.       13854337.      2972176.98     13853327.66
      2972692.25       13852764.        2973179.       13852807.
      2973907.25       13852261.        2973942.       13851160.
        2973652.       13850704.        2973536.       13849570.
        2974080.       13848698.       2974475.5       13848635.
        2975191.       13847761.      2974904.75       13846920.
      2975384.25       13844363.       2974944.5       13843845.
      2974793.45     13842468.72       2974840.9      13841759.6
      2975146.38     13841552.86      2975494.44      13840781.7

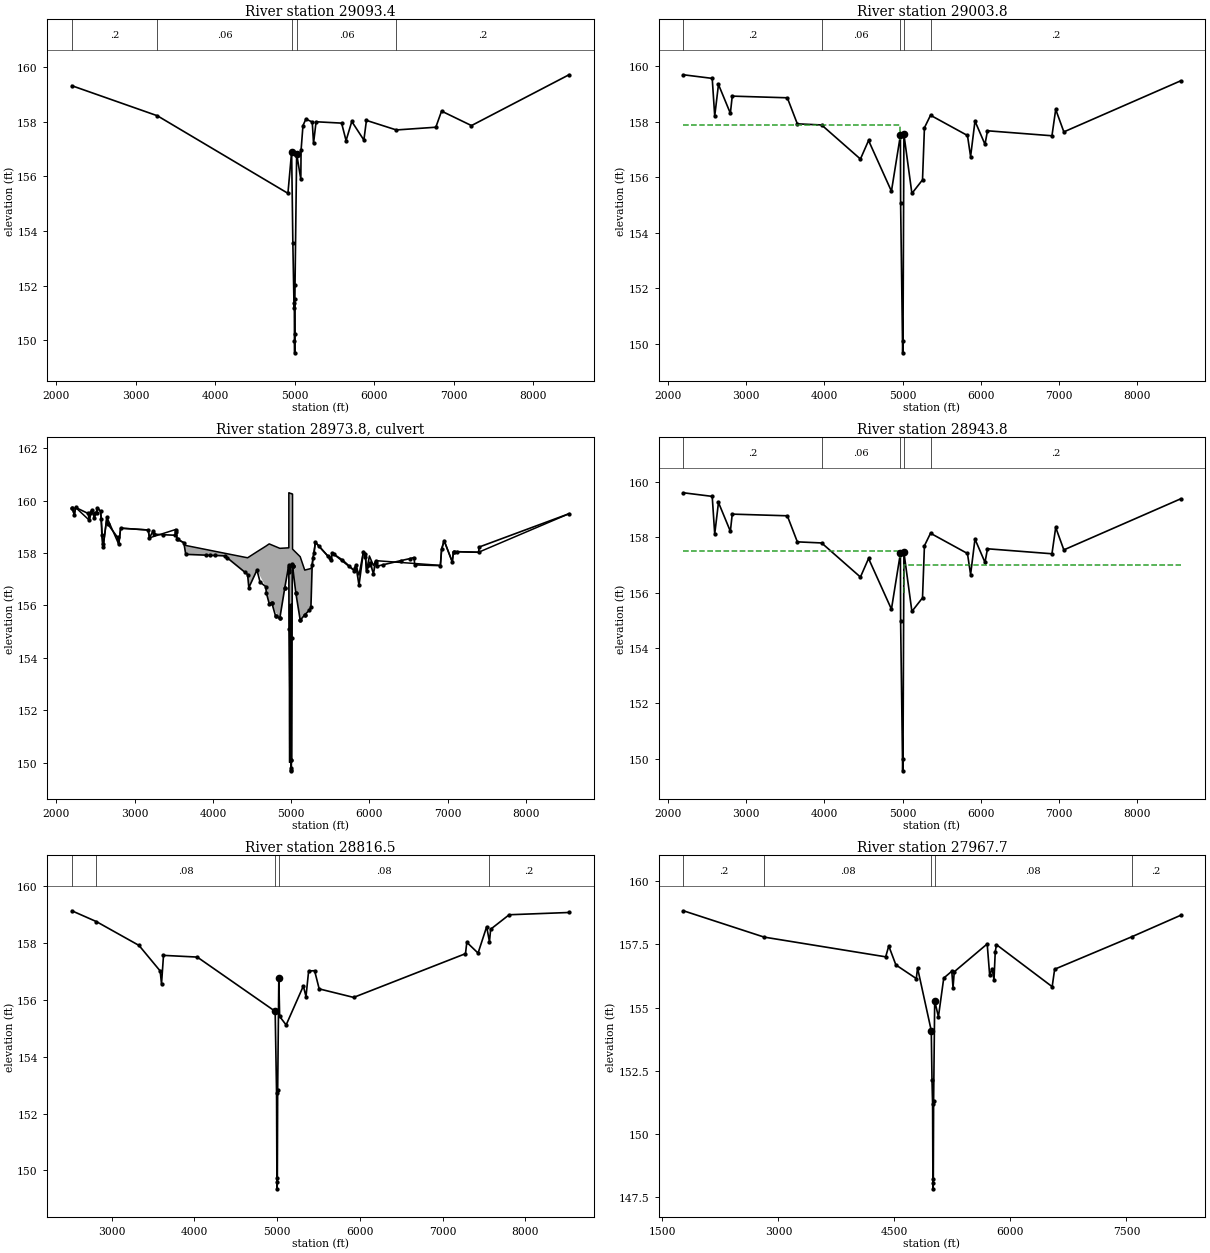
Type RM Length L Ch R = 1 ,29093.4 ,46.6,89.6,148.3
BEGIN DESCRIPTION:
Cross Section 29093.4
END DESCRIPTION:
XS GIS Cut Line= 6
      2969985.67     13867523.68      2970056.62     13864882.71
      2970046.51     13864643.42      2970026.29     13864586.12
        2969605.     13864431.09      2966747.54     13864381.75
#Sta/Elev= 30
  2199.7  159.32  3274.5  158.22  4916.1  155.38  4962.6   156.9    4978  153.56
    4993  151.18  4996.6  151.35  4998.4  149.99  5000.6  149.54  5002.9  150.24
  5003.5   151.5  5005.2  152.01  5025.7  156.83  5078.2  155.89  5081.1  156.95
  5105.1  157.86  5141.9   158.1  5221.9  157.99  5237.9  157.21  5269.9     158
  5590.8  157.95  5646.8  157.31  5718.8  158.01  5870.8  157.33  5902.8  158.05
  6279.3   157.7  6775.2   157.8  6847.2  158.39  7223.2  157.86  8448.8  159.72
#Mann= 5 , 1 , 0
  2199.7      .2       0  3274.5     .06       0  4962.6    .048       0
  5025.7     .06       0  6279.3      .2       0
Bank Sta=4962.6,5025.7
Exp/Cntr=0.5,0.3

Type RM Length L Ch R = 1 ,29003.8 ,60,60,60
BEGIN DESCRIPTION:
Upstream Section of Bridge/Culvert/Weir
END DESCRIPTION:
XS GIS Cut Line= 6
       2970048.3     13867525.44        2970122.     13865551.25
      2970149.14     13864519.36      2969954.55     13864391.91
      2969546.28     13864301.18      2966851.37     13864223.62
#Sta/Elev= 30
  2197.1   159.7  2565.1  159.57  2597.1  158.21  2645.1  159.35  2797.1  158.31
  2821.1  158.93  3525.1  158.87  3653.1  157.93  3963.7  157.89  4459.6  156.66
  4563.6  157.33    4856   155.5  4970.7  157.52  4973.4  155.07  4999.5  149.67
  5003.9   150.1  5015.6  157.55  5117.6  155.42  5253.3  155.91  5277.9  157.79
  5355.7  158.24  5827.9  157.51  5867.9  156.75  5923.9  158.03  6051.9  157.19
  6083.9  157.68  6907.9   157.5  6955.9  158.45  7059.9  157.64  8551.8  159.48
#Mann= 5 , 1 , 0
  2197.1      .2       0  3963.7     .06       0  4970.7    .048       0
  5015.6     .06       0  5355.7      .2       0
#XS Ineff= 2 , 0
       0    4960   157.9  5013.3       0  155.95
Permanent Ineff=
       F       F
Bank Sta=4970.7,5015.6
Exp/Cntr=0.5,0.3

Type RM Length L Ch R = 2 ,28973.8 ,,,
BEGIN DESCRIPTION:
PITTS ROAD
Structure ID: T00-14
END DESCRIPTION:
Bridge Culvert--1,0,-1,-1, 0
Deck Dist Width WeirC Skew NumUp NumDn MinLoCord MaxHiCord MaxSubmerge Is_Ogee
10,40,3,0, 60, 60, , , 0.95, 0, 1,1,,
  2197.1  2229.1  2245.1  2421.1  2453.1  2485.1  2525.1  2565.1  2597.1  2645.1
  2797.1  2821.1  3173.1  3189.1  3525.1  3541.1  3629.1  3653.1  4155.6  4443.6
  4459.6  4563.6  4675.6  4719.9    4856  4970.7 4970.79  4970.9  4973.4  4997.4
  4999.5  5003.1  5003.9  5011.6  5015.6  5018.3 5018.41  5116.2  5174.2  5253.3
  5269.2  5309.9  5509.9  5525.9  5807.6  5827.9  5867.9  5923.9  5947.9  5963.9
  6000.8  6051.9  6083.9  6907.9  6923.9  6955.9  7059.9  7075.9  7395.9  8551.8
  159.72  159.46  159.74  159.25  159.65  159.34  159.72  159.59  158.23  159.37
  158.33  158.95  158.88  158.58   158.9  158.54   158.4  158.29  157.99  157.82
  157.85  158.05  158.26  158.35  158.18   158.2   158.2   160.3   160.3  160.27
  160.27  160.27  160.27  160.26  160.25  160.25  158.15  157.86  157.35  157.41
  157.54  158.42  157.76     158  157.33  157.54  157.16  158.06  157.98  157.33
  157.89  157.53  157.71  157.53  158.15  158.48  157.67  158.06  158.03   159.5
  159.72  159.46  159.74  159.25  159.65  159.34  159.72  159.59  158.23  159.37
  158.33  158.95  158.88  158.58  158.89  158.53  158.39  157.95  157.89  157.18
  156.68  157.35  156.72  156.07  155.52  157.54  157.46  157.36  155.09  149.71
  149.69   149.8  150.12  154.75  157.57   157.5   157.5  155.44  155.64  155.93
  157.53  158.41  157.75  157.99  157.33  157.53  156.77  158.05  157.97  157.32
  157.54  157.21   157.7  157.52  158.14  158.47  157.66  158.05  158.03   159.5
  2197.1  2229.1  2245.1  2421.1  2453.1  2485.1  2525.1  2565.1  2597.1  2645.1
  2797.1  2821.1  3173.1  3189.1  3525.1  3541.1  3629.1  3653.1  4155.6  4443.6
  4459.6  4563.6  4675.6  4719.9    4856  4970.7 4970.79  4970.9  4973.4  4997.4
  4999.5  5003.1  5003.9  5011.6  5015.6  5018.3 5018.41  5116.2  5174.2  5253.3
  5269.2  5309.9  5509.9  5525.9  5807.6  5827.9  5867.9  5923.9  5947.9  5963.9
  6000.8  6051.9  6083.9  6907.9  6923.9  6955.9  7059.9  7075.9  7395.9  8551.8
  159.72  159.46  159.74  159.25  159.65  159.34  159.72  159.59  158.23  159.37
  158.33  158.95  158.88  158.58   158.9  158.54   158.4  158.29  157.99  157.82
  157.85  158.05  158.26  158.35  158.18   158.2   158.2   160.3   160.3  160.27
  160.27  160.27  160.27  160.26  160.25  160.25  158.15  157.86  157.35  157.41
  157.54  158.42  157.76     158  157.33  157.54  157.16  158.06  157.98  157.33
  157.89  157.53  157.71  157.53  158.15  158.48  157.67  158.06  158.03   159.5
  159.62  159.36  159.64  159.15  159.55  159.24  159.62  159.49  158.13  159.27
  158.23  158.85  158.78  158.48  158.79  158.43  158.29  157.85  157.79  157.08
  156.58  157.25  156.62  155.97  155.42  157.44  157.36  157.26  154.99  149.61
  149.59   149.7  150.02  154.65  157.47   157.4   157.4  155.34  155.54  155.83
  157.43  158.31  157.65  157.89  157.23  157.43  156.67  157.95  157.87  157.22
  157.44  157.11   157.6  157.42  158.04  158.37  157.56  157.95  157.93   159.4
BR Coef= 1 , 0 , 0 ,1.25, 0 ,,,0.8,-1,2,0,
WSPro=,,,, 1 ,,,, 0 ,,,, 0 ,,,,-1 ,-1 ,-1 , 0 , 0 , 0 , 0 , 0
Culvert=1,6,,40,0.015,0.2,1,1,3,150,4980.2,149.57,4980.2,Culvert #1  , 0 ,10
Culvert Bottom n=0.015
Culvert=1,6,,40,0.015,0.2,1,1,3,150.06,4987.9,149.87,4987.9,Culvert #2  , 0 ,10
Culvert Bottom n=0.015
Culvert=1,6,,40,0.015,0.2,1,1,3,150.05,4997.6,149.75,4997.6,Culvert #3  , 0 ,10
Culvert Bottom n=0.015
Culvert=1,6,,40,0.015,0.2,1,1,3,150.08,5005.9,149.52,5005.9,Culvert #4  , 0 ,10
Culvert Bottom n=0.015
BR U #Sta/Elev= 119
  2197.1  159.72  2205.1  159.71  2229.1  159.46  2245.1  159.74  2405.1  159.51
  2421.1  159.25  2429.1  159.52  2453.1  159.65  2485.1  159.34  2493.1  159.51
  2517.1  159.51  2525.1  159.72  2565.1  159.59  2573.1  159.29  2581.1  158.68
  2589.1  158.35  2597.1  158.23  2645.1  159.37  2661.1  159.09  2781.1   158.6
  2797.1  158.33  2821.1  158.95  3173.1  158.88  3189.1  158.58  3237.1  158.85
  3245.1  158.72  3356.6   158.7  3517.1  158.68  3525.1  158.89  3533.1   158.8
  3541.1  158.53  3548.9  158.52  3629.1  158.39  3653.1  157.95  3908.9  157.92
  3963.7  157.91  4028.9  157.91  4155.6  157.89  4182.7  157.82  4412.7  157.26
  4443.6  157.18  4459.6  156.68  4563.6  157.35  4603.6  156.89  4675.6  156.72
  4683.6  156.48  4719.9  156.07  4751.9  156.11  4752.1  156.11  4802.8  155.58
  4803.7  155.58    4856  155.52  4856.1  155.52  4919.1  156.67  4919.4  156.68
  4970.7  157.54 4970.79  157.46  4970.9  157.36 4971.01  157.26  4973.4  155.09
    4996  150.09  4997.4  149.71  4999.5  149.69  5003.1   149.8  5003.9  150.12
  5011.6  154.75  5015.6  157.57 5018.19  157.51  5018.3   157.5 5018.41   157.5
  5059.8  156.49  5060.4  156.48  5116.2  155.44  5117.6  155.44  5174.2  155.64
    5175  155.64  5228.4  155.81  5253.3  155.93  5269.2  157.53  5277.9  157.81
  5293.9     158  5309.9  158.41  5355.7  158.26  5473.3  157.87  5493.3   157.8
  5509.9  157.75  5525.9  157.99  5543.3  157.96  5655.6  157.74  5740.8  157.51
  5807.6  157.33  5811.9  157.42  5827.9  157.53  5867.9  156.77  5923.9  158.05
  5947.9  157.97  5950.8  157.85  5963.9  157.32  6000.8  157.54  6011.9  157.61
  6051.9  157.21  6083.9   157.7  6090.8  157.61  6099.9   157.5  6170.8  157.55
  6401.6  157.71  6521.6  157.79  6571.9  157.83  6579.9  157.55  6907.9  157.52
  6923.9  158.14  6955.9  158.47  7059.9  157.66  7075.9  158.05  7081.6  158.05
  7121.6  158.05  7395.9  158.03  7403.9  158.23  8551.8   159.5
BR U #Mann= 5
  2197.1      .2  3963.7     .06  4970.7    .048  5015.6     .06  5355.7      .2
BR U Banks=4970.7,5015.6
BR D #Sta/Elev= 119
  2197.1  159.62  2205.1  159.61  2229.1  159.36  2245.1  159.64  2405.1  159.41
  2421.1  159.15  2429.1  159.42  2453.1  159.55  2485.1  159.24  2493.1  159.41
  2517.1  159.41  2525.1  159.62  2565.1  159.49  2573.1  159.19  2581.1  158.58
  2589.1  158.25  2597.1  158.13  2645.1  159.27  2661.1  158.99  2781.1   158.5
  2797.1  158.23  2821.1  158.85  3173.1  158.78  3189.1  158.48  3237.1  158.75
  3245.1  158.62  3356.6   158.6  3517.1  158.58  3525.1  158.79  3533.1   158.7
  3541.1  158.43  3548.9  158.42  3629.1  158.29  3653.1  157.85  3908.9  157.82
  3963.7  157.81  4028.9  157.81  4155.6  157.79  4182.7  157.72  4412.7  157.16
  4443.6  157.08  4459.6  156.58  4563.6  157.25  4603.6  156.79  4675.6  156.62
  4683.6  156.38  4719.9  155.97  4751.9  156.01  4752.1  156.01  4802.8  155.48
  4803.7  155.48    4856  155.42  4856.1  155.42  4919.1  156.57  4919.4  156.58
  4970.7  157.44 4970.79  157.36  4970.9  157.26 4971.01  157.16  4973.4  154.99
    4996  149.99  4997.4  149.61  4999.5  149.59  5003.1   149.7  5003.9  150.02
  5011.6  154.65  5015.6  157.47 5018.19  157.41  5018.3   157.4 5018.41   157.4
  5059.8  156.39  5060.4  156.38  5116.2  155.34  5117.6  155.34  5174.2  155.54
    5175  155.54  5228.4  155.71  5253.3  155.83  5269.2  157.43  5277.9  157.71
  5293.9   157.9  5309.9  158.31  5355.7  158.16  5473.3  157.77  5493.3   157.7
  5509.9  157.65  5525.9  157.89  5543.3  157.86  5655.6  157.64  5740.8  157.41
  5807.6  157.23  5811.9  157.32  5827.9  157.43  5867.9  156.67  5923.9  157.95
  5947.9  157.87  5950.8  157.75  5963.9  157.22  6000.8  157.44  6011.9  157.51
  6051.9  157.11  6083.9   157.6  6090.8  157.51  6099.9   157.4  6170.8  157.45
  6401.6  157.61  6521.6  157.69  6571.9  157.73  6579.9  157.45  6907.9  157.42
  6923.9  158.04  6955.9  158.37  7059.9  157.56  7075.9  157.95  7081.6  157.95
  7121.6  157.95  7395.9  157.93  7403.9  158.13  8551.8   159.4
BR D #Mann= 5
  2197.1      .2  3963.7     .06  4970.7    .048  5015.6     .06  5355.7      .2
BR D Banks=4970.7,5015.6
BC Design=,, 0 ,, 0 ,,,,,,
BC HTab HWMax=159.72

Type RM Length L Ch R = 1 ,28943.8 ,127.3,127.3,127.3
BEGIN DESCRIPTION:
Downstream Section of Bridge/Culvert/Weir
END DESCRIPTION:
XS GIS Cut Line= 6
       2970108.3     13867525.31        2970182.     13865551.11
      2970209.14     13864519.22      2970014.55     13864391.77
      2969606.28     13864301.04      2966911.37     13864223.48
#Sta/Elev= 30
  2197.1   159.6  2565.1  159.47  2597.1  158.11  2645.1  159.25  2797.1  158.21
  2821.1  158.83  3525.1  158.77  3653.1  157.83  3963.7  157.79  4459.6  156.56
  4563.6  157.23    4856   155.4  4970.7  157.42  4973.4  154.97  4999.5  149.57
  5003.9     150  5015.6  157.45  5117.6  155.32  5253.3  155.81  5277.9  157.69
  5355.7  158.14  5827.9  157.41  5867.9  156.65  5923.9  157.93  6051.9  157.09
  6083.9  157.58  6907.9   157.4  6955.9  158.35  7059.9  157.54  8551.8  159.38
#Mann= 5 , 1 , 0
  2197.1      .2       0  3963.7     .06       0  4970.7    .048       0
  5015.6     .06       0  5355.7      .2       0
#XS Ineff= 2 , 0
       0    4960   157.5  5013.3       0     157
Permanent Ineff=
       F       F
Bank Sta=4970.7,5015.6
Exp/Cntr=0.5,0.3

Type RM Length L Ch R = 1 ,28816.5 ,934.1,848.8,668.3
BEGIN DESCRIPTION:
Cross Section 28816.5-Interpolated
END DESCRIPTION:
XS GIS Cut Line= 6
      2971064.04     13867014.24      2971036.37     13866202.74
      2970467.35     13864917.85      2970071.11     13864255.02
      2969670.35     13864141.55      2967069.65     13864036.62
#Sta/Elev= 30
  2518.6  159.14  2814.8  158.76  3330.6  157.92  3586.6  157.02  3602.6  156.56
  3626.6  157.57  4034.6  157.51  4976.4   155.6  4993.3  152.72  4997.6   149.6
  5000.2  149.35  5002.6  149.72  5006.7  152.84  5020.6  156.78  5030.5  155.42
    5109  155.12    5317  156.49    5349  156.12    5381  157.02    5453  157.03
  5508.5  156.39    5925  156.09    7277  157.63    7293  158.03    7429  157.65
    7533  158.58  7566.8  158.05    7581  158.49    7805     159  8527.8  159.08
#Mann= 5 , 1 , 0
  2518.6      .2       0  2814.8     .08       0  4976.4    .048       0
  5020.6     .08       0  7566.8      .2       0
Bank Sta=4976.4,5020.6
Exp/Cntr=0.3,0.1

Type RM Length L Ch R = 1 ,27967.7 ,1512.3,826.8,508.9
BEGIN DESCRIPTION:
Cross Section 27967.7
END DESCRIPTION:
XS GIS Cut Line= 6
      2972690.42     13866751.54      2972030.03     13865656.82
      2970805.46     13864027.39      2970363.62      13863765.2
      2969227.47     13863687.52      2967770.79     13863711.38
#Sta/Elev= 30
  1772.3  158.83  2814.8  157.79  4386.8  157.01  4426.8  157.44  4518.9  156.69
  4782.9  156.15  4798.9  156.57  4976.4  154.09  4985.7  152.13  4993.3  151.21
  4997.6  148.09  5000.2  147.84  5002.6  148.21  5006.7  151.33  5020.6  155.27
  5068.7  154.64  5137.6  156.17  5241.6  156.44  5257.6  155.79  5273.6  156.42
  5699.3  157.52  5731.3  156.28  5763.3  156.54  5787.3   156.1  5803.3  157.21
  5819.3  157.49  6539.3  155.83  6571.3  156.52  7566.8   157.8    8199  158.65
#Mann= 5 , 1 , 0
  1772.3      .2       0  2814.8     .08       0  4976.4    .048       0
  5020.6     .08       0  7566.8      .2       0
Bank Sta=4976.4,5020.6
Exp/Cntr=0.3,0.1

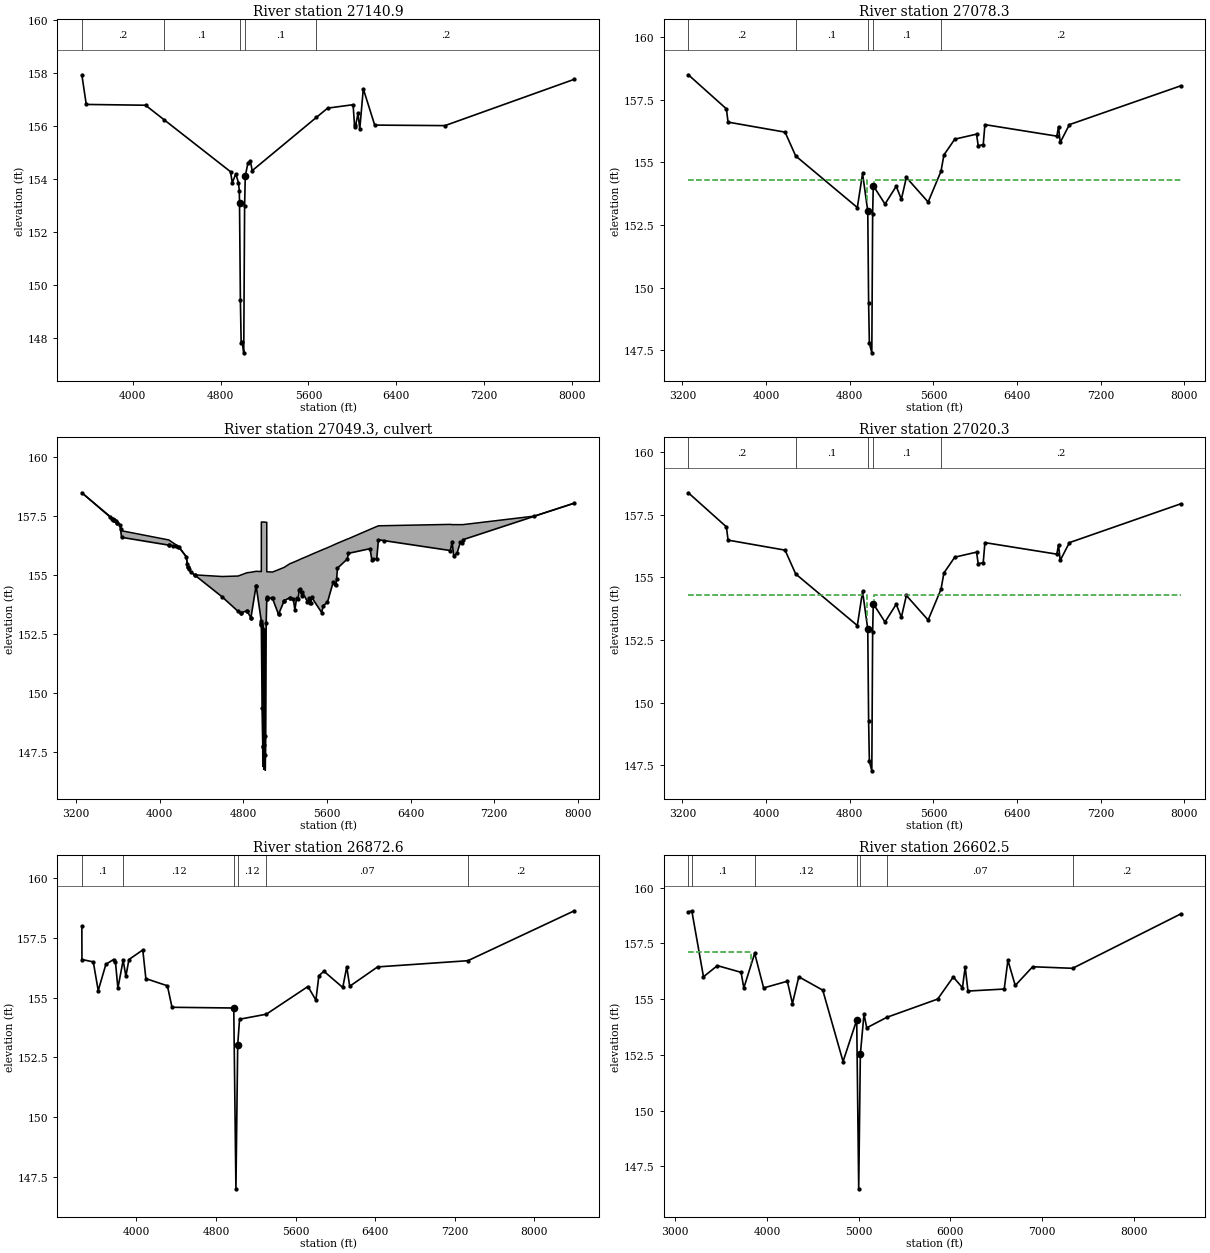
Type RM Length L Ch R = 1 ,27140.9 ,62.6,62.6,62.6
BEGIN DESCRIPTION:
Cross Section 27140.9-Interpolated
END DESCRIPTION:
XS GIS Cut Line= 6
      2972579.87     13863987.73      2972102.33     13863658.76
      2971437.58     13863458.14      2971256.23     13863403.42
      2970242.05     13863511.82      2968242.32     13863614.22
#Sta/Elev= 30
  3536.5  157.94  3576.5  156.82  4116.4  156.79  4283.2  156.25  4890.7  154.28
  4906.7  153.86  4938.7   154.2  4962.7  153.87  4970.7  153.57  4972.7   153.1
  4980.6  149.43  4987.7  147.82  4997.6  147.85  5011.1  147.44  5019.1     153
  5025.2  154.11  5048.2  154.59  5072.2  154.67  5088.2  154.32  5672.8  156.33
  5775.4  156.68  6007.4  156.81  6020.1  156.04  6028.1  155.98  6052.1  156.48
  6068.1  155.89  6100.1  157.41  6204.1  156.04  6844.1  156.02  8022.5  157.77
#Mann= 5 , 1 , 0
  3536.5      .2       0  4283.2      .1       0  4972.7    .048       0
  5025.2      .1       0  5672.8      .2       0
Bank Sta=4972.7,5025.2
Exp/Cntr=0.5,0.3

Type RM Length L Ch R = 1 ,27078.3 ,58,58,58
BEGIN DESCRIPTION:
Upstream Section of Bridge/Culvert/Weir
END DESCRIPTION:
XS GIS Cut Line= 6
      2972951.56     13863695.77      2971993.74     13863353.69
      2971557.62     13863345.98      2971056.65     13863329.69
      2970628.61     13863317.87      2968307.39     13863465.29
#Sta/Elev= 30
  3256.7   158.5  3620.7  157.14  3636.7  156.61  4181.8  156.21  4283.2  155.26
  4872.8   153.2  4922.7  154.56  4972.4  153.06  4980.6  149.39  4987.7  147.78
  5011.1   147.4  5019.1  152.96  5025.2  154.07  5137.2  153.34  5244.5  154.05
  5293.6  153.53  5341.6   154.4  5549.6  153.42  5672.8  154.65  5700.4   155.3
  5804.4  155.93  6012.4  156.13  6028.4  155.67  6076.4  155.71  6092.4  156.51
  6780.4  156.05  6796.4  156.43  6812.4   155.8  6900.4  156.51  7965.3  158.06
#Mann= 5 , 1 , 0
  3256.7      .2       0  4283.2      .1       0  4972.4    .048       0
  5025.2      .1       0  5672.8      .2       0
#XS Ineff= 2 , 0
       0    4961   154.3    5035       0   154.3
Permanent Ineff=
       F       F
Bank Sta=4972.4,5025.2
Exp/Cntr=0.5,0.3

Type RM Length L Ch R = 2 ,27049.3 ,,,
BEGIN DESCRIPTION:
CLAY ROAD
Structure ID: T00-13
END DESCRIPTION:
Bridge Culvert--1,0,-1,-1, 0
Deck Dist Width WeirC Skew NumUp NumDn MinLoCord MaxHiCord MaxSubmerge Is_Ogee
10,38,3,0, 60, 60, , , 0.95, 0, 1,1,,
  3256.7  3620.7  3636.7  4088.2  4181.8  4253.8  4269.8  4295.8  4335.3    4597
  4750.7  4835.6  4873.3  4922.7  4972.4 4972.59  4972.7  4980.6  4987.7  4997.6
  5011.1  5019.1  5024.8 5024.91  5025.2  5079.7  5137.2  5192.2  5244.5  5277.8
  5293.6  5309.6  5325.6  5333.6  5341.6  5357.6  5365.6  5413.6  5429.6  5437.6
  5445.6  5453.6  5549.6  5565.6  5604.4  5660.4  5684.4  5700.4  5796.4  5804.4
  6012.4  6028.4  6076.4  6092.4  6780.4  6796.4  6812.4  6900.4  7580.4  7965.3
   158.5  157.15  156.89   156.5  156.22   155.8  155.38  155.16  155.02  154.95
  154.97  155.11  155.13  155.17  155.16  155.16  157.26  157.26  157.26  157.26
  157.25  157.25  157.25  155.15  155.15  155.14  155.24  155.34  155.49  155.55
  155.58  155.61  155.64  155.66  155.67  155.71  155.72  155.81  155.84  155.86
  155.87  155.89  156.07   156.1  156.17  156.28  156.33  156.36  156.54  156.55
  156.95  156.98  157.07   157.1  157.16  157.15  157.15  157.15  157.51  158.06
   158.5  157.14  156.61  156.28  156.21  155.79  155.37  155.15  155.01  154.09
  153.47  153.49   153.2  154.56  153.06  152.97  152.93  149.39  147.78  147.81
   147.4  152.96     154  154.02  154.07  154.02  153.34  153.93  154.05  154.01
  153.53  154.03     154  154.36   154.4  154.14  154.29  153.88  154.02  153.81
  153.83  154.07  153.42  153.72  153.85  154.72  154.59   155.3   155.7  155.93
  156.13  155.67  155.71  156.51  156.05  156.43   155.8  156.51   157.5  158.06
  3256.7  3620.7  3636.7  4088.2  4181.8  4253.8  4269.8  4295.8  4335.3    4597
  4750.7  4835.6  4873.3  4922.7  4972.4 4972.59  4972.7  4980.6  4987.7  4997.6
  5011.1  5019.1  5024.8 5024.91  5025.2  5079.7  5137.2  5192.2  5244.5  5277.8
  5293.6  5309.6  5325.6  5333.6  5341.6  5357.6  5365.6  5413.6  5429.6  5445.6
  5453.6  5549.6  5565.6  5604.4  5660.4  5684.4  5692.4  5700.4  5796.4  5804.4
  6012.4  6028.4  6076.4  6092.4  6780.4  6796.4  6812.4  6900.4  7580.4  7965.3
   158.5  157.15  156.89   156.5  156.22   155.8  155.38  155.16  155.02  154.95
  154.97  155.11  155.13  155.17  155.16  155.16  157.26  157.26  157.26  157.26
  157.25  157.25  157.25  155.15  155.15  155.14  155.24  155.34  155.49  155.55
  155.58  155.61  155.64  155.66  155.67  155.71  155.72  155.81  155.84  155.87
  155.89  156.07   156.1  156.17  156.28  156.33  156.34  156.36  156.54  156.55
  156.95  156.98  157.07   157.1  157.16  157.15  157.15  157.15  157.51  158.06
   158.4  157.04  156.51  156.18  156.11  155.69  155.27  155.05  154.91  153.99
  153.37  153.39   153.1  154.46  152.96  152.87  152.83  149.29  147.68  147.71
   147.3  152.86   153.9  153.92  153.97  153.92  153.24  153.83  153.95  153.91
  153.43  153.93   153.9  154.26   154.3  154.04  154.19  153.78  153.92  153.73
  153.97  153.32  153.62  153.75  154.62  154.49  154.73   155.2   155.6  155.83
  156.03  155.57  155.61  156.41  155.95  156.33   155.7  156.41   157.4  157.96
BR Coef= 1 , 0 , 0 ,1.25, 0 ,,,0.8,-1,2,0,
WSPro=,,,, 1 ,,,, 0 ,,,, 0 ,,,,-1 ,-1 ,-1 , 0 , 0 , 0 , 0 , 0
Culvert=1,6,,38,0.015,0.2,1,1,3,146.88,4986.9,146.37,4986.9,Culvert #1  , 0 ,10
Culvert Bottom n=0.015
Culvert=1,6,,38,0.015,0.2,1,1,3,146.75,4995,146.35,4995,Culvert #2  , 0 ,10
Culvert Bottom n=0.015
Culvert=1,6,,38,0.015,0.2,1,1,3,146.77,5003.1,146.34,5003.1,Culvert #3  , 0 ,10
Culvert Bottom n=0.015
Culvert=1,6,,38,0.015,0.2,1,1,3,146.71,5011.3,146.35,5011.3,Culvert #4  , 0 ,10
Culvert Bottom n=0.015
BR U #Sta/Elev= 98
  3256.7   158.5  3529.8  157.46  3546.6   157.4  3552.4  157.38  3556.7  157.36
  3559.9  157.35  3562.6  157.34  3578.5  157.29  3594.4  157.23  3595.1  157.23
  3620.7  157.14  3626.3  156.95  3636.7  156.61    4088  156.28  4088.2  156.28
  4132.2  156.25  4158.4  156.23  4176.8  156.21  4181.8  156.21  4253.8  155.79
    4266  155.47  4269.8  155.37  4273.8  155.34  4283.2  155.26  4295.8  155.15
  4335.3  155.01    4339     155    4597  154.09  4750.7  153.47  4775.8  153.42
  4778.3  153.42  4835.5  153.49  4835.6  153.49  4872.8   153.2  4873.3   153.2
  4922.7  154.56  4923.1  154.55  4972.4  153.06 4972.59  152.97  4972.7  152.93
 4972.81  152.88  4980.6  149.39  4987.7  147.78    4991  147.74  4997.6  147.81
  5011.1   147.4  5012.4  148.19  5019.1  152.96 5024.69  153.98  5024.8     154
 5024.91  154.02  5025.2  154.07  5076.9  154.02  5079.7  154.02  5137.2  153.34
  5137.7  153.35  5192.2  153.93  5192.3  153.93  5244.5  154.05  5244.6  154.05
  5277.8  154.01  5293.6  153.53  5309.6  154.03  5325.6     154  5333.6  154.36
  5341.6   154.4  5357.6  154.14  5365.6  154.29  5413.6  153.88  5429.6  154.02
  5437.6  153.81  5445.6  153.83  5453.6  154.07  5549.6  153.42  5565.6  153.72
  5604.4  153.85  5660.4  154.72  5672.8  154.65  5684.4  154.59  5692.4  154.83
  5700.4   155.3  5796.4   155.7  5804.4  155.93  6012.4  156.13  6028.4  155.67
  6038.7  155.68  6076.4  155.71  6092.4  156.51  6147.2  156.47  6780.4  156.05
  6796.4  156.43  6812.4   155.8  6844.4  155.95  6876.4  156.41  6892.4  156.35
  6900.4  156.51  7580.4   157.5  7965.3  158.06
BR U #Mann= 5
  3256.7      .2  4283.2      .1  4972.4    .048  5025.2      .1  5672.8      .2
BR U Banks=4972.4,5025.2
BR D #Sta/Elev= 98
  3256.7   158.4  3529.8  157.36  3546.6   157.3  3552.4  157.28  3556.7  157.26
  3559.9  157.25  3562.6  157.24  3578.5  157.19  3594.4  157.13  3595.1  157.13
  3620.7  157.04  3626.3  156.85  3636.7  156.51    4088  156.18  4088.2  156.18
  4132.2  156.15  4158.4  156.13  4176.8  156.11  4181.8  156.11  4253.8  155.69
    4266  155.37  4269.8  155.27  4273.8  155.24  4283.2  155.16  4295.8  155.05
  4335.3  154.91    4339   154.9    4597  153.99  4750.7  153.37  4775.8  153.32
  4778.3  153.32  4835.5  153.39  4835.6  153.39  4872.8   153.1  4873.3   153.1
  4922.7  154.46  4923.1  154.45  4972.4  152.96 4972.59  152.87  4972.7  152.83
 4972.81  152.78  4980.6  149.29  4987.7  147.68    4991  147.64  4997.6  147.71
  5011.1   147.3  5012.4  148.09  5019.1  152.86 5024.69  153.88  5024.8   153.9
 5024.91  153.92  5025.2  153.97  5076.9  153.92  5079.7  153.92  5137.2  153.24
  5137.7  153.25  5192.2  153.83  5192.3  153.83  5244.5  153.95  5244.6  153.95
  5277.8  153.91  5293.6  153.43  5309.6  153.93  5325.6   153.9  5333.6  154.26
  5341.6   154.3  5357.6  154.04  5365.6  154.19  5413.6  153.78  5429.6  153.92
  5437.6  153.71  5445.6  153.73  5453.6  153.97  5549.6  153.32  5565.6  153.62
  5604.4  153.75  5660.4  154.62  5672.8  154.55  5684.4  154.49  5692.4  154.73
  5700.4   155.2  5796.4   155.6  5804.4  155.83  6012.4  156.03  6028.4  155.57
  6038.7  155.58  6076.4  155.61  6092.4  156.41  6147.2  156.37  6780.4  155.95
  6796.4  156.33  6812.4   155.7  6844.4  155.85  6876.4  156.31  6892.4  156.25
  6900.4  156.41  7580.4   157.4  7965.3  157.96
BR D #Mann= 5
  3256.7      .2  4283.2      .1  4972.4    .048  5025.2      .1  5672.8      .2
BR D Banks=4972.4,5025.2
BC Design=,, 0 ,, 0 ,,,,,,
BC HTab HWMax=158.5

Type RM Length L Ch R = 1 ,27020.3 ,147.7,147.7,147.7
BEGIN DESCRIPTION:
Downstream Section of Bridge/Culvert/Weir
END DESCRIPTION:
XS GIS Cut Line= 6
       2972961.3      13863638.6      2972003.48     13863296.51
      2971567.36      13863288.8      2971066.39     13863272.51
      2970638.35     13863260.69      2968317.13     13863408.11
#Sta/Elev= 30
  3256.7  158.38  3620.7  157.02  3636.7  156.49  4181.8  156.09  4283.2  155.14
  4872.8  153.08  4922.7  154.44  4972.4  152.94  4980.6  149.27  4987.7  147.66
  5011.1  147.28  5019.1  152.84  5025.2  153.95  5137.2  153.22  5244.5  153.93
  5293.6  153.41  5341.6  154.28  5549.6   153.3  5672.8  154.53  5700.4  155.18
  5804.4  155.81  6012.4  156.01  6028.4  155.55  6076.4  155.59  6092.4  156.39
  6780.4  155.93  6796.4  156.31  6812.4  155.68  6900.4  156.39  7965.3  157.94
#Mann= 5 , 1 , 0
  3256.7      .2       0  4283.2      .1       0  4972.4    .048       0
  5025.2      .1       0  5672.8      .2       0
#XS Ineff= 2 , 0
       0    4961   154.3    5035       0   154.3
Permanent Ineff=
       F       F
Bank Sta=4972.4,5025.2
Exp/Cntr=0.5,0.3

Type RM Length L Ch R = 1 ,26872.6 ,464.3,270.1,48.5
BEGIN DESCRIPTION:
Cross Section 26872.6-Interpolated
END DESCRIPTION:
XS GIS Cut Line= 6
      2972796.92     13863412.24      2971850.98     13863176.73
      2970967.52     13863127.43      2970561.07     13863192.08
      2968408.51     13863324.31      2967891.06     13863388.87
#Sta/Elev= 30
  3451.3     158  3452.3   156.6  3566.2   156.5  3615.9   155.3    3693   156.4
  3770.2   156.6    3789   156.5  3813.7   155.4  3866.5  156.57  3893.9   155.9
  3924.8   156.6  4063.9     157  4094.9   155.8  4311.3   155.5  4357.6   154.6
  4978.5  154.57  5000.3     147  5018.1  153.03  5036.7   154.1  5305.5  154.31
  5724.2  155.47  5804.2   154.9  5834.2  155.92  5884.2  156.11  6074.2  155.43
  6114.2  156.29  6144.2  155.48  6424.2  156.29  7332.1  156.55  8402.3  158.64
#Mann= 6 , 1 , 0
  3451.3      .1       0  3866.5     .12       0  4978.5    .048       0
  5018.1     .12       0  5305.5     .07       0  7332.1      .2       0
#XS Ineff= 2 , 0
       0  4063.9     157               0
Permanent Ineff=
       F       F
Bank Sta=4978.5,5018.1
Exp/Cntr=0.3,0.1

Type RM Length L Ch R = 1 ,26602.5 ,79.9,396.6,410
BEGIN DESCRIPTION:
Cross Section 26602.5-Interpolated
END DESCRIPTION:
XS GIS Cut Line= 6
       2973056.7     13863060.58      2972298.88     13862946.19
      2971726.94     13862717.41      2971297.98      13862860.4
      2970625.94     13863153.52      2967830.38     13863297.84
#Sta/Elev= 30
  3143.1   158.9    3181  158.96  3308.3     156    3460   156.5  3717.9   156.2
  3748.2   155.5  3866.5  157.05  3963.9   155.5  4222.4   155.8    4278   154.8
  4347.2     156  4608.3   155.4  4829.7   152.2  4978.5  154.06  5000.3  146.49
  5018.1  152.52  5057.7  154.33  5087.7  153.71  5305.5  154.18  5860.9     155
  6030.9  155.99  6130.9  155.51  6160.9  156.44  6190.9  155.36  6586.3  155.45
  6626.3  156.74  6706.3  155.61  6896.3  156.45  7332.1  156.38  8510.8  158.82
#Mann= 7 , 1 , 0
  3143.1     .07       0    3181      .1       0  3866.5     .12       0
  4978.5    .048       0  5018.1     .12       0  5305.5     .07       0
  7332.1      .2       0
#XS Ineff= 2 , 0
       0  3829.5   157.1               0
Permanent Ineff=
       F       F
Bank Sta=4978.5,5018.1
Exp/Cntr=0.3,0.1