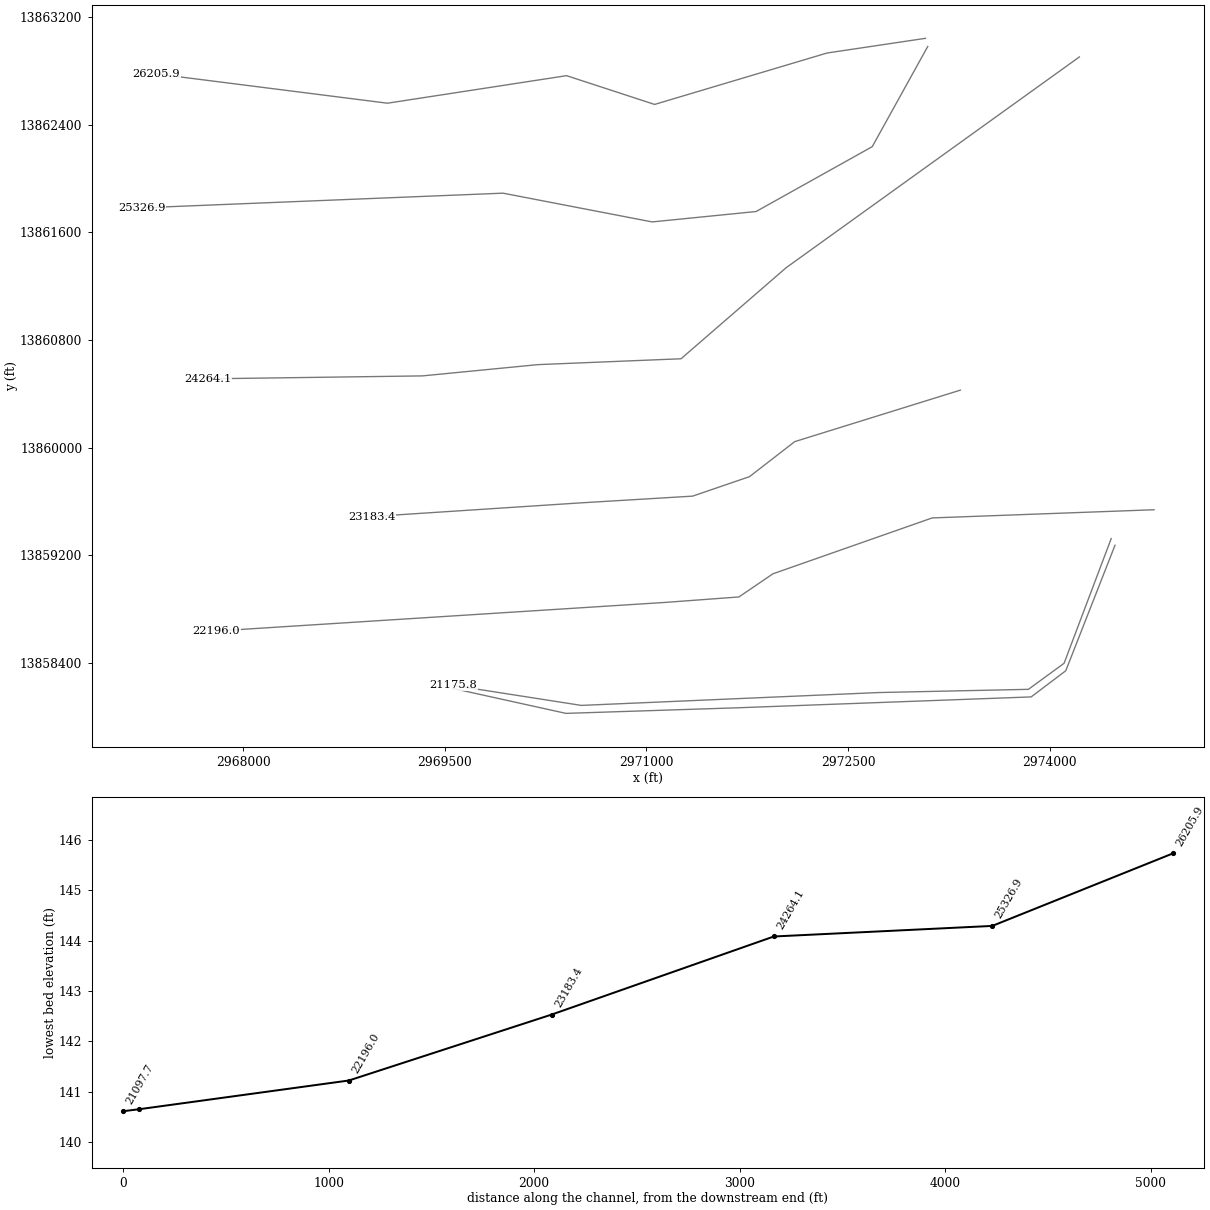
HEC-RAS study T100-00-00.PRJ: T100-00-00

--- T100-00-00.g01 (geometry) --- (continued)

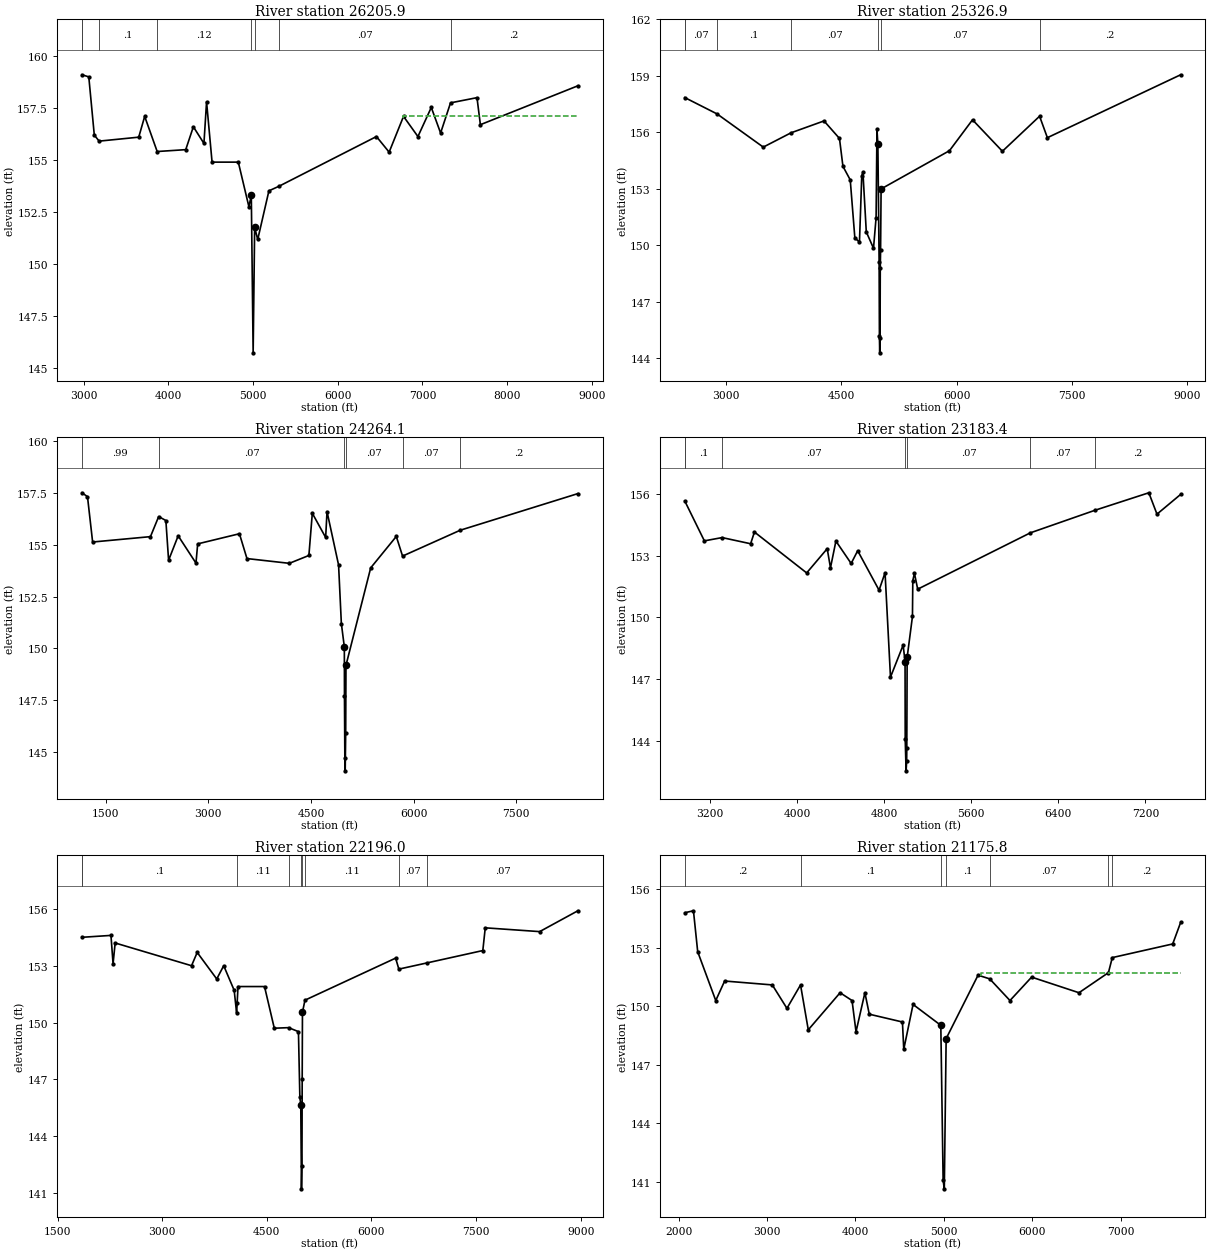
Type RM Length L Ch R = 1 ,26205.9 ,963,879,861.8
BEGIN DESCRIPTION:
Cross Section 26205.9
END DESCRIPTION:
XS GIS Cut Line= 6
      2973075.69     13863041.67       2972343.6     13862932.54
      2971061.31     13862550.58      2970406.53      13862764.3
      2969074.22     13862559.68      2967356.33     13862777.26
#Sta/Elev= 30
  2978.7   159.1  3058.7     159  3123.7   156.2    3181  155.91  3648.7   156.1
  3718.9   157.1  3866.5  155.41  4203.9   155.5  4293.9   156.6  4418.9   155.8
    4450   157.8    4515   154.9    4825   154.9  4949.9  152.76  4978.5   153.3
  5000.3  145.73  5018.1  151.76  5054.3  151.18  5186.5  153.52  5305.5  153.74
  6456.8  156.13  6606.8  155.38  6776.8   157.1  6946.8  156.13  7104.7  157.53
  7214.7   156.3  7332.1  157.75  7644.7     158  7684.7   156.7  8836.3  158.57
#Mann= 8 , 1 , 0
  2978.7      .2       0  2978.7     .07       0    3181      .1       0
  3866.5     .12       0  4978.5    .048       0  5018.1     .12       0
  5305.5     .07       0  7332.1      .2       0
#XS Ineff= 2 , 0
       0  3718.9   157.1  6766.8       0   157.1
Permanent Ineff=
       F       F
Bank Sta=4978.5,5018.1
Exp/Cntr=0.3,0.1

Type RM Length L Ch R = 1 ,25326.9 ,518.9,1062.8,1289.2
BEGIN DESCRIPTION:
Cross Section 25326.9
END DESCRIPTION:
XS GIS Cut Line= 6
      2973092.92     13862981.16      2972680.09     13862236.83
      2971816.13     13861754.84      2971043.12     13861677.54
      2969933.63     13861891.25      2967247.62     13861782.29
#Sta/Elev= 30
  2462.4  157.84  2883.3  156.97  3483.5  155.21  3844.9  155.97  4273.7   156.6
  4474.9  155.67  4519.9  154.19  4614.9  153.47  4674.9  150.39  4734.9  150.17
  4764.9   153.7  4779.9  153.88  4823.8  150.71  4917.5  149.84  4951.3  151.47
  4962.5  156.15  4974.5  155.35  4990.6  149.12  4994.4  145.18  4998.5  144.29
  5002.8   145.1  5005.6  148.81  5009.8  149.75  5016.3  152.99  5905.7  155.02
  6205.7  156.66  6594.5  154.99  7078.1  156.85  7179.5  155.71    8913  159.05
#Mann= 7 , 1 , 0
  2462.4      .2       0  2462.4     .07       0  2883.3      .1       0
  3844.9     .07       0  4974.5    .048       0  5016.3     .07       0
  7078.1      .2       0
#XS Ineff= 2 , 0
       0  4273.7   156.6  6205.7       0  156.66
Permanent Ineff=
       F       F
Bank Sta=4974.5,5016.3
Exp/Cntr=0.3,0.1

Type RM Length L Ch R = 1 ,24264.1 ,1366.4,1080.7,1026.8
BEGIN DESCRIPTION:
Cross Section 24264.1
END DESCRIPTION:
XS GIS Cut Line= 6
       2974220.5      13862903.4      2972040.11     13861337.66
      2971257.93      13860660.8      2970192.81     13860617.15
      2969334.32     13860533.48      2967737.37     13860511.66
#Sta/Elev= 30
  1155.2  157.52  1235.2  157.33  1310.2  155.14  2155.2   155.4  2275.2  156.37
  2380.2  156.18  2420.2  154.26  2560.2  155.44  2820.2  154.12  2845.2  155.05
  3455.2  155.54  3565.2  154.34  4184.5  154.11  4470.1  154.49  4520.1  156.53
  4715.1  155.36  4735.1  156.61  4903.9  154.03  4944.5   151.2    4988  150.07
  4989.9  147.69  4995.5  144.69  5000.7  144.08  5007.8  145.92  5011.9  149.18
  5373.1  153.89  5747.4  155.41  5838.8  154.46  6681.7  155.71  8400.2  157.48
#Mann= 6 , 1 , 0
  1155.2     .99       0  2275.2     .07       0    4988    .048       0
  5011.9     .07       0  5838.8     .07       0  6681.7      .2       0
#XS Ineff= 2 , 0
       0  3455.2  155.54  5747.4       0  155.41
Permanent Ineff=
       F       F
Bank Sta=4988,5011.9
Exp/Cntr=0.3,0.1

Type RM Length L Ch R = 1 ,23183.4 ,988.3,987.4,793.4
BEGIN DESCRIPTION:
Cross Section 23183.4
END DESCRIPTION:
XS GIS Cut Line= 6
      2973335.47     13860427.65      2972103.66      13860045.1
      2971767.21     13859784.84      2971344.37     13859640.15
      2970504.09     13859589.53      2968955.22     13859488.29
#Sta/Elev= 30
  2966.7  155.66  3146.7  153.72  3309.6  153.88  3571.7  153.58  3606.7  154.15
  4086.7  152.16  4275.4  153.34  4305.4  152.41  4355.4  153.71  4495.4  152.62
  4555.4  153.24  4751.9  151.32  4806.9  152.17  4856.9  147.09  4973.2  148.65
  4990.7  147.84  4992.2  144.06  5000.2  142.53  5005.6  143.02  5006.7  143.66
  5009.9  148.05  5058.7  150.04  5061.9  151.79  5076.9  152.14  5106.9  151.37
  6141.8  154.11  6736.4  155.21  7230.6  156.06  7305.6  155.02  7522.8  155.98
#Mann= 7 , 1 , 0
  2966.7      .2       0  2966.7      .1       0  3309.6     .07       0
  4990.7    .048       0  5009.9     .07       0  6141.8     .07       0
  6736.4      .2       0
Bank Sta=4990.7,5009.9
Exp/Cntr=0.3,0.1

Type RM Length L Ch R = 1 ,22196.0 ,1360.5,1020.2,995.8
BEGIN DESCRIPTION:
Cross Section 22196.0
END DESCRIPTION:
XS GIS Cut Line= 6
      2974776.34     13859538.91      2973126.16     13859478.17
      2971941.68     13859063.09      2971688.58     13858890.99
      2971141.89     13858850.49      2967801.04     13858637.89
#Sta/Elev= 30
  1851.2   154.5  2266.2   154.6  2296.2   153.1  2326.2   154.2  3421.2     153
  3502.5   153.7  3782.5   152.3  3882.5     153  4032.5   151.7  4067.5   150.5
  4075.3  151.05  4087.5   151.9  4467.5   151.9  4607.5   149.7  4812.4  149.73
  4953.8  149.52  4973.9  146.07  4987.2  145.66  4997.2  141.22  5004.1  142.44
  5007.5  147.02  5011.3  150.54  5047.1  151.18  6346.9   153.4  6393.2  152.82
  6799.8  153.15  7596.9   153.8  7631.9     155  8411.9   154.8  8959.5   155.9
#Mann= 9 , 1 , 0
  1851.2      .2       0  1851.2      .1       0  4075.3     .11       0
  4812.4      .1       0  4987.2    .048       0  5011.3      .1       0
  5047.1     .11       0  6393.2     .07       0  6799.8     .07       0
Bank Sta=4987.2,5011.3
Exp/Cntr=0.3,0.1

Type RM Length L Ch R = 1 ,21175.8 ,115.6,78.1,74
BEGIN DESCRIPTION:
Cross Section 21175.8-Interpolated
END DESCRIPTION:
XS GIS Cut Line= 6
      2974457.36     13859324.46      2974107.05     13858398.25
      2973841.66     13858204.52      2972727.02     13858180.63
      2970516.32     13858085.09      2969564.99     13858233.38
#Sta/Elev= 30
  2069.8   154.8  2167.9   154.9    2216   152.8  2420.2   150.3  2520.7   151.3
    3060   151.1  3225.5   149.9  3379.4   151.1  3466.9   148.8    3827   150.7
  3962.1   150.3  4007.1   148.7  4107.6   150.7  4157.1   149.6  4532.2   149.2
  4547.2   147.8  4652.4   150.1  4966.4  149.03  4992.6  141.09  5005.9  140.65
  5026.8  148.35  5387.9   151.6  5519.8  151.41  5748.8   150.3  5993.8   151.5
  6529.5   150.7  6862.9  151.73  6906.3   152.5    7590   153.2  7679.5   154.3
#Mann= 7 , 1 , 0
  2069.8      .2       0  3379.4      .1       0  4966.4    .048       0
  5026.8      .1       0  5519.8     .07       0  6862.9     .07       0
  6906.3      .2       0
#XS Ineff= 2 , 0
       0                  5417.2       0   151.7
Permanent Ineff=
       F       F
Bank Sta=4966.4,5026.8
Exp/Cntr=0.5,0.3

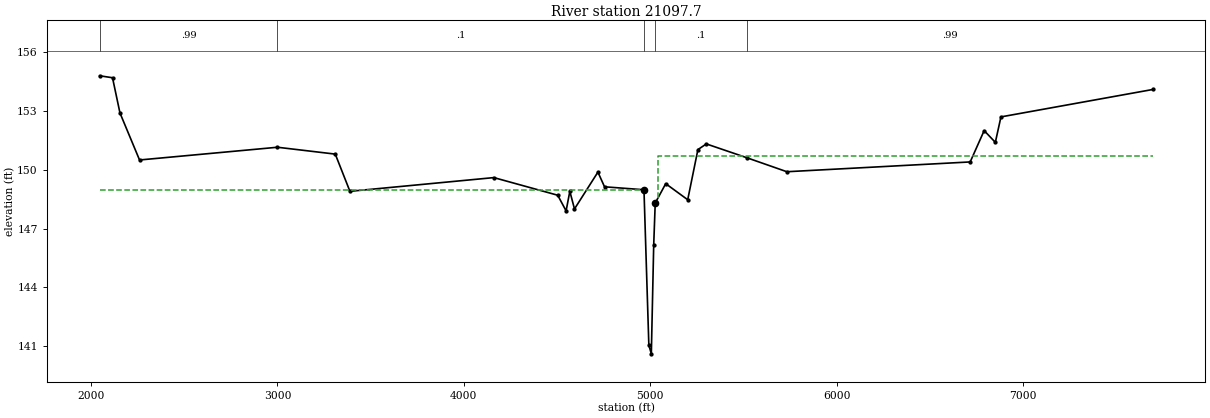
Type RM Length L Ch R = 1 ,21097.7 ,59,59,59
BEGIN DESCRIPTION:
Upstream Section of Bridge/Culvert/Weir
END DESCRIPTION:
XS GIS Cut Line= 6
      2974485.63     13859274.98      2974119.59     13858342.71
      2973862.21     13858148.25      2971670.87      13858067.1
      2970401.83     13858025.89      2969558.33     13858211.79
#Sta/Elev= 30
  2045.8  154.81  2114.9  154.71  2154.9  152.91  2259.9  150.51    3000  151.16
  3310.1  150.81  3388.7  148.91  4160.9  149.61  4503.6  148.71  4548.6  147.91
  4568.6  148.91  4593.6  148.01  4719.3  149.89  4754.8  149.14  4966.4  148.99
  4992.6  141.05  5005.9  140.61  5018.6  146.15  5026.8  148.31  5083.1   149.3
  5201.1  148.48  5255.8  151.04    5301  151.33  5519.8  150.62  5733.1  149.91
  6716.7  150.41  6791.7  152.01  6851.7  151.41  6881.7  152.71  7696.3  154.11
#Mann= 5 , 1 , 0
  2045.8     .99       0    3000      .1       0  4966.4    .048       0
  5026.8      .1       0  5519.8     .99       0
#XS Ineff= 2 , 0
       0    4964     149    5042       0   150.7
Permanent Ineff=
       F       F
Bank Sta=4966.4,5026.8
Exp/Cntr=0.5,0.3