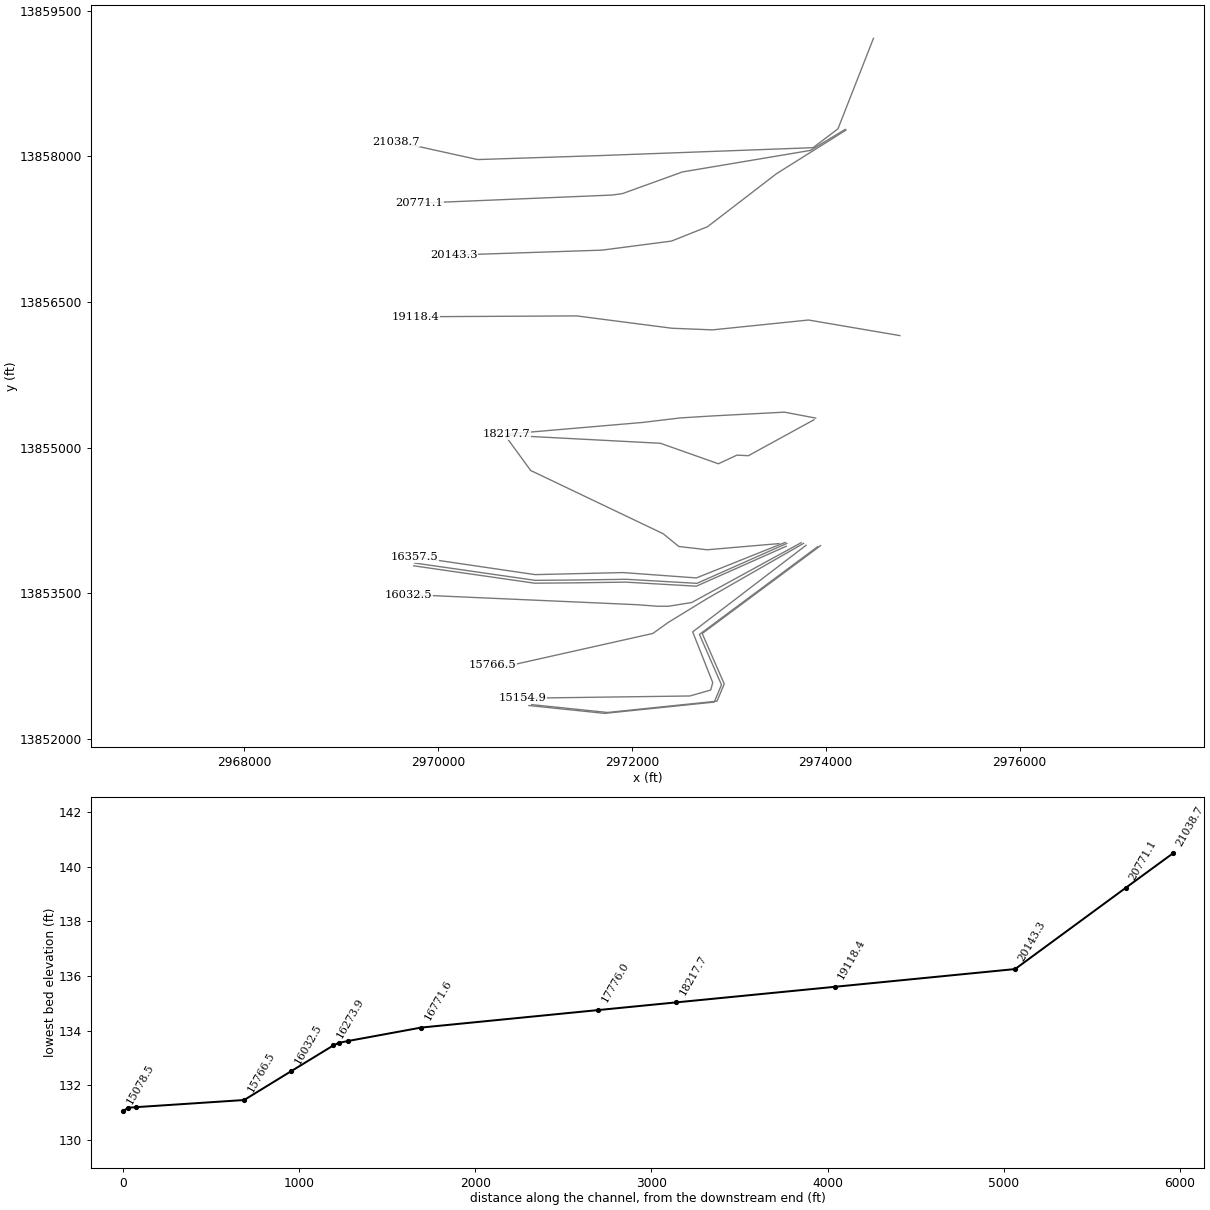
HEC-RAS study T100-00-00.PRJ: T100-00-00

--- T100-00-00.g01 (geometry) --- (continued)

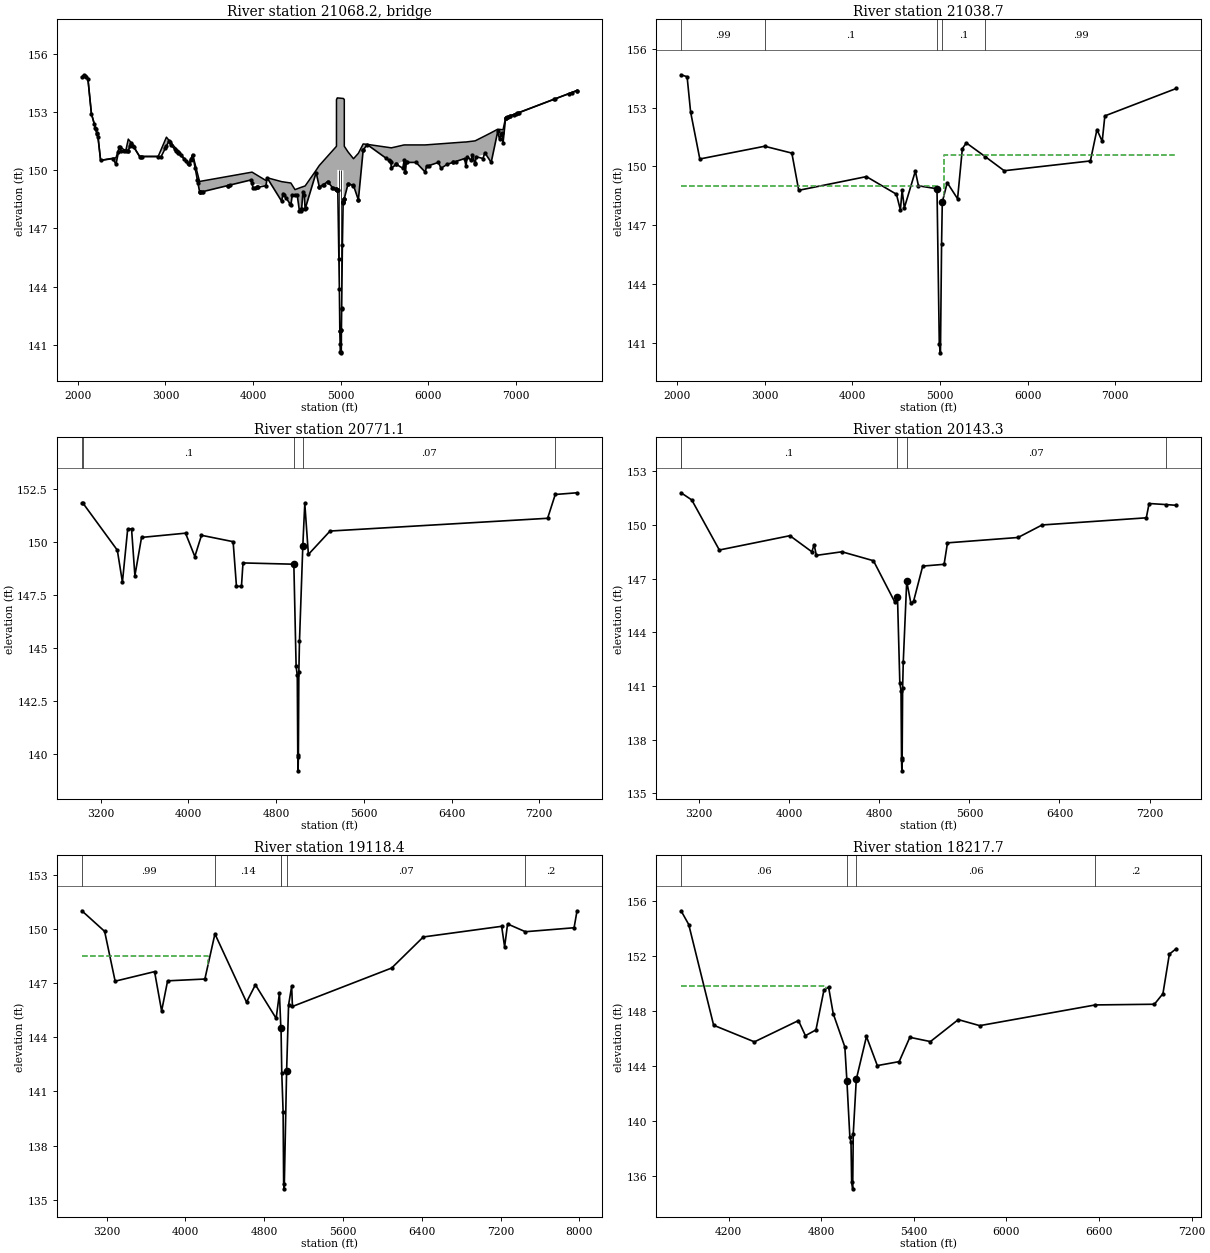
Type RM Length L Ch R = 3 ,21068.2 ,,,
BEGIN DESCRIPTION:
MORTON ROAD
Structure ID: T00-12
END DESCRIPTION:
Bridge Culvert--1,0,-1,-1, 0
Deck Dist Width WeirC Skew NumUp NumDn MinLoCord MaxHiCord MaxSubmerge Is_Ogee
10,39,2.6,0, 60, 60, , , 0.95, 0, 1,1,,
  2045.8  2069.9  2114.9  2154.9  2229.9  2259.9  2434.9  2474.9  2546.5  2575.4
  2609.9  2704.9  2916.8  3010.5  3039.9  3270.1  3310.1  3388.7  3987.8  4145.9
  4160.9  4325.9  4340.9  4430.9  4478.2  4548.6  4568.6  4593.6  4719.3  4754.8
 4951.09  4951.2  4960.7 4960.81  4960.9 5030.69  5030.8  5040.5 5040.61  5083.1
  5145.4  5201.1  5255.8    5301  5577.3  5723.1  5733.1  5748.1    5964  6413.4
  6428.4  6443.4  6498.4  6533.4  6643.4  6716.7  6791.7  6851.7  6881.7  7696.3
   154.8  154.91  154.71  152.91  151.71  150.51  150.64  151.21     151   151.6
  151.41  150.71  150.71   151.7  151.54  150.31  150.81  149.42   149.9  149.47
  149.61  149.41   149.4  149.34     149  149.12  149.15  149.19     150  150.24
  151.23  153.63  153.72  153.72  153.72  153.69  153.69  153.63  151.23  150.94
  150.59  150.87  151.35  151.33  151.15   151.3   151.3   151.3   151.3  151.45
  151.45  151.46  151.49  151.51  151.76  151.93  152.11  152.08  152.71   154.1
   154.8   154.9   154.7   152.9   151.7   150.5   150.3   151.2     151  151.01
   151.4   150.7   150.7  151.24   151.5   150.3   150.8   148.9  149.32   149.2
   149.6   148.4   148.8   148.2   148.7   147.9   148.9     148  149.88  149.13
  149.01  149.01  148.99  148.99  150.02  149.99  148.37  148.54  148.54  149.29
  149.21  148.47  151.03  151.32   150.1   150.5   149.9   150.4   149.9   150.6
   150.2   150.7   150.8   150.3   150.9   150.4     152   151.4   152.7   154.1
  2045.8  2069.9  2114.9  2154.9  2229.9  2259.9  2434.9  2474.9  2546.5  2575.4
  2609.9  2704.9  2916.8  3010.5  3039.9  3270.1  3310.1  3388.7  3987.8  4145.9
  4160.9  4325.9  4340.9  4430.9  4478.2  4548.6  4568.6  4593.6  4719.3  4754.8
 4951.09  4951.2  4960.7 4960.81  4960.9 5030.69  5030.8  5040.5 5040.61  5083.1
  5145.4  5201.1  5255.8    5301  5577.3  5723.1  5733.1  5748.1    5964  6413.4
  6428.4  6443.4  6498.4  6533.4  6643.4  6716.7  6791.7  6851.7  6881.7  7696.3
   154.8  154.91  154.71  152.91  151.71  150.51  150.64  151.21     151   151.6
  151.41  150.71  150.71   151.7  151.54  150.31  150.81  149.42   149.9  149.47
  149.61  149.41   149.4  149.34     149  149.12  149.15  149.19     150  150.24
  151.23  153.63  153.72  153.72  153.72  153.69  153.69  153.63  151.23  150.94
  150.59  150.87  151.35  151.33  151.15   151.3   151.3   151.3   151.3  151.45
  151.45  151.46  151.49  151.51  151.76  151.93  152.11  152.08  152.71   154.1
  154.73  154.83  154.63  152.83  151.63  150.43  150.23  151.13  150.93  150.94
  151.33  150.63  150.63  151.17  151.43  150.23  150.73  148.83  149.25  149.13
  149.53  148.33  148.73  148.13  148.63  147.83  148.83  147.93  149.81  149.06
  148.94  148.94  148.92  148.92  149.95  149.92   148.3  148.47  148.47  149.22
  149.14   148.4  150.96  151.25  150.03  150.43  149.83  150.33  149.83  150.53
  150.13  150.63  150.73  150.23  150.83  150.33  151.93  151.33  152.63  154.03
Pier Skew, UpSta & Num, DnSta & Num=  ,4984.3, 2 ,4984.3, 2 , 0 , 0 , 0 ,,
     1.4     1.4
  142.62  151.01
     1.4     1.4
  142.55  150.94
Pier Skew, UpSta & Num, DnSta & Num=  ,5007.7, 2 ,5007.7, 2 , 0 , 0 , 0 ,,
     1.4     1.4
  140.47     151
     1.4     1.4
   140.4  150.93
Abutment Skew #Up #Dn= , 2 , 2
  4960.7  4989.7
  150.02  141.71
  4960.7  4989.7
  149.95  141.64
Abutment Skew #Up #Dn= , 2 , 2
  5010.4 5030.89
  142.92  149.99
  5010.4 5030.89
  142.85  149.92
BR Coef= 1 , 1 , 0 ,1.25, 0 ,,,0.8,0,2,0,
WSPro=,,,, 1 ,,,, 0 ,,,, 0 ,,,,-1 ,-1 ,-1 , 0 , 0 , 0 , 0 , 0
BR U #Sta/Elev= 192
  2045.8   154.8  2069.9   154.9  2075.9  154.87    2092   154.8  2114.9   154.7
  2154.9   152.9  2188.7  152.36  2199.3  152.19  2204.8   152.1  2217.3   151.9
  2220.9  151.84  2229.9   151.7  2259.9   150.5  2399.9   150.6  2434.9   150.3
  2462.6  150.92  2474.9   151.2  2477.1  151.18  2494.9     151  2527.1     151
  2546.5     151  2574.9     151  2575.4  151.01  2595.9  151.24  2604.3  151.34
  2609.9   151.4  2627.5  151.27  2639.9  151.18  2704.9   150.7  2720.5   150.7
  2731.6   150.7  2916.8   150.7  2949.9   150.7    3000  151.15  3010.5  151.24
  3039.9   151.5  3047.3  151.43  3060.1   151.3  3108.6  151.07  3122.5     151
    3130  150.97  3139.8  150.92  3141.3  150.91  3151.4  150.87  3172.8  150.76
  3215.6  150.56  3237.1  150.46  3254.1  150.38  3270.1   150.3  3272.9  150.34
  3289.1  150.54  3290.6  150.56  3310.1   150.8  3338.9   150.1  3363.7   149.5
  3369.9  149.35  3388.7   148.9    3393   148.9  3397.6   148.9  3412.6   148.9
  3428.7   148.9  3712.2  149.21  3712.7  149.21  3741.2  149.24  3978.7   149.5
  3987.8  149.32  3998.7   149.1  4025.9   149.1  4042.9  149.11  4045.9  149.12
  4060.4  149.13  4145.9   149.2  4160.9   149.6  4325.9   148.4  4340.9   148.8
  4350.5  148.74  4373.1  148.59  4423.1  148.25  4430.9   148.2  4445.9   148.7
  4478.2   148.7  4503.6   148.7  4528.6   147.9  4543.6     148  4548.6   147.9
  4553.6     148  4568.6   148.9  4583.6   148.7  4593.6     148  4598.3  148.07
  4719.3  149.88  4754.8  149.13  4755.5  149.13  4801.7  149.26  4803.2  149.26
  4850.8  149.41  4852.8   149.4  4905.5   149.1  4906.3   149.1 4951.09  149.01
  4951.2  149.01 4951.31  149.01  4960.7  148.99 4960.81  148.99  4960.9  148.99
  4966.4  148.98  4979.7  145.42  4984.3  143.91  4989.6  141.73  4989.7  141.71
  4992.6  141.04  4994.9  140.64  4999.8  140.62  5005.9   140.6  5007.4  141.78
  5007.7   141.8  5010.3  142.88  5010.4  142.92  5018.6  146.14  5026.8   148.3
 5030.69  148.37  5030.8  148.37  5030.9  148.37 5040.39  148.54  5040.5  148.54
 5040.61  148.54  5083.1  149.29  5083.4  149.29  5144.6  149.22  5145.4  149.21
  5199.8  148.49  5201.1  148.47  5255.8  151.03  5257.9  151.04    5301  151.32
  5519.8  150.61  5552.3   150.5  5559.1  150.47  5572.3   150.4  5577.3   150.1
  5633.1   150.3  5634.1   150.3  5708.1   150.1  5723.1   150.5  5733.1   149.9
  5738.1   149.9  5748.1   150.4  5753.1   150.4    5859   150.4    5964   149.9
    5979   150.2  6009.3  150.24    6114   150.4    6144   150.1    6214   150.3
  6277.4   150.4  6279.4   150.4  6309.5  150.44  6413.4   150.6  6428.4   150.2
  6443.4   150.7  6488.4   150.5  6498.4   150.8    6530  150.35  6533.4   150.3
  6543.4   150.7  6623.4   150.6  6643.4   150.9  6716.7   150.4  6791.7     152
  6811.7   151.6  6832.5  151.85  6836.7   151.9  6851.7   151.4  6880.9  152.67
  6881.7   152.7  6886.6  152.71  6896.3  152.73  6911.6  152.75    6926  152.78
  6930.5  152.78  6973.1  152.86  7003.8  152.91  7015.7  152.93  7019.1  152.94
  7028.3  152.95  7438.2  153.66  7449.2  153.68  7602.8  153.94  7633.5  153.99
  7693.4   154.1  7696.3   154.1
BR U #Mann= 5
  2045.8     .99    3000      .1  4966.4    .048  5026.8      .1  5519.8     .99
BR U Banks=4966.4,5026.8
BR D #Sta/Elev= 192
  2045.8  154.73  2069.9  154.83  2075.9   154.8    2092  154.73  2114.9  154.63
  2154.9  152.83  2188.7  152.29  2199.3  152.12  2204.8  152.03  2217.3  151.83
  2220.9  151.77  2229.9  151.63  2259.9  150.43  2399.9  150.53  2434.9  150.23
  2462.6  150.85  2474.9  151.13  2477.1  151.11  2494.9  150.93  2527.1  150.93
  2546.5  150.93  2574.9  150.93  2575.4  150.94  2595.9  151.17  2604.3  151.27
  2609.9  151.33  2627.5   151.2  2639.9  151.11  2704.9  150.63  2720.5  150.63
  2731.6  150.63  2916.8  150.63  2949.9  150.63    3000  151.08  3010.5  151.17
  3039.9  151.43  3047.3  151.36  3060.1  151.23  3108.6     151  3122.5  150.93
    3130   150.9  3139.8  150.85  3141.3  150.84  3151.4   150.8  3172.8  150.69
  3215.6  150.49  3237.1  150.39  3254.1  150.31  3270.1  150.23  3272.9  150.27
  3289.1  150.47  3290.6  150.49  3310.1  150.73  3338.9  150.03  3363.7  149.43
  3369.9  149.28  3388.7  148.83    3393  148.83  3397.6  148.83  3412.6  148.83
  3428.7  148.83  3712.2  149.14  3712.7  149.14  3741.2  149.17  3978.7  149.43
  3987.8  149.25  3998.7  149.03  4025.9  149.03  4042.9  149.04  4045.9  149.05
  4060.4  149.06  4145.9  149.13  4160.9  149.53  4325.9  148.33  4340.9  148.73
  4350.5  148.67  4373.1  148.52  4423.1  148.18  4430.9  148.13  4445.9  148.63
  4478.2  148.63  4503.6  148.63  4528.6  147.83  4543.6  147.93  4548.6  147.83
  4553.6  147.93  4568.6  148.83  4583.6  148.63  4593.6  147.93  4598.3     148
  4719.3  149.81  4754.8  149.06  4755.5  149.06  4801.7  149.19  4803.2  149.19
  4850.8  149.34  4852.8  149.33  4905.5  149.03  4906.3  149.03 4951.09  148.94
  4951.2  148.94 4951.31  148.94  4960.7  148.92 4960.81  148.92  4960.9  148.92
  4966.4  148.91  4979.7  145.35  4984.3  143.84  4989.6  141.66  4989.7  141.64
  4992.6  140.97  4994.9  140.57  4999.8  140.55  5005.9  140.53  5007.4  141.71
  5007.7  141.73  5010.3  142.81  5010.4  142.85  5018.6  146.07  5026.8  148.23
 5030.69   148.3  5030.8   148.3  5030.9   148.3 5040.39  148.47  5040.5  148.47
 5040.61  148.47  5083.1  149.22  5083.4  149.22  5144.6  149.15  5145.4  149.14
  5199.8  148.42  5201.1   148.4  5255.8  150.96  5257.9  150.97    5301  151.25
  5519.8  150.54  5552.3  150.43  5559.1   150.4  5572.3  150.33  5577.3  150.03
  5633.1  150.23  5634.1  150.23  5708.1  150.03  5723.1  150.43  5733.1  149.83
  5738.1  149.83  5748.1  150.33  5753.1  150.33    5859  150.33    5964  149.83
    5979  150.13  6009.3  150.17    6114  150.33    6144  150.03    6214  150.23
  6277.4  150.33  6279.4  150.33  6309.5  150.37  6413.4  150.53  6428.4  150.13
  6443.4  150.63  6488.4  150.43  6498.4  150.73    6530  150.28  6533.4  150.23
  6543.4  150.63  6623.4  150.53  6643.4  150.83  6716.7  150.33  6791.7  151.93
  6811.7  151.53  6832.5  151.78  6836.7  151.83  6851.7  151.33  6880.9   152.6
  6881.7  152.63  6886.6  152.64  6896.3  152.66  6911.6  152.68    6926  152.71
  6930.5  152.71  6973.1  152.79  7003.8  152.84  7015.7  152.86  7019.1  152.87
  7028.3  152.88  7438.2  153.59  7449.2  153.61  7602.8  153.87  7633.5  153.92
  7693.4  154.03  7696.3  154.03
BR D #Mann= 5
  2045.8     .99    3000      .1  4966.4    .048  5026.8      .1  5519.8     .99
BR D Banks=4966.4,5026.8
BC Design=,, 0 ,, 0 ,,,,,,
BC HTab HWMax=154.91

Type RM Length L Ch R = 1 ,21038.7 ,267.6,267.6,267.6
BEGIN DESCRIPTION:
Downstream Section of Bridge/Culvert/Weir
END DESCRIPTION:
XS GIS Cut Line= 6
      2974493.21     13859216.46      2974127.17     13858284.19
      2973869.79     13858089.73      2971678.45     13858008.58
      2970409.41     13857967.37      2969565.91     13858153.28
#Sta/Elev= 30
  2045.8  154.68  2114.9  154.58  2154.9  152.78  2259.9  150.38    3000  151.03
  3310.1  150.68  3388.7  148.78  4160.9  149.48  4503.6  148.58  4548.6  147.78
  4568.6  148.78  4593.6  147.88  4719.3  149.76  4754.8  149.01  4966.4  148.86
  4992.6  140.92  5005.9  140.48  5018.6  146.02  5026.8  148.18  5083.1  149.17
  5201.1  148.35  5255.8  150.91    5301   151.2  5519.8  150.49  5733.1  149.78
  6716.7  150.28  6791.7  151.88  6851.7  151.28  6881.7  152.58  7696.3  153.98
#Mann= 5 , 1 , 0
  2045.8     .99       0    3000      .1       0  4966.4    .048       0
  5026.8      .1       0  5519.8     .99       0
#XS Ineff= 2 , 0
       0    4964     149    5042       0   150.6
Permanent Ineff=
       F       F
Bank Sta=4966.4,5026.8
Exp/Cntr=0.5,0.3

Type RM Length L Ch R = 1 ,20771.1 ,453.9,627.8,685.2
BEGIN DESCRIPTION:
Cross Section 20771.1-Interpolated
END DESCRIPTION:
XS GIS Cut Line= 6
      2974201.07      13858277.9      2973843.13      13858061.8
       2972522.5     13857839.96      2971903.28     13857616.57
      2971795.33     13857601.57      2969805.21     13857518.45
#Sta/Elev= 30
  3027.8   151.8  3039.4   151.8  3351.2   149.6  3397.8   148.1  3445.9   150.6
  3481.1   150.6  3511.5   148.4  3572.2   150.2  3973.4   150.4  4058.3   149.3
    4119   150.3  4407.6     150    4438   147.9  4483.6   147.9  4497.6     149
  4961.5  148.94  4982.2  144.13  4992.8  143.71  4997.4  139.85  5000.1  139.22
  5002.9  139.95  5007.1  143.85  5012.8  145.31  5043.4  149.82  5061.3   151.8
  5094.1   149.4  5291.7   150.5  7276.3   151.1    7346  152.22  7544.7   152.3
#Mann= 5 , 1 , 0
  3027.8      .2       0  3039.4      .1       0  4961.5    .048       0
  5043.4     .07       0    7346      .2       0
#XS Ineff= 2 , 0
       0    4119   150.3  5061.3       0   151.8
Permanent Ineff=
       F       F
Bank Sta=4961.5,5043.4
Exp/Cntr=0.3,0.1

Type RM Length L Ch R = 1 ,20143.3 ,1309.7,1024.9,814.9
BEGIN DESCRIPTION:
Cross Section 20143.3
END DESCRIPTION:
XS GIS Cut Line= 6
      2974209.84     13858271.25      2973492.83     13857821.74
      2972781.36     13857275.44      2972408.69     13857127.22
      2971692.99     13857034.05      2970164.19     13856983.23
#Sta/Elev= 30
  3039.4   151.8  3134.4   151.4  3379.4   148.6  4006.1   149.4  4201.1   148.5
  4221.1   148.9  4241.1   148.3  4467.9   148.5  4747.9     148  4938.3  145.68
  4961.5  145.97  4982.2  141.16  4992.8  140.74  4997.4  136.88  5000.1  136.25
  5002.9  136.98  5007.1  140.88  5012.8  142.34  5043.4  146.85  5080.7  145.61
  5104.2  145.73  5185.4   147.7  5375.4   147.8  5405.4     149  6032.1   149.3
  6245.9     150  7170.9   150.4  7195.9   151.2    7346  151.14  7436.8   151.1
#Mann= 5 , 1 , 0
  3039.4      .2       0  3039.4      .1       0  4961.5    .048       0
  5043.4     .07       0    7346      .2       0
#XS Ineff= 2 , 0
       0  4006.1   149.4               0
Permanent Ineff=
       F       F
Bank Sta=4961.5,5043.4
Exp/Cntr=0.3,0.1

Type RM Length L Ch R = 1 ,19118.4 ,881.3,900.7,1002.5
BEGIN DESCRIPTION:
Cross Section 19118.4
END DESCRIPTION:
XS GIS Cut Line= 6
      2974765.65     13856153.46      2973823.15     13856314.12
      2972832.18     13856212.48      2972412.93     13856229.42
      2971430.43     13856356.46      2969767.83     13856347.72
#Sta/Elev= 30
  2949.6     151  3180.7  149.86  3287.3   147.1  3687.5  147.63    3759  145.45
  3819.8  147.12    4198  147.22    4300  149.72  4620.7  145.94  4710.9   146.9
  4921.5  145.04  4954.6  146.43  4968.5  144.59  4970.9  144.53  4978.5  142.01
    4992  139.87  4997.5  135.86  5003.4   135.6  5027.4   142.1  5047.5  145.78
  5078.9  146.82  5086.6   145.7  6093.7  147.83    6415  149.55  7210.1  150.14
  7240.1     149  7270.1  150.27  7450.9  149.84  7945.1  150.06  7975.1     151
#Mann= 6 , 1 , 0
  2949.6     .99       0    4300     .14       0  4968.5     .07       0
  4970.9    .048       0  5027.4     .07       0  7450.9      .2       0
#XS Ineff= 2 , 0
       0  4228.3  148.48               0
Permanent Ineff=
       F       F
Bank Sta=4970.9,5027.4
Exp/Cntr=0.3,0.1

Type RM Length L Ch R = 1 ,18217.7 ,471.2,441.7,241.2
BEGIN DESCRIPTION:
Cross Section 18217.7-Interpolated
END DESCRIPTION:
XS GIS Cut Line= 6
      2973897.13     13855303.69      2973574.61      13855364.7
      2972825.04     13855325.46      2972496.73     13855304.94
      2972111.19     13855258.68      2970704.42     13855138.18
#Sta/Elev= 30
  3891.7  155.29  3941.4  154.29  4102.8  146.95    4367  145.74  4652.3  147.29
  4697.4  146.19  4765.7  146.61  4817.6  149.52  4847.6  149.72  4877.6  147.79
  4952.8  145.37  4966.1  142.91  4985.4  138.78  4992.7  138.41  4996.9  135.55
  5003.7  135.03  5007.3  139.05    5027  143.01  5092.9  146.13  5163.2  144.01
  5304.8   144.3  5373.9  146.07  5507.2  145.76  5687.8  147.36  5826.7  146.92
  6575.5  148.43  6958.2  148.48  7013.6  149.25  7055.2  152.13  7099.7  152.53
#Mann= 4 , 1 , 0
  3891.7     .06       0  4966.1    .048       0    5027     .06       0
  6575.5      .2       0
#XS Ineff= 2 , 0
       0  4832.6  149.78               0
Permanent Ineff=
       F       F
Bank Sta=4966.1,5027
Exp/Cntr=0.3,0.1

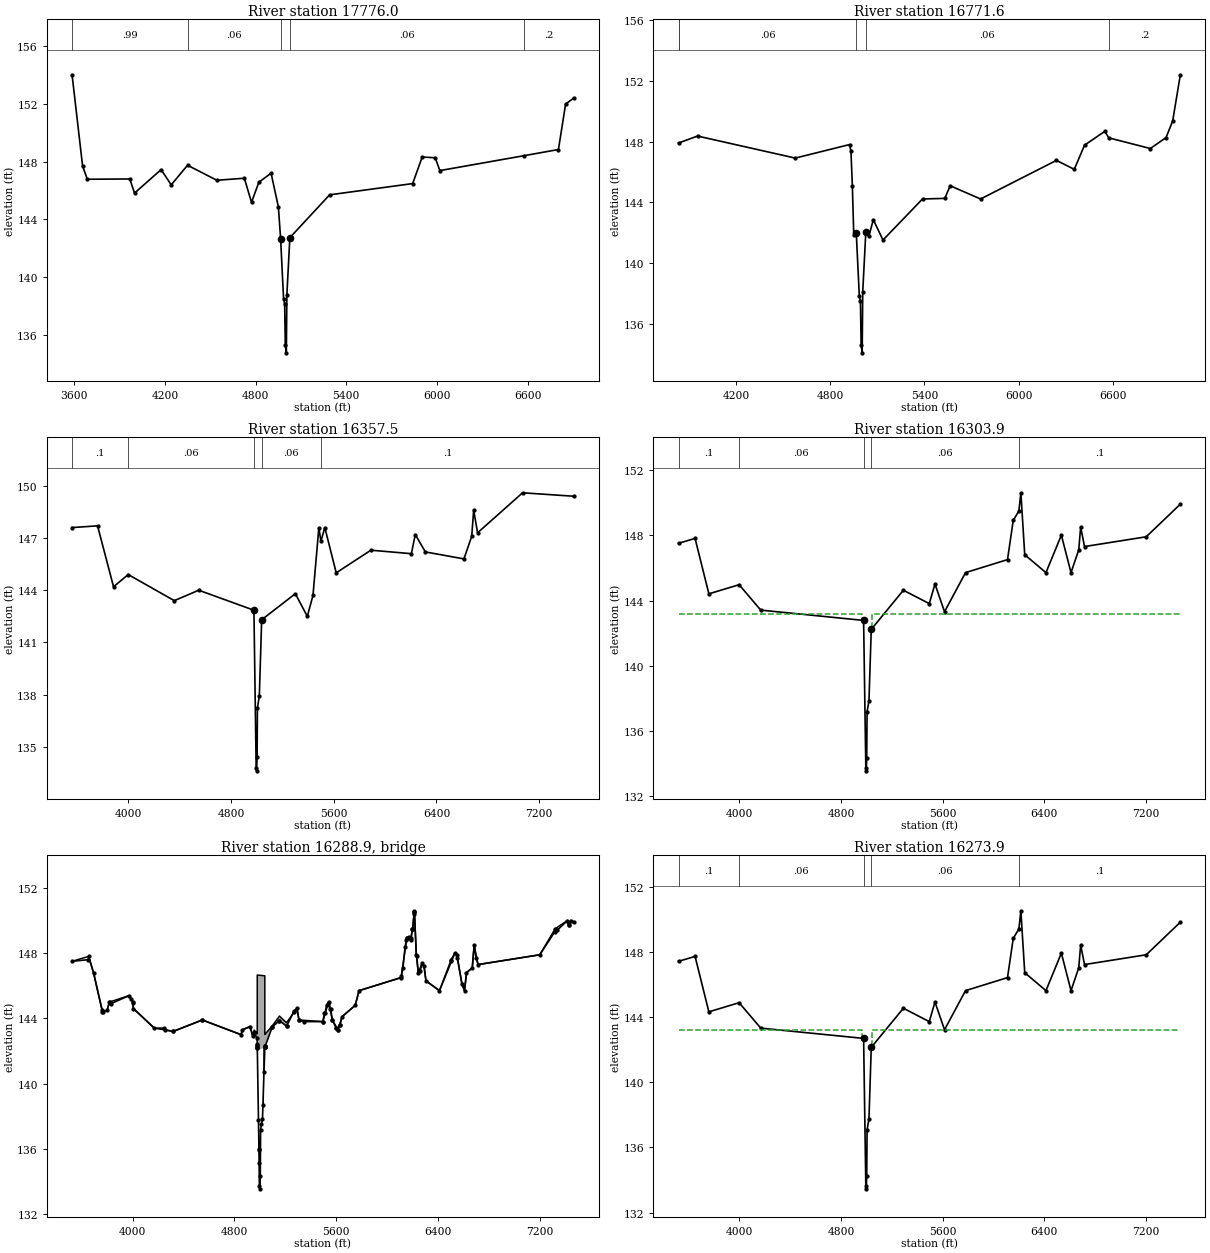
Type RM Length L Ch R = 1 ,17776.0 ,1032.4,1004.4,788.8
BEGIN DESCRIPTION:
Cross Section 17776.0-Interpolated
END DESCRIPTION:
XS GIS Cut Line= 6
      2973879.69     13855286.25      2973202.54     13854916.05
      2973084.95     13854921.92      2972893.44       13854833.
      2972295.51     13855043.95      2970711.81      13855127.1
#Sta/Elev= 30
  3585.6  154.02  3655.1  147.71  3686.4  146.78  3967.8   146.8  3999.1  145.82
  4175.2  147.45  4241.6  146.39    4350  147.75  4543.9  146.71    4726  146.85
  4773.2  145.18  4821.8  146.57  4902.7   147.2  4951.2  144.86  4966.1  142.63
  4985.4   138.5  4992.7  138.13  4996.9  135.27  5003.7  134.75  5007.3  138.77
    5027  142.73  5290.2   145.7  5839.9  146.48  5903.1  148.32  5989.6  148.27
  6019.7  147.38  6575.5  148.41  6804.7  148.84  6852.2  151.99  6906.8  152.41
#Mann= 5 , 1 , 0
  3585.6     .99       0    4350     .06       0  4966.1    .048       0
    5027     .06       0  6575.5      .2       0
#XS Ineff= 2 , 0
       0  4902.7   147.2               0
Permanent Ineff=
       F       F
Bank Sta=4966.1,5027
Exp/Cntr=0.3,0.1

Type RM Length L Ch R = 1 ,16771.6 ,328.3,414.1,666.9
BEGIN DESCRIPTION:
Cross Section 16771.6
END DESCRIPTION:
XS GIS Cut Line= 6
      2973518.24     13854010.32      2972777.13      13853946.8
      2972484.92     13853980.68      2972323.99     13854111.96
      2970956.31     13854763.84      2970699.17     13855116.21
#Sta/Elev= 30
  3833.3  147.91  3954.2  148.37  4577.1  146.92  4923.3  147.81  4932.2  147.37
  4941.2  145.06  4950.1  141.84  4966.1  141.99  4985.4  137.86  4992.7  137.49
  4996.9  134.63  5003.7  134.11  5007.3  138.13    5027  142.09  5047.4  141.82
  5074.6  142.87  5136.3  141.53  5388.2  144.23  5530.4  144.27  5564.6   145.1
  5758.2  144.23  6241.8  146.77  6355.4  146.18  6420.9  147.77  6550.2  148.68
  6575.5  148.25  6840.2  147.55  6940.5  148.27  6982.7  149.37  7031.3   152.4
#Mann= 5 , 1 , 0
  3833.3      .2       0  3833.3     .06       0  4966.1    .048       0
    5027     .06       0  6575.5      .2       0
Bank Sta=4966.1,5027
Exp/Cntr=0.3,0.1

Type RM Length L Ch R = 1 ,16357.5 ,52.9,53.6,46
BEGIN DESCRIPTION:
Cross Section 16357.5-Interpolated
END DESCRIPTION:
XS GIS Cut Line= 5
      2973582.07     13854022.65      2972666.26     13853656.81
      2971908.21     13853711.87      2971001.94     13853690.69
      2969761.11     13853872.79
#Sta/Elev= 30
  3562.7   147.6  3761.1   147.7  3885.5   144.2    4000   144.9  4358.8   143.4
  4548.9     144  4978.6  142.85    4996  133.81  4999.3  133.62  5003.2  134.42
  5005.9  137.24  5020.7  137.92  5038.8   142.3  5300.9   143.8  5394.4   142.5
  5438.4   143.7  5484.2   147.6    5500  146.81  5530.6   147.6  5619.4     145
  5889.5   146.3  6204.6   146.1  6234.8   147.2  6313.6   146.2  6613.8   145.8
  6674.4   147.1  6689.6   148.6  6719.9   147.3  7070.6   149.6  7469.6   149.4
#Mann= 5 , 1 , 0
  3562.7      .1       0    4000     .06       0  4978.6    .048       0
  5038.8     .06       0    5500      .1       0
Bank Sta=4978.6,5038.8
Exp/Cntr=0.5,0.3

Type RM Length L Ch R = 1 ,16303.9 ,30,30,30
BEGIN DESCRIPTION:
Upstream Section of Bridge/Culvert/Weir
END DESCRIPTION:
XS GIS Cut Line= 6
      2973599.93     13854012.43      2972672.38     13853600.86
      2971942.77     13853642.67      2971423.14     13853635.23
      2971002.73     13853631.78      2969756.68     13853810.67
#Sta/Elev= 30
  3523.8  147.51  3653.8  147.81  3762.2  144.41    4000  144.97  4170.2  143.41
  4978.6  142.78    4996  133.74  4999.3  133.55  5003.2  134.35  5005.9  137.17
  5020.7  137.85  5038.8  142.23  5291.3  144.63  5494.6  143.81  5539.7  145.01
  5614.7  143.31  5779.7  145.71  6109.8  146.51  6154.8  148.91  6199.5   149.5
  6214.8  150.61  6245.2  146.81  6411.9  145.71  6533.2  148.01    6609  145.71
  6669.7  147.11  6684.8  148.51  6715.1  147.31  7200.3  147.91  7468.3  149.91
#Mann= 5 , 1 , 0
  3523.8      .1       0    4000     .06       0  4978.6    .048       0
  5038.8     .06       0  6199.5      .1       0
#XS Ineff= 2 , 0
       0    4968   143.2    5048       0   143.2
Permanent Ineff=
       F       F
Bank Sta=4978.6,5038.8
Exp/Cntr=0.5,0.3

Type RM Length L Ch R = 3 ,16288.9 ,,,
BEGIN DESCRIPTION:
ACCESS ROAD
Structure ID: T00-11
END DESCRIPTION:
Bridge Culvert--1,0,-1,-1, 0
Deck Dist Width WeirC Skew NumUp NumDn MinLoCord MaxHiCord MaxSubmerge Is_Ogee
10,10,2.6,0, 60, 60, , , 0.95, 0, 1,1,,
  3523.8  3653.8  3692.5  3762.2  3799.2  3817.5  3973.3  3999.4  4006.1  4170.2
  4318.8  4547.6  4852.1  4863.4  4923.6  4943.1  4955.4  4978.6 4979.39  4979.5
  4989.2    5039 5039.11  5096.8  5153.7  5209.7  5291.3  5307.6  5494.6  5539.7
  5569.7  5614.7  5645.9  5749.7  5779.7  6109.8  6154.8  6184.8  6200.6  6214.8
    6230  6245.2  6275.5  6290.6  6305.8  6411.9  6533.2  6548.4  6588.7    6609
  6624.2  6669.7  6684.8  6715.1  7200.3  7321.6  7417.4  7427.7  7442.9  7468.3
   147.5   147.8   146.8   144.4   144.5     145   145.4     145   144.6   143.4
   143.2   143.9     143   143.3   143.5  142.93  143.28  143.07  143.06  146.66
  146.65  146.61  143.01  143.53  144.14  143.73  144.62   143.9   143.8     145
   143.9   143.3   144.1   144.8   145.7   146.5   148.9   148.8   149.5   150.6
   147.9   146.8   147.4   147.2   146.3   145.7     148   147.9   146.1   145.7
   146.8   147.1   148.5   147.3   147.9   149.5     150   149.7     150   149.9
   147.5   147.8   146.8   144.4   144.5     145   145.4     145   144.6   143.4
   143.2   143.9     143   143.3   143.5  142.93  143.11  142.77   142.4  142.34
  142.05  142.22  142.23  143.47  143.86  143.52  144.62   143.9   143.8     145
   143.9   143.3   144.1   144.8   145.7   146.5   148.9   148.8   149.5   150.6
   147.9   146.8   147.4   147.2   146.3   145.7     148   147.9   146.1   145.7
   146.8   147.1   148.5   147.3   147.9   149.5     150   149.7     150   149.9
  3523.8  3653.8  3692.5  3762.2  3799.2  3817.5  3973.3  3999.4  4006.1  4170.2
  4318.8  4547.6  4852.1  4863.4  4923.6  4943.1  4955.4  4978.6 4979.39  4979.5
  4989.2    5039 5039.11  5096.8  5153.7  5209.7  5291.3  5307.6  5494.6  5539.7
  5569.7  5614.7  5645.9  5749.7  5779.7  6109.8  6154.8  6184.8  6200.6  6214.8
    6230  6245.2  6275.5  6290.6  6305.8  6411.9  6533.2  6548.4  6588.7    6609
  6624.2  6669.7  6684.8  6715.1  7200.3  7321.6  7417.4  7427.7  7442.9  7468.3
   147.5   147.8   146.8   144.4   144.5     145   145.4     145   144.6   143.4
   143.2   143.9     143   143.3   143.5  142.93  143.28  143.07  143.06  146.66
  146.65  146.61  143.01  143.53  144.14  143.73  144.62   143.9   143.8     145
   143.9   143.3   144.1   144.8   145.7   146.5   148.9   148.8   149.5   150.6
   147.9   146.8   147.4   147.2   146.3   145.7     148   147.9   146.1   145.7
   146.8   147.1   148.5   147.3   147.9   149.5     150   149.7     150   149.9
  147.46  147.76  146.76  144.36  144.46  144.96  145.36  144.96  144.56  143.36
  143.16  143.86  142.96  143.26  143.46  142.89  143.07  142.73  142.36   142.3
  142.01  142.18  142.19  143.43  143.82  143.48  144.58  143.86  143.76  144.96
  143.86  143.26  144.06  144.76  145.66  146.46  148.86  148.76  149.46  150.56
  147.86  146.76  147.36  147.16  146.26  145.66  147.96  147.86  146.06  145.66
  146.76  147.06  148.46  147.26  147.86  149.46  149.96  149.66  149.96  149.86
Pier Skew, UpSta & Num, DnSta & Num=  ,5024, 2 ,5024, 2 , 0 , 0 , 0 ,,
     1.4     1.4
   137.5  143.02
     1.4     1.4
  137.46  142.98
Abutment Skew #Up #Dn= , 2 , 2
  4979.7    4993
  142.16  135.94
  4979.7    4993
  142.12   135.9
Abutment Skew #Up #Dn= , 2 , 2
  5032.4 5042.79
  140.69   142.3
  5032.4 5042.79
  140.65  142.26
BR Coef= 1 , 1 , 0 ,1.25, 0 ,,,0.8,0,2,0,
WSPro=,,,, 1 ,,,, 0 ,,,, 0 ,,,,-1 ,-1 ,-1 , 0 , 0 , 0 , 0 , 0
BR U #Sta/Elev= 133
  3523.8   147.5  3651.2   147.6  3653.8   147.8  3692.5   146.8  3760.7   144.5
  3762.2   144.4  3763.8   144.4  3799.2   144.5  3817.5     145  3825.6     145
  3828.9   144.9  3973.3   145.4  3988.8   145.2  3999.4     145    4000  144.96
  4006.1   144.6  4170.2   143.4  4249.5   143.4  4252.2   143.3  4317.7   143.2
  4318.8   143.2  4547.5   143.9  4547.6   143.9  4852.1     143  4863.4   143.3
  4923.6   143.5  4943.1  142.93  4954.7  143.12  4955.4  143.11  4978.6  142.77
 4979.39   142.4  4979.5  142.34 4979.61  142.29  4979.7  142.25 4979.81   142.2
  4979.9  142.16  4989.2  137.76  4992.9  135.99    4993  135.94    4994  135.14
    4996  133.73  4999.3  133.54  5003.2  134.34  5005.9  137.16  5012.4  137.49
  5020.7  137.84    5024  138.68  5032.4  140.69  5038.8  142.22 5038.89  142.22
    5039  142.22 5039.11  142.23 5042.59   142.3  5042.7   142.3  5042.8  142.31
  5096.8  143.47  5097.3  143.47  5153.7  143.86  5153.8  143.86  5209.7  143.52
  5211.3  143.54  5266.1   144.4  5268.1  144.43  5291.3  144.62  5307.6   143.9
  5307.7   143.9  5344.6   143.8  5492.7   143.8  5494.6   143.8  5507.6   144.3
  5511.6   144.3  5524.6   144.8  5537.7   144.9  5539.7     145  5553.7   144.6
  5555.5   144.6  5569.7   143.9  5570.2   143.9  5599.5   143.4  5599.7   143.4
  5612.7   143.3  5614.7   143.3  5628.8   143.6  5630.5   143.6  5645.9   144.1
  5749.7   144.8  5779.7   145.7  6109.8   146.5  6112.7   146.6  6124.8   147.1
    6142   148.4  6152.7   148.8  6154.8   148.9  6156.7   148.9  6169.8     149
  6184.8   148.8  6187.7   148.9  6199.5  149.49  6199.8   149.5  6200.6   149.5
  6214.1   150.5  6214.2   150.5  6214.8   150.6  6215.5   150.4    6230   147.9
  6233.3   147.8  6245.2   146.8  6260.3   146.9  6275.5   147.4  6290.6   147.2
  6305.8   146.3  6411.9   145.7  6499.8   147.5  6502.9   147.6  6533.2     148
  6548.4   147.9  6553.1   147.7  6588.7   146.1    6609   145.7  6624.2   146.8
  6669.7   147.1  6684.8   148.5    6700   147.7  6715.1   147.3  7200.3   147.9
  7317.2   149.3  7321.6   149.5  7336.7   149.4  7417.4     150  7427.7   149.7
  7430.6   149.7  7442.9     150  7468.3   149.9
BR U #Mann= 5
  3523.8      .1    4000     .06  4978.6    .048  5038.8     .06  6199.5      .1
BR U Banks=4978.6,5038.8
BR D #Sta/Elev= 133
  3523.8  147.46  3651.2  147.56  3653.8  147.76  3692.5  146.76  3760.7  144.46
  3762.2  144.36  3763.8  144.36  3799.2  144.46  3817.5  144.96  3825.6  144.96
  3828.9  144.86  3973.3  145.36  3988.8  145.16  3999.4  144.96    4000  144.92
  4006.1  144.56  4170.2  143.36  4249.5  143.36  4252.2  143.26  4317.7  143.16
  4318.8  143.16  4547.5  143.86  4547.6  143.86  4852.1  142.96  4863.4  143.26
  4923.6  143.46  4943.1  142.89  4954.7  143.08  4955.4  143.07  4978.6  142.73
 4979.39  142.36  4979.5   142.3 4979.61  142.25  4979.7  142.21 4979.81  142.16
  4979.9  142.12  4989.2  137.72  4992.9  135.95    4993   135.9    4994   135.1
    4996  133.69  4999.3   133.5  5003.2   134.3  5005.9  137.12  5012.4  137.45
  5020.7   137.8    5024  138.64  5032.4  140.65  5038.8  142.18 5038.89  142.18
    5039  142.18 5039.11  142.19 5042.59  142.26  5042.7  142.26  5042.8  142.27
  5096.8  143.43  5097.3  143.43  5153.7  143.82  5153.8  143.82  5209.7  143.48
  5211.3   143.5  5266.1  144.36  5268.1  144.39  5291.3  144.58  5307.6  143.86
  5307.7  143.86  5344.6  143.76  5492.7  143.76  5494.6  143.76  5507.6  144.26
  5511.6  144.26  5524.6  144.76  5537.7  144.86  5539.7  144.96  5553.7  144.56
  5555.5  144.56  5569.7  143.86  5570.2  143.86  5599.5  143.36  5599.7  143.36
  5612.7  143.26  5614.7  143.26  5628.8  143.56  5630.5  143.56  5645.9  144.06
  5749.7  144.76  5779.7  145.66  6109.8  146.46  6112.7  146.56  6124.8  147.06
    6142  148.36  6152.7  148.76  6154.8  148.86  6156.7  148.86  6169.8  148.96
  6184.8  148.76  6187.7  148.86  6199.5  149.45  6199.8  149.46  6200.6  149.46
  6214.1  150.46  6214.2  150.46  6214.8  150.56  6215.5  150.36    6230  147.86
  6233.3  147.76  6245.2  146.76  6260.3  146.86  6275.5  147.36  6290.6  147.16
  6305.8  146.26  6411.9  145.66  6499.8  147.46  6502.9  147.56  6533.2  147.96
  6548.4  147.86  6553.1  147.66  6588.7  146.06    6609  145.66  6624.2  146.76
  6669.7  147.06  6684.8  148.46    6700  147.66  6715.1  147.26  7200.3  147.86
  7317.2  149.26  7321.6  149.46  7336.7  149.36  7417.4  149.96  7427.7  149.66
  7430.6  149.66  7442.9  149.96  7468.3  149.86
BR D #Mann= 5
  3523.8      .1    4000     .06  4978.6    .048  5038.8     .06  6199.5      .1
BR D Banks=4978.6,5038.8
BC Design=,, 0 ,, 0 ,,,,,,
BC HTab HWMax=150.61

Type RM Length L Ch R = 1 ,16273.9 ,241.4,241.4,241.4
BEGIN DESCRIPTION:
Downstream Section of Bridge/Culvert/Weir
END DESCRIPTION:
XS GIS Cut Line= 6
       2973593.5     13853983.13      2972665.94     13853571.56
      2971936.33     13853613.37       2971416.7     13853605.93
      2970996.29     13853602.48      2969750.25     13853781.36
#Sta/Elev= 30
  3523.8  147.42  3653.8  147.72  3762.2  144.32    4000  144.88  4170.2  143.32
  4978.6  142.69    4996  133.65  4999.3  133.46  5003.2  134.26  5005.9  137.08
  5020.7  137.76  5038.8  142.14  5291.3  144.54  5494.6  143.72  5539.7  144.92
  5614.7  143.22  5779.7  145.62  6109.8  146.42  6154.8  148.82  6199.5  149.41
  6214.8  150.52  6245.2  146.72  6411.9  145.62  6533.2  147.92    6609  145.62
  6669.7  147.02  6684.8  148.42  6715.1  147.22  7200.3  147.82  7468.3  149.82
#Mann= 5 , 1 , 0
  3523.8      .1       0    4000     .06       0  4978.6    .048       0
  5038.8     .06       0  6199.5      .1       0
#XS Ineff= 2 , 0
       0    4968   143.2    5048       0   143.2
Permanent Ineff=
       F       F
Bank Sta=4978.6,5038.8
Exp/Cntr=0.5,0.3

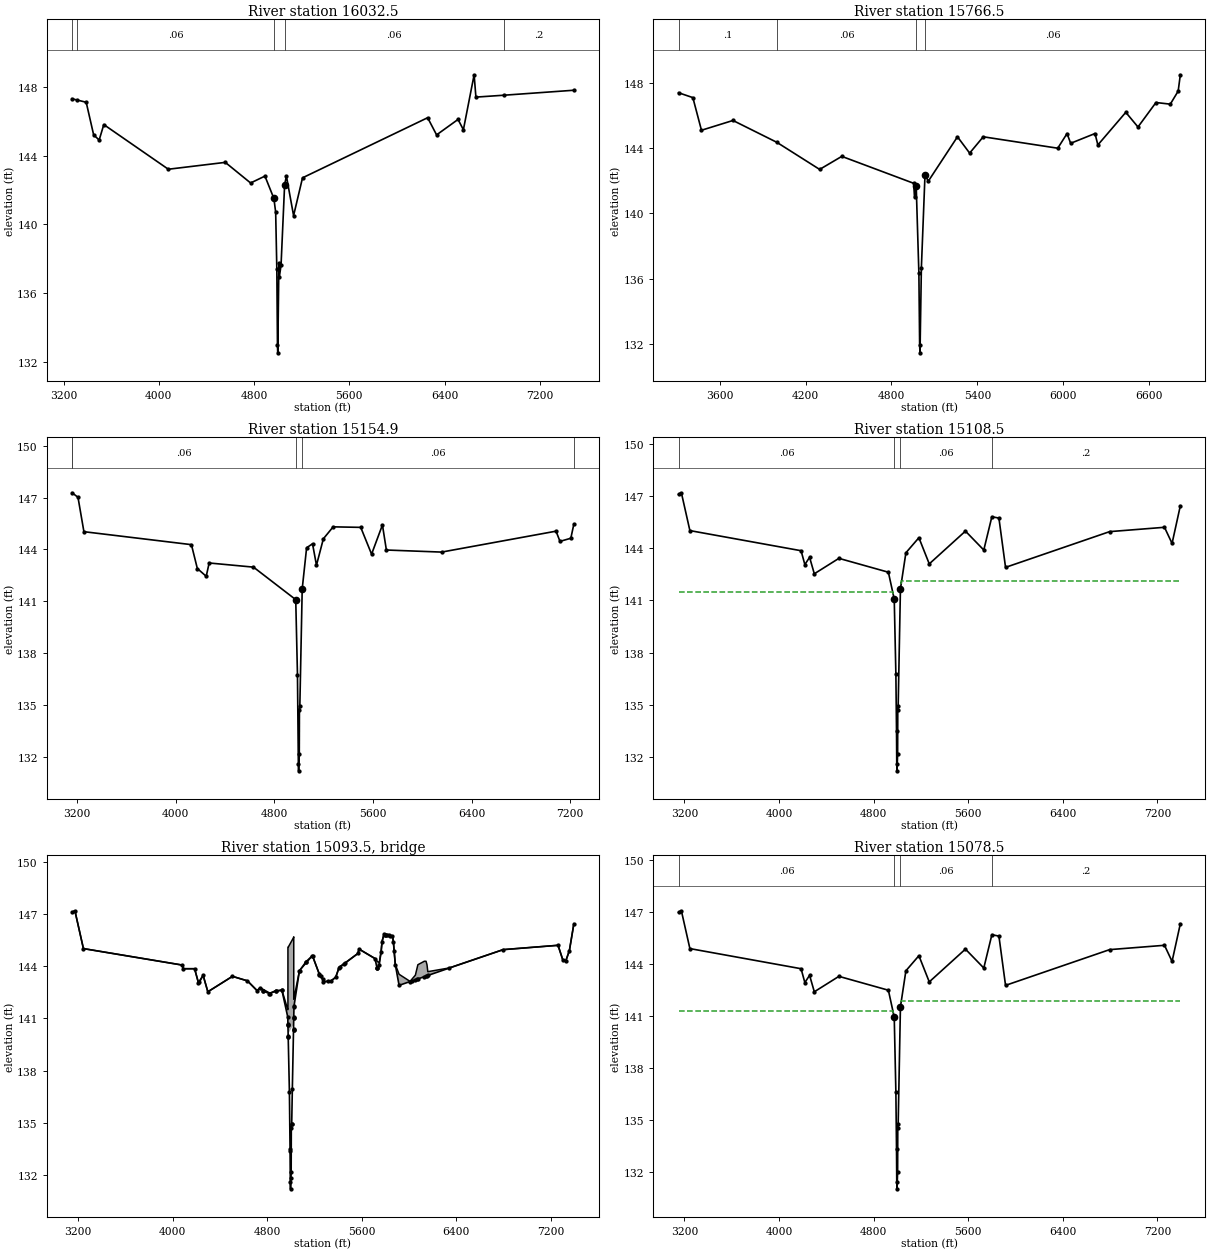
Type RM Length L Ch R = 1 ,16032.5 ,49.6,266,446.2
BEGIN DESCRIPTION:
Cross Section 16032.5-Interpolated
END DESCRIPTION:
XS GIS Cut Line= 6
      2973747.58     13854019.78      2972618.27      13853403.4
      2972381.16     13853365.28      2972265.65     13853364.79
      2972049.29     13853380.99      2969695.86      13853485.3
#Sta/Elev= 30
  3271.3   147.3  3313.6  147.23    3390   147.1  3452.6   145.2  3498.9   144.9
  3537.8   145.8  4079.9   143.2  4558.3   143.6    4771   142.4  4891.4   142.8
  4966.5   141.5  4981.5   140.7  4991.3  137.38  4996.6  132.96  4999.2  132.51
  5008.7  137.73  5011.6   136.9  5026.6   137.6  5056.7   142.3  5071.8   142.8
    5132   140.5  5207.1   142.7  6258.1   146.2  6333.2   145.2  6513.4   146.1
  6558.4   145.5  6648.5   148.7  6663.5   147.4  6899.2  147.51  7486.3   147.8
#Mann= 5 , 1 , 0
  3271.3      .2       0  3313.6     .06       0  4966.5    .048       0
  5056.7     .06       0  6899.2      .2       0
Bank Sta=4966.5,5056.7
Exp/Cntr=0.3,0.1

Type RM Length L Ch R = 1 ,15766.5 ,608.3,611.6,992.4
BEGIN DESCRIPTION:
Cross Section 15766.5
END DESCRIPTION:
XS GIS Cut Line= 6
      2973772.33     13854012.86      2972783.06     13853447.08
      2972373.12     13853196.37      2972217.27     13853084.57
      2970733.36     13852752.56      2970563.41     13852756.06
#Sta/Elev= 30
  3313.6   147.4  3413.6   147.1  3473.6   145.1  3693.6   145.7    4000  144.36
  4298.6   142.7  4453.2   143.5  4954.9  141.85  4960.7     141  4972.7  141.66
  4991.3  136.33  4996.6  131.91  4999.2  131.46  5008.7  136.68    5034  142.38
  5057.1  141.98  5260.6   144.7  5345.6   143.7  5440.6   144.7  5960.6     144
  6025.6   144.9  6050.6   144.3  6220.6   144.9  6240.6   144.2  6435.6   146.2
  6520.6   145.3  6646.2   146.8  6746.2   146.7  6801.2   147.5  6816.2   148.5
#Mann= 4 , 1 , 0
  3313.6      .1       0    4000     .06       0  4972.7    .048       0
    5034     .06       0
Bank Sta=4972.7,5034
Exp/Cntr=0.3,0.1

Type RM Length L Ch R = 1 ,15154.9 ,46.4,46.4,46.4
BEGIN DESCRIPTION:
Cross Section 15154.9-Interpolated
END DESCRIPTION:
XS GIS Cut Line= 6
      2973797.84     13853993.15      2972627.98     13853100.76
       2972834.9     13852578.54      2972814.42     13852501.75
      2972599.42     13852440.32       2970870.9     13852417.21
#Sta/Elev= 30
  3160.3  147.28  3208.3  147.02  3256.3  145.03  4128.3  144.28  4176.3   142.9
  4248.3  142.45  4272.3  143.22  4631.7  142.98  4974.4   141.1  4988.4  136.77
  4995.7  131.58  4997.7   131.2  5003.1  132.17  5004.3  134.69  5007.7  134.95
  5026.9  141.72  5062.6   144.1  5110.6  144.33  5142.6  143.09  5198.5  144.62
    5278  145.31  5501.6  145.28  5589.6  143.73  5677.6  145.42  5709.6  143.97
  6157.6  143.85  7085.6  145.06  7117.6  144.47  7205.6  144.65  7230.2  145.47
#Mann= 5 , 1 , 0
  3160.3      .2       0  3160.3     .06       0  4974.4    .048       0
  5026.9     .06       0  7230.2      .2       0
#XS Ineff= 2 , 0
       0                    5278       0  145.31
Permanent Ineff=
       F       F
Bank Sta=4974.4,5026.9
Exp/Cntr=0.5,0.3

Type RM Length L Ch R = 1 ,15108.5 ,30,30,30
BEGIN DESCRIPTION:
Upstream Section of Bridge/Culvert/Weir
END DESCRIPTION:
XS GIS Cut Line= 6
      2973918.73     13853979.61      2972697.73     13853074.35
      2972925.14     13852554.97      2972850.42      13852377.4
      2971720.53     13852261.06      2970938.47     13852341.72
#Sta/Elev= 30
  3150.5  147.12  3174.5  147.21  3246.5  145.03  4186.6  143.87  4218.6  143.07
  4258.6  143.49  4298.6  142.54  4506.6  143.43  4924.9  142.63  4974.4  141.08
  4988.3  136.75  4993.7  133.46  4995.7  131.56  4997.7  131.18  5003.1  132.15
  5004.3  134.67  5007.7  134.93  5026.8  141.67    5073  143.75  5182.9  144.62
  5270.6  143.11  5576.4     145  5731.6  143.91    5800  145.83  5859.6  145.75
  5915.6  142.91  6795.6  144.97  7259.6  145.22  7323.6  144.29  7393.5  146.46
#Mann= 4 , 1 , 0
  3150.5     .06       0  4974.4    .048       0  5026.8     .06       0
    5800      .2       0
#XS Ineff= 2 , 0
       0    4968   141.5    5033       0   142.1
Permanent Ineff=
       F       F
Bank Sta=4974.4,5026.8
Exp/Cntr=0.5,0.3

Type RM Length L Ch R = 3 ,15093.5 ,,,
BEGIN DESCRIPTION:
ACCESS ROAD
Structure ID: T00-10
END DESCRIPTION:
Bridge Culvert--1,0,-1,-1, 0
Deck Dist Width WeirC Skew NumUp NumDn MinLoCord MaxHiCord MaxSubmerge Is_Ogee
10,10,2.6,0, 60, 60, , , 0.95, 0, 1,1,,
  3150.5  3174.5  3246.5  4082.6  4090.6  4186.6  4218.6  4258.6  4298.6  4506.6
  4633.4  4714.5  4742.6  4821.2  4924.9  4974.4 4975.69  4975.8 4978.01  4978.1
 5022.89    5023 5024.89    5025 5025.11  5026.9    5073  5182.9  5242.4  5270.4
  5270.6  5340.3  5380.3  5408.4  5568.4  5576.4  5712.4  5731.6  5747.6  5763.6
  5771.6  5787.6  5859.6  5867.6  5883.6  5915.6  6008.5  6053.5  6074.5  6128.8
  6143.6  6151.7  6158.6  6336.7  6795.6  7259.6  7299.6  7323.6  7355.6  7393.5
  147.12  147.21  145.03  144.08  143.87  143.87  143.07  143.49  142.54  143.43
  143.17  142.61  142.77  142.47  142.64  141.51  141.51  145.11  145.11  145.11
  145.66  145.66  145.71  145.71  142.11  142.15  143.76  144.62  143.54  143.27
  143.12  143.17  143.39  143.95  144.76  145.01  144.46  144.29  144.22  144.85
  145.44  145.86  145.76  145.41  144.12  143.55  143.14   143.5   144.1   144.3
   144.3   144.1   143.7  143.91  144.97  145.22  144.39  144.29  144.91  146.46
  147.12  147.21  145.03  144.08  143.87  143.87  143.07  143.49  142.54  143.43
  143.17  142.61  142.77  142.44  142.63  141.08  140.68  140.64  139.96  140.11
  140.66  140.36  141.01  141.05  141.09   141.7  143.75  144.62  143.53  143.26
  143.11  143.16  143.38  143.94  144.75     145  144.45  143.91   144.1  144.84
  145.43  145.85  145.75   145.4  144.11  142.91  143.13  143.23  143.28  143.41
  143.44  143.46  143.48   143.9  144.97  145.22  144.39  144.29  144.91  146.46
  3150.5  3174.5  3246.5  4082.6  4090.6  4186.6  4218.6  4258.6  4298.6  4506.6
  4633.4  4714.5  4742.6  4821.2  4924.9  4974.4 4975.69  4975.8 4978.01  4978.1
 5022.89    5023 5024.89    5025 5025.11  5026.9    5073  5182.9  5242.4  5270.4
  5270.6  5340.3  5380.3  5408.4  5568.4  5576.4  5712.4  5731.6  5747.6  5763.6
  5771.6  5787.6  5859.6  5867.6  5883.6  5915.6  6008.5  6053.5  6074.5  6128.8
  6143.6  6151.7  6158.6  6336.7  6795.6  7259.6  7299.6  7323.6  7355.6  7393.5
  147.12  147.21  145.03  144.08  143.87  143.87  143.07  143.49  142.54  143.43
  143.17  142.61  142.77  142.47  142.64  141.51  141.51  145.11  145.11  145.11
  145.66  145.66  145.71  145.71  142.11  142.15  143.76  144.62  143.54  143.27
  143.12  143.17  143.39  143.95  144.76  145.01  144.46  144.29  144.22  144.85
  145.44  145.86  145.76  145.41  144.12  143.55  143.14   143.5   144.1   144.3
   144.3   144.1   143.7  143.91  144.97  145.22  144.39  144.29  144.91  146.46
  147.02  147.11  144.93  143.98  143.77  143.77  142.97  143.39  142.44  143.33
  143.07  142.51  142.67  142.34  142.53  140.98  140.58  140.54  139.86  140.01
  140.56  140.26  140.91  140.95  140.99   141.6  143.65  144.52  143.43  143.16
  143.01  143.06  143.28  143.84  144.65   144.9  144.35  143.81     144  144.74
  145.33  145.75  145.65   145.3  144.01  142.81  143.03  143.13  143.18  143.31
  143.34  143.36  143.38   143.8  144.87  145.12  144.29  144.19  144.81  146.36
Abutment Skew #Up #Dn= , 2 , 2
  4977.9  4993.8
  140.11  133.36
  4977.9  4993.8
  140.01  133.26
Abutment Skew #Up #Dn= , 2 , 2
  5007.7 5023.09
  134.93  140.66
  5007.7 5023.09
  134.83  140.56
BR Coef= 1 , 1 , 0 ,1.25, 0 ,,,0.8,0,2,0,
WSPro=,,,, 1 ,,,, 0 ,,,, 0 ,,,,-1 ,-1 ,-1 , 0 , 0 , 0 , 0 , 0
BR U #Sta/Elev= 103
  3150.5  147.12  3174.5  147.21  3246.5  145.03  4082.6  144.08  4090.6  143.87
  4186.6  143.87  4218.6  143.07  4226.6  143.09  4258.6  143.49  4298.6  142.54
  4506.6  143.43  4633.4  143.17  4714.5  142.61  4742.6  142.77  4764.7  142.59
  4765.8  142.58  4819.9  142.44  4821.2  142.44  4872.3  142.61  4874.5  142.61
  4923.9  142.63  4924.9  142.63  4974.4  141.08 4975.69  140.68  4975.8  140.64
 4975.91  140.61  4977.9  139.99 4978.01  139.96  4978.1  139.93  4988.3  136.75
  4993.7  133.46  4993.8  133.36  4995.7  131.56  4997.7  131.18  5000.7  131.81
  5003.1  132.15  5004.3  134.67  5007.6  134.92  5007.7  134.93  5013.1  136.96
 5022.89  140.32    5023  140.36  5023.1  140.39 5024.89  141.01    5025  141.05
 5025.11  141.09  5026.8  141.67  5026.9   141.7    5073  143.75  5074.5  143.76
  5125.2  144.24  5128.2  144.27  5182.9  144.62  5185.3  144.58  5240.2  143.57
  5242.4  143.53  5252.5  143.43  5270.4  143.26  5270.6  143.11    5315  143.14
  5340.3  143.16  5380.3  143.38  5408.4  143.94  5415.7  143.98  5453.2  144.17
  5460.5   144.2  5568.4  144.75  5576.4     145  5712.4  144.45  5728.4  143.92
  5729.7  143.92  5731.6  143.91  5747.6   144.1  5763.6  144.84  5771.6  145.43
  5787.6  145.85  5798.5  145.83    5800  145.83  5806.3  145.82  5813.5  145.81
  5828.5  145.79  5836.4  145.78  5859.6  145.75  5867.6   145.4  5873.5  144.92
  5883.6  144.11  5915.6  142.91  6008.5  143.13  6023.5  143.16  6053.5  143.23
  6068.5  143.27  6074.5  143.28  6128.8  143.41  6143.6  143.44  6151.7  143.46
  6158.6  143.48  6336.7   143.9  6795.6  144.97  7259.6  145.22  7299.6  144.39
  7323.6  144.29  7355.6  144.91  7393.5  146.46
BR U #Mann= 4
  3150.5     .06  4974.4    .048  5026.8     .06    5800      .2
BR U Banks=4974.4,5026.8
BR D #Sta/Elev= 103
  3150.5  147.02  3174.5  147.11  3246.5  144.93  4082.6  143.98  4090.6  143.77
  4186.6  143.77  4218.6  142.97  4226.6  142.99  4258.6  143.39  4298.6  142.44
  4506.6  143.33  4633.4  143.07  4714.5  142.51  4742.6  142.67  4764.7  142.49
  4765.8  142.48  4819.9  142.34  4821.2  142.34  4872.3  142.51  4874.5  142.51
  4923.9  142.53  4924.9  142.53  4974.4  140.98 4975.69  140.58  4975.8  140.54
 4975.91  140.51  4977.9  139.89 4978.01  139.86  4978.1  139.83  4988.3  136.65
  4993.7  133.36  4993.8  133.26  4995.7  131.46  4997.7  131.08  5000.7  131.71
  5003.1  132.05  5004.3  134.57  5007.6  134.82  5007.7  134.83  5013.1  136.86
 5022.89  140.22    5023  140.26  5023.1  140.29 5024.89  140.91    5025  140.95
 5025.11  140.99  5026.8  141.57  5026.9   141.6    5073  143.65  5074.5  143.66
  5125.2  144.14  5128.2  144.17  5182.9  144.52  5185.3  144.48  5240.2  143.47
  5242.4  143.43  5252.5  143.33  5270.4  143.16  5270.6  143.01    5315  143.04
  5340.3  143.06  5380.3  143.28  5408.4  143.84  5415.7  143.88  5453.2  144.07
  5460.5   144.1  5568.4  144.65  5576.4   144.9  5712.4  144.35  5728.4  143.82
  5729.7  143.82  5731.6  143.81  5747.6     144  5763.6  144.74  5771.6  145.33
  5787.6  145.75  5798.5  145.73    5800  145.73  5806.3  145.72  5813.5  145.71
  5828.5  145.69  5836.4  145.68  5859.6  145.65  5867.6   145.3  5873.5  144.82
  5883.6  144.01  5915.6  142.81  6008.5  143.03  6023.5  143.06  6053.5  143.13
  6068.5  143.17  6074.5  143.18  6128.8  143.31  6143.6  143.34  6151.7  143.36
  6158.6  143.38  6336.7   143.8  6795.6  144.87  7259.6  145.12  7299.6  144.29
  7323.6  144.19  7355.6  144.81  7393.5  146.36
BR D #Mann= 4
  3150.5     .06  4974.4    .048  5026.8     .06    5800      .2
BR D Banks=4974.4,5026.8
BC Design=,, 0 ,, 0 ,,,,,,
BC HTab HWMax=147.21

Type RM Length L Ch R = 1 ,15078.5 ,389.9,389.9,389.9
BEGIN DESCRIPTION:
Downstream Section of Bridge/Culvert/Weir
END DESCRIPTION:
XS GIS Cut Line= 6
      2973947.22       13853989.      2972726.23     13853083.73
      2972953.64     13852564.35      2972878.92     13852386.78
      2971749.03     13852270.44      2970966.96     13852351.11
#Sta/Elev= 30
  3150.5  146.99  3174.5  147.08  3246.5   144.9  4186.6  143.74  4218.6  142.94
  4258.6  143.36  4298.6  142.41  4506.6   143.3  4924.9   142.5  4974.4  140.95
  4988.3  136.62  4993.7  133.33  4995.7  131.43  4997.7  131.05  5003.1  132.02
  5004.3  134.54  5007.7   134.8  5026.8  141.54    5073  143.62  5182.9  144.49
  5270.6  142.98  5576.4  144.87  5731.6  143.78    5800   145.7  5859.6  145.62
  5915.6  142.78  6795.6  144.84  7259.6  145.09  7323.6  144.16  7393.5  146.33
#Mann= 4 , 1 , 0
  3150.5     .06       0  4974.4    .048       0  5026.8     .06       0
    5800      .2       0
#XS Ineff= 2 , 0
       0    4968   141.3    5033       0   141.9
Permanent Ineff=
       F       F
Bank Sta=4974.4,5026.8
Exp/Cntr=0.5,0.3