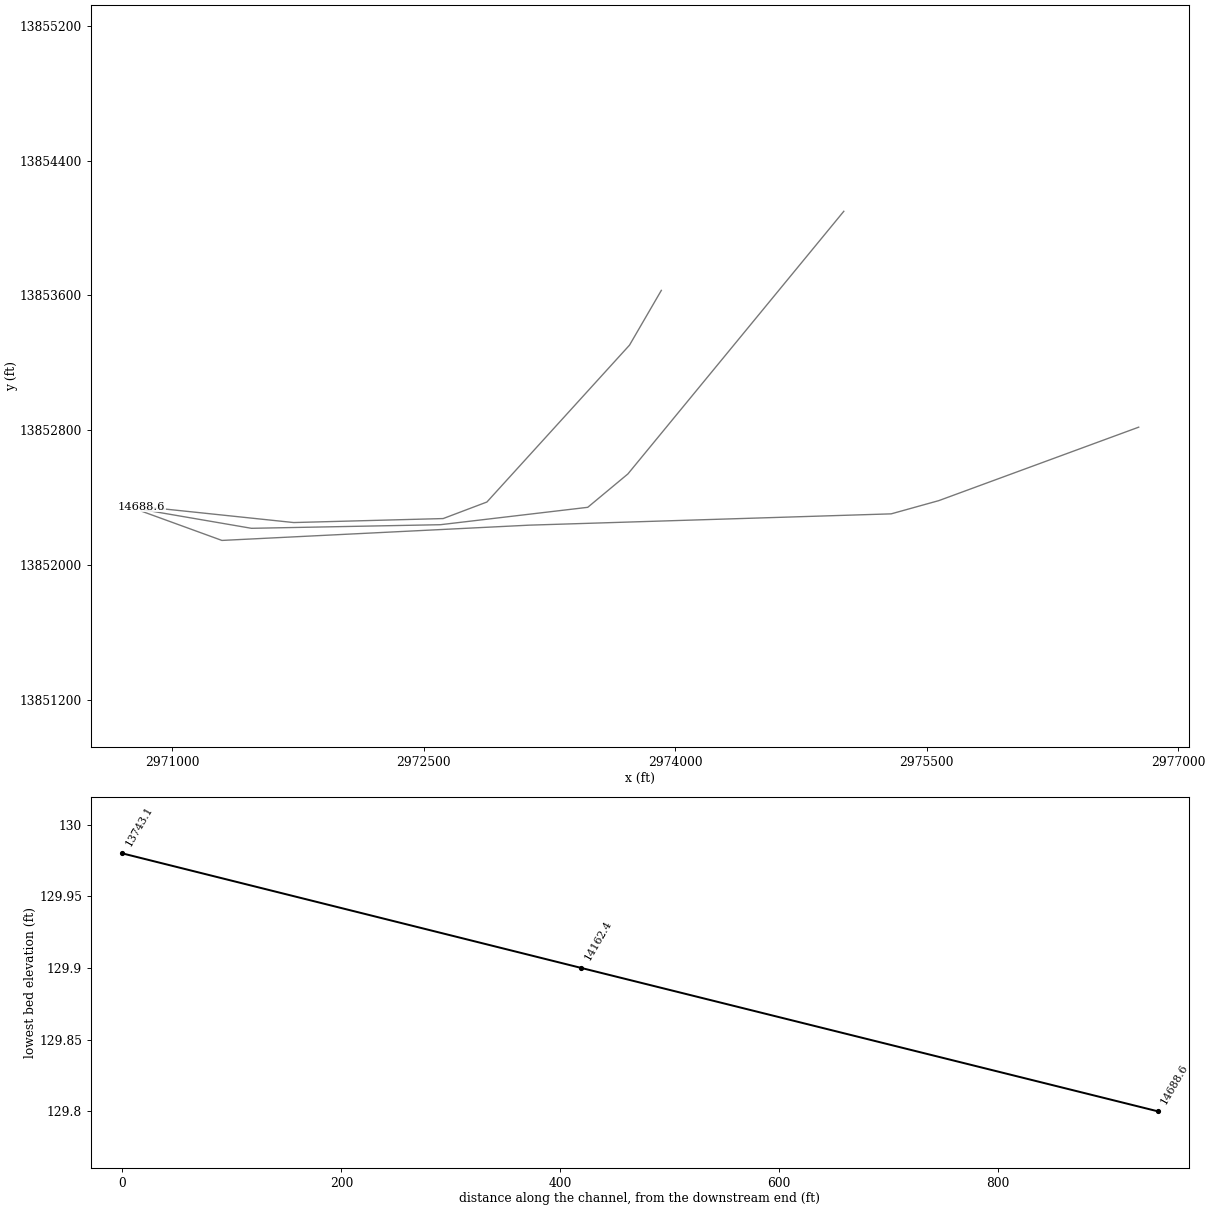
HEC-RAS study T100-00-00.PRJ: T100-00-00

--- T100-00-00.g01 (geometry) --- (continued)

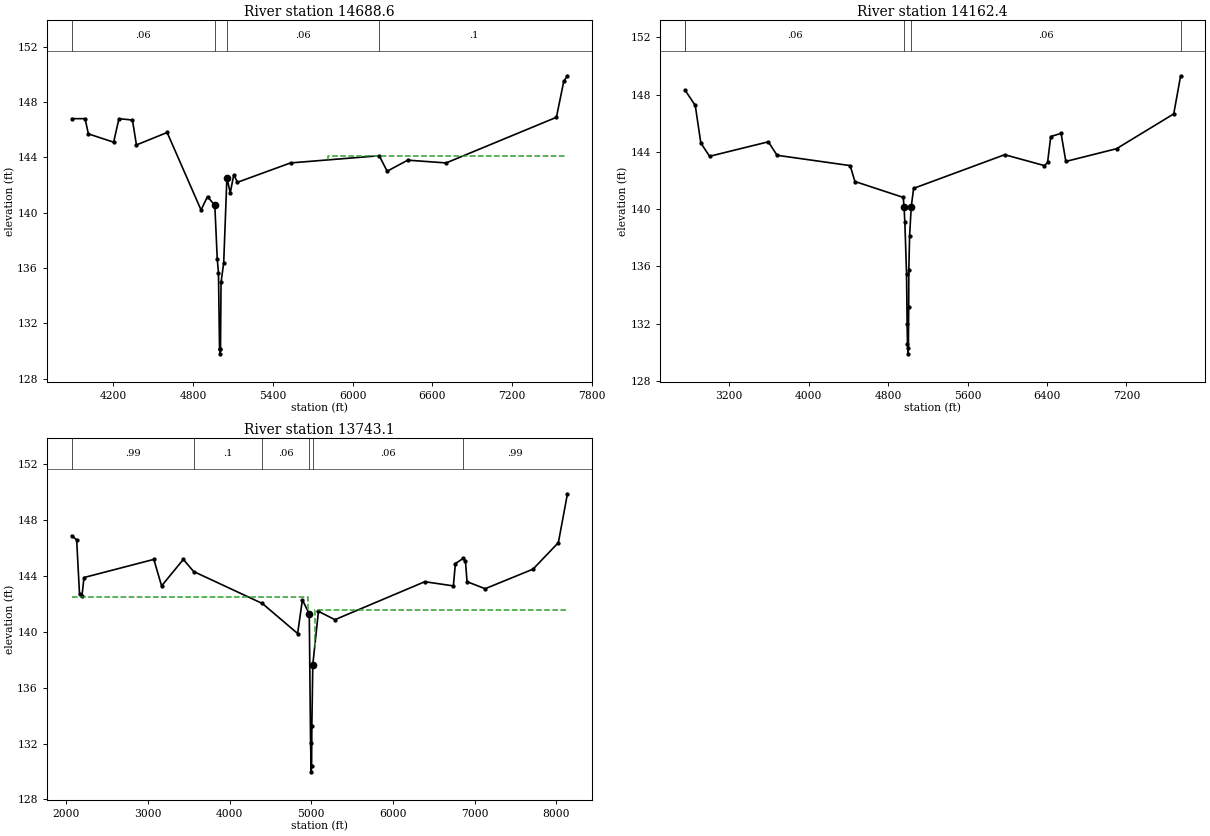
Type RM Length L Ch R = 1 ,14688.6 ,919.9,526.2,329
BEGIN DESCRIPTION:
Cross Section 14688.6
END DESCRIPTION:
XS GIS Cut Line= 6
      2973918.07     13853630.07      2973728.29     13853304.79
      2972877.92     13852373.11      2972617.05     13852274.86
      2971726.02     13852251.14      2970818.06       13852346.
#Sta/Elev= 30
  3886.6   146.8  3986.6   146.8  4011.6   145.7  4201.6   145.1  4241.6   146.8
  4343.2   146.7  4373.2   144.9  4604.2   145.8  4859.2   140.2  4907.9  141.17
  4962.9  140.53  4981.1  136.68  4990.3  135.65  4998.4  130.18  5002.5   129.8
  5005.6  130.12  5009.7  134.96  5029.8  136.39  5053.8  142.54  5078.9  141.44
  5105.8  142.75    5133   142.2  5532.4   143.6    6200  144.12  6259.4     143
  6414.4   143.8  6703.2   143.6  7533.2   146.9  7588.2   149.5  7616.1   149.9
#Mann= 4 , 1 , 0
  3886.6     .06       0  4962.9    .048       0  5053.8     .06       0
    6200      .1       0
#XS Ineff= 2 , 0
       0                  5811.2       0   144.1
Permanent Ineff=
       F       F
Bank Sta=4962.9,5053.8
Exp/Cntr=0.3,0.1

Type RM Length L Ch R = 1 ,14162.4 ,419.3,419.3,419.3
BEGIN DESCRIPTION:
Cross Section 14162.4-Interpolated
END DESCRIPTION:
XS GIS Cut Line= 6
      2975006.23      13854099.8      2973718.55     13852539.73
      2973479.18     13852341.62       2972600.4     13852238.35
      2971473.87     13852216.94      2970837.68     13852325.81
#Sta/Elev= 30
  2753.7  148.32  2857.7  147.24  2913.7  144.62  3001.7  143.69  3593.7   144.7
  3681.7  143.76  4417.7  143.04  4465.7  141.93  4952.6  140.82  4960.6  140.13
  4968.6   139.1  4985.7  135.49  4991.5  131.99  4995.1  130.61  4999.7   129.9
  5004.2  130.29  5007.4   133.2  5008.6  135.74  5016.6  138.14  5032.6  140.13
  5056.6  141.45  5974.1   143.8  6374.1  143.04  6406.1  143.26  6438.1  145.07
  6542.1  145.29  6590.1  143.33  7100.8  144.22  7676.8  146.65  7746.2  149.31
#Mann= 5 , 1 , 0
  2753.7      .2       0  2753.7     .06       0  4960.6    .045       0
  5032.6     .06       0  7746.2      .2       0
#XS Ineff= 2 , 0
       0  3593.7   144.7  5974.1       0   143.8
Permanent Ineff=
       F       F
Bank Sta=4960.6,5032.6
Exp/Cntr=0.5,0.3

Type RM Length L Ch R = 1 ,13743.1 ,58,58,58
BEGIN DESCRIPTION:
Upstream Section of Bridge/Culvert/Weir
END DESCRIPTION:
XS GIS Cut Line= 6
      2976764.65     13852817.62      2975572.72     13852381.37
      2975288.65     13852302.81      2973130.56     13852235.69
      2971297.85     13852144.96       2970816.9     13852319.14
#Sta/Elev= 30
    2067   146.9    2127   146.6    2162   142.7    2192   142.6    2217   143.9
    3072   145.2    3167   143.3  3433.4   145.2  3559.8  144.33  4401.1  142.04
  4833.2  139.89  4891.4   142.3  4975.6  141.29  4991.5  132.07  4999.6  129.98
  5004.2  130.37  5007.4  133.28  5018.9  137.66  5087.9  141.48  5289.6  140.88
  6390.3   143.6  6740.3   143.3  6765.3   144.9    6860  145.27    6888   145.1
    6908   143.6  7129.6   143.1  7716.1   144.5  8026.1   146.4  8137.6   149.9
#Mann= 6 , 1 , 0
    2067     .99       0  3559.8      .1       0  4401.1     .06       0
  4975.6    .045       0  5018.9     .06       0    6860     .99       0
#XS Ineff= 2 , 0
       0    4962   142.5    5040       0   141.6
Permanent Ineff=
       F       F
Bank Sta=4975.6,5018.9
Exp/Cntr=0.5,0.3