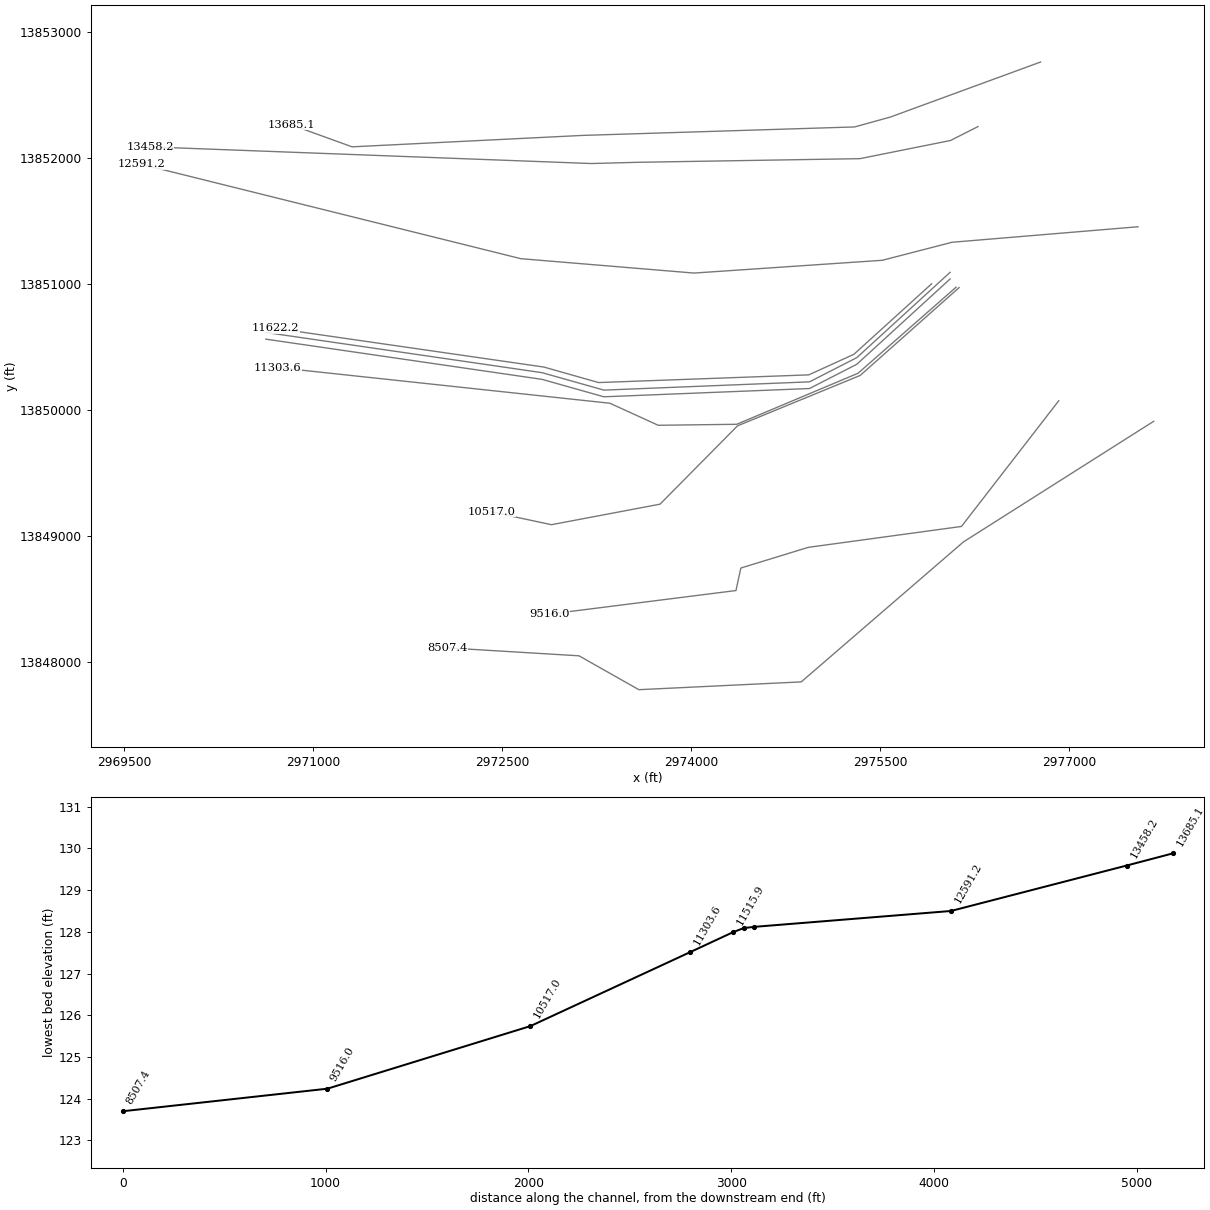
HEC-RAS study T100-00-00.PRJ: T100-00-00

--- T100-00-00.g01 (geometry) --- (continued)

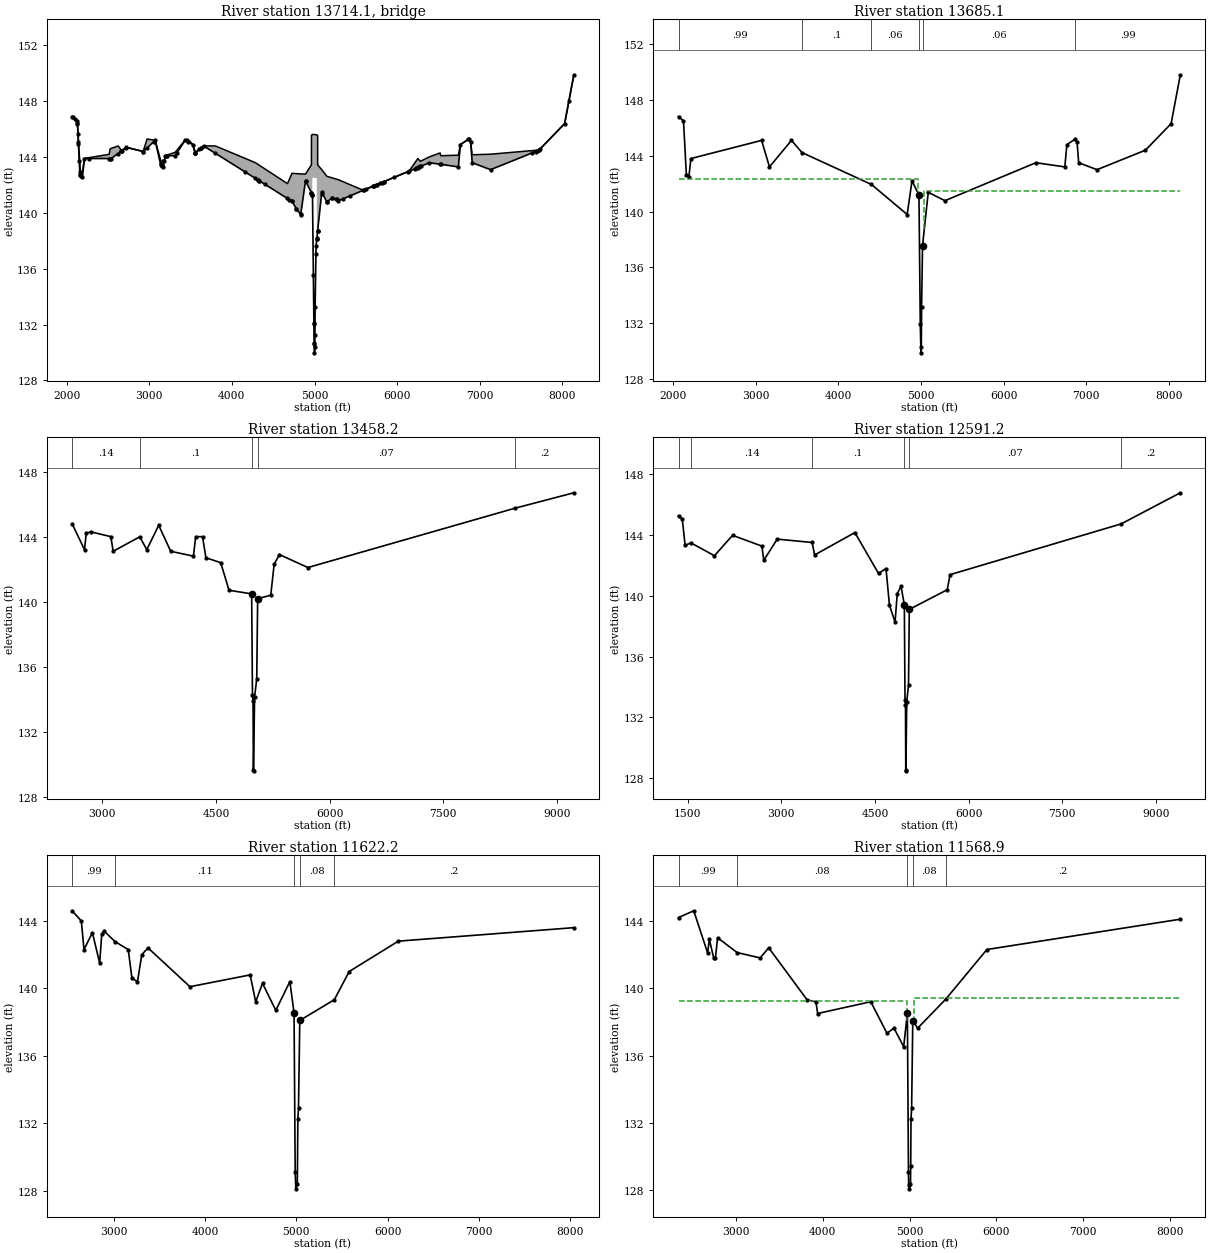
Type RM Length L Ch R = 3 ,13714.1 ,,,
BEGIN DESCRIPTION:
FRANZ ROAD
Structure ID: T00-9
END DESCRIPTION:
Bridge Culvert--1,0,-1,-1, 0
Deck Dist Width WeirC Skew NumUp NumDn MinLoCord MaxHiCord MaxSubmerge Is_Ogee
10,38,2.6,0, 60, 60, , , 0.95, 0, 1,1,,
    2067    2127    2132    2162  2165.5  2176.3    2192    2217  2515.7  2528.1
  2623.8  2668.1    2722    2927  2974.6    3072    3137  3148.5    3167  3181.9
    3197  3313.4  3433.4  3465.8  3528.4  3559.1  3657.7    3802  4285.4  4672.8
  4727.3  4833.2  4891.4 4962.99  4963.1 4972.91    4973 5028.09  5028.2  5038.1
 5038.21  5087.9  5149.1  5289.6  5588.9  6144.6    6250  6280.1  6390.3  6520.3
  6525.9  6740.3  6765.3    6868    6888    6908  7129.6  7716.1  8026.1  8137.6
   146.9  146.61  146.41   143.5   143.1   142.8  142.89  143.91   144.2   144.6
   144.8  144.47  144.71  144.41   145.3  145.21  143.81   143.6  143.81  143.71
  144.11  144.34  145.21   145.3  144.91  144.34  144.81   144.8   143.6   142.1
  142.84   142.8  142.79  143.45  145.55  145.63  145.63   145.6   145.6  145.54
  143.44   143.1  142.63  142.38  141.63     143   143.9   143.7  144.02   144.3
   144.1  144.14  144.91  145.31  145.11  144.17  144.21  144.51  146.41   149.9
   146.9   146.6   146.4   142.7  142.69  142.65   142.6   143.9   143.9   143.9
  144.26  144.46   144.7   144.4  144.66   145.2   143.5  143.42   143.3   143.7
   144.1   144.1   145.2   145.1   144.9  144.33   144.8  144.27  142.47  141.04
  140.88  139.89   142.3  141.44  141.44  141.32  142.53   142.5  138.17  138.72
  138.73  141.48   140.8  140.88  141.62  142.99  143.25  143.33   143.6  143.49
  143.48   143.3   144.9   145.3   145.1   143.6   143.1   144.5   146.4   149.9
    2067    2127    2132    2162  2165.5  2176.3    2192    2217  2515.7  2528.1
  2623.8  2668.1    2722    2927  2974.6    3072    3137  3148.5    3167  3181.9
    3197  3313.4  3433.4  3465.8  3528.4  3559.1  3657.7    3802  4285.4  4672.8
  4727.3  4833.2  4891.4 4962.99  4963.1 4972.91    4973 5028.09  5028.2  5038.1
 5038.21  5087.9  5149.1  5289.6  5588.9  6144.6    6250  6280.1  6390.3  6520.3
  6525.9  6740.3  6765.3    6868    6888    6908  7129.6  7716.1  8026.1  8137.6
   146.9  146.61  146.41   143.5   143.1   142.8  142.89  143.91   144.2   144.6
   144.8  144.47  144.71  144.41   145.3  145.21  143.81   143.6  143.81  143.71
  144.11  144.34  145.21   145.3  144.91  144.34  144.81   144.8   143.6   142.1
  142.84   142.8  142.79  143.45  145.55  145.63  145.63   145.6   145.6  145.54
  143.44   143.1  142.63  142.38  141.63     143   143.9   143.7  144.02   144.3
   144.1  144.14  144.91  145.31  145.11  144.17  144.21  144.51  146.41   149.9
  146.81  146.51  146.31  142.61   142.6  142.56  142.51  143.81  143.81  143.81
  144.17  144.37  144.61  144.31  144.57  145.11  143.41  143.33  143.21  143.61
  144.01  144.01  145.11  145.01  144.81  144.24  144.71  144.18  142.38  140.95
  140.79   139.8  142.21  141.35  141.35  141.23  142.44  142.41  138.08  138.63
  138.64  141.39  140.71  140.79  141.53   142.9  143.16  143.24  143.51   143.4
  143.39  143.21  144.81  145.21  145.01  143.51  143.01  144.41  146.31  149.81
Abutment Skew #Up #Dn= , 2 , 2
  4972.8  4991.5
  142.53  132.07
  4972.8  4991.5
  142.44  131.98
Abutment Skew #Up #Dn= , 2 , 2
  5017.4 5028.29
  137.09   142.5
  5017.4 5028.29
     137  142.41
BR Coef= 1 , 1 , 0 ,1.25, 0 ,,,0.8,0,2,0,
WSPro=,,,, 1 ,,,, 0 ,,,, 0 ,,,,-1 ,-1 ,-1 , 0 , 0 , 0 , 0 , 0
BR U #Sta/Elev= 147
    2067   146.9  2079.9  146.84  2097.3  146.75    2127   146.6  2130.8  146.45
    2132   146.4  2138.1  145.65  2142.4  145.12    2144  144.92  2153.9   143.7
  2160.2  142.92    2162   142.7  2165.5  142.69  2176.3  142.65    2192   142.6
    2217   143.9    2266   143.9  2515.7   143.9  2528.1   143.9    2542   143.9
  2623.8  144.26  2655.7  144.41  2656.3  144.41  2668.1  144.46  2714.9  144.67
    2722   144.7  2926.8   144.4    2927   144.4  2974.6  144.66  3054.8  145.11
    3072   145.2    3137   143.5  3148.5  143.42    3150  143.41  3160.2  143.35
    3167   143.3  3181.9   143.7    3197   144.1  3207.1   144.1  3213.8   144.1
  3313.4   144.1  3336.3  144.31  3433.4   145.2  3465.8   145.1  3528.4   144.9
  3553.4   144.3  3555.4  144.31  3559.1  144.33  3559.8  144.33  3605.8  144.55
  3621.4  144.63    3631  144.67  3657.7   144.8    3802  144.27  4157.1  142.95
  4285.4  142.47  4310.6  142.38  4312.6  142.37  4326.1  142.32  4327.6  142.32
  4401.1  142.04  4672.8  141.04  4696.2  140.95  4727.3  140.88  4727.5  140.88
  4778.8  140.29  4778.9  140.29  4833.2  139.89  4833.5   139.9  4891.2  142.29
  4891.4   142.3 4962.99  141.44  4963.1  141.44 4963.21  141.44  4972.8  141.32
 4972.91  141.32    4973  141.32  4975.6  141.29  4985.7  135.57  4991.4  132.13
  4991.5  132.07  4995.1  130.69  4996.9  130.58  4999.6  129.98  5004.2  130.37
    5005  131.27  5007.4  133.28  5017.4  137.09  5018.9  137.66 5028.09  138.17
  5028.2  138.17  5028.3  138.18 5037.99  138.72  5038.1  138.72 5038.21  138.73
  5086.3  141.39  5087.9  141.48  5149.1   140.8  5151.6  140.81  5212.1  141.06
  5212.4  141.06  5265.3     141  5266.6  140.99  5289.6  140.88  5349.5  141.03
  5424.6  141.21  5588.9  141.62  5603.1  141.65  5617.3  141.69  5707.3  141.91
  5708.1  141.91  5723.1  141.95  5738.1  141.99  5753.1  142.03  5790.5  142.12
  5813.2  142.17  5838.2  142.24  5843.3  142.25  5963.8  142.55  6129.5  142.96
  6144.6  142.99  6219.9  143.18  6224.7  143.19    6250  143.25  6252.3  143.26
  6265.1  143.29  6280.1  143.33  6285.3  143.34  6390.3   143.6  6520.3  143.49
  6525.9  143.48  6740.3   143.3  6765.3   144.9    6860  145.27    6868   145.3
    6888   145.1    6908   143.6  7129.6   143.1  7626.1  144.29  7674.7   144.4
  7695.1  144.45    7711  144.49  7716.1   144.5  7724.8  144.55  8026.1   146.4
    8078  148.03  8137.6   149.9
BR U #Mann= 6
    2067     .99  3559.8      .1  4401.1     .06  4975.6    .045  5018.9     .06
    6860     .99
BR U Banks=4975.6,5018.9
BR D #Sta/Elev= 147
    2067  146.81  2079.9  146.75  2097.3  146.66    2127  146.51  2130.8  146.36
    2132  146.31  2138.1  145.56  2142.4  145.03    2144  144.83  2153.9  143.61
  2160.2  142.83    2162  142.61  2165.5   142.6  2176.3  142.56    2192  142.51
    2217  143.81    2266  143.81  2515.7  143.81  2528.1  143.81    2542  143.81
  2623.8  144.17  2655.7  144.32  2656.3  144.32  2668.1  144.37  2714.9  144.58
    2722  144.61  2926.8  144.31    2927  144.31  2974.6  144.57  3054.8  145.02
    3072  145.11    3137  143.41  3148.5  143.33    3150  143.32  3160.2  143.26
    3167  143.21  3181.9  143.61    3197  144.01  3207.1  144.01  3213.8  144.01
  3313.4  144.01  3336.3  144.22  3433.4  145.11  3465.8  145.01  3528.4  144.81
  3553.4  144.21  3555.4  144.22  3559.1  144.24  3559.8  144.24  3605.8  144.46
  3621.4  144.54    3631  144.58  3657.7  144.71    3802  144.18  4157.1  142.86
  4285.4  142.38  4310.6  142.29  4312.6  142.28  4326.1  142.23  4327.6  142.23
  4401.1  141.95  4672.8  140.95  4696.2  140.86  4727.3  140.79  4727.5  140.79
  4778.8   140.2  4778.9   140.2  4833.2   139.8  4833.5  139.81  4891.2   142.2
  4891.4  142.21 4962.99  141.35  4963.1  141.35 4963.21  141.35  4972.8  141.23
 4972.91  141.23    4973  141.23  4975.6   141.2  4985.7  135.48  4991.4  132.04
  4991.5  131.98  4995.1   130.6  4996.9  130.49  4999.6  129.89  5004.2  130.28
    5005  131.18  5007.4  133.19  5017.4     137  5018.9  137.57 5028.09  138.08
  5028.2  138.08  5028.3  138.09 5037.99  138.63  5038.1  138.63 5038.21  138.64
  5086.3   141.3  5087.9  141.39  5149.1  140.71  5151.6  140.72  5212.1  140.97
  5212.4  140.97  5265.3  140.91  5266.6   140.9  5289.6  140.79  5349.5  140.94
  5424.6  141.12  5588.9  141.53  5603.1  141.56  5617.3   141.6  5707.3  141.82
  5708.1  141.82  5723.1  141.86  5738.1   141.9  5753.1  141.94  5790.5  142.03
  5813.2  142.08  5838.2  142.15  5843.3  142.16  5963.8  142.46  6129.5  142.87
  6144.6   142.9  6219.9  143.09  6224.7   143.1    6250  143.16  6252.3  143.17
  6265.1   143.2  6280.1  143.24  6285.3  143.25  6390.3  143.51  6520.3   143.4
  6525.9  143.39  6740.3  143.21  6765.3  144.81    6860  145.18    6868  145.21
    6888  145.01    6908  143.51  7129.6  143.01  7626.1   144.2  7674.7  144.31
  7695.1  144.36    7711   144.4  7716.1  144.41  7724.8  144.46  8026.1  146.31
    8078  147.94  8137.6  149.81
BR D #Mann= 6
    2067     .99  3559.8      .1  4401.1     .06  4975.6    .045  5018.9     .06
    6860     .99
BR D Banks=4975.6,5018.9
BC Design=,, 0 ,, 0 ,,,,,,
BC HTab HWMax=149.9

Type RM Length L Ch R = 1 ,13685.1 ,226.9,226.9,226.9
BEGIN DESCRIPTION:
Downstream Section of Bridge/Culvert/Weir
END DESCRIPTION:
XS GIS Cut Line= 6
      2976774.32     13852760.44       2975582.4     13852324.19
      2975298.33     13852245.63      2973140.24     13852178.51
      2971307.53     13852087.78      2970826.57     13852261.96
#Sta/Elev= 30
    2067   146.8    2127   146.5    2162   142.6    2192   142.5    2217   143.8
    3072   145.1    3167   143.2  3433.4   145.1  3559.8  144.23  4401.1  141.94
  4833.2  139.79  4891.4   142.2  4975.6  141.19  4991.5  131.97  4999.6  129.88
  5004.2  130.27  5007.4  133.18  5018.9  137.56  5087.9  141.38  5289.6  140.78
  6390.3   143.5  6740.3   143.2  6765.3   144.8    6860  145.17    6888     145
    6908   143.5  7129.6     143  7716.1   144.4  8026.1   146.3  8137.6   149.8
#Mann= 6 , 1 , 0
    2067     .99       0  3559.8      .1       0  4401.1     .06       0
  4975.6    .045       0  5018.9     .06       0    6860     .99       0
#XS Ineff= 2 , 0
       0    4962   142.3    5040       0   141.5
Permanent Ineff=
       F       F
Bank Sta=4975.6,5018.9
Exp/Cntr=0.5,0.3

Type RM Length L Ch R = 1 ,13458.2 ,850.6,867,787.4
BEGIN DESCRIPTION:
Cross Section 13458.2-Interpolated
END DESCRIPTION:
XS GIS Cut Line= 6
      2976277.77      13852248.5      2976059.59     13852138.13
      2975340.03     13851993.97      2973583.76     13851965.28
        2973208.     13851955.32      2969701.94     13852087.53
#Sta/Elev= 30
  2602.6   144.8  2766.7   143.2  2789.1   144.2  2847.1   144.3  3114.1     144
  3144.7   143.1  3495.2  143.99  3588.2   143.2  3745.7   144.7  3903.3   143.1
  4203.3   142.8  4233.4     144  4323.4     144  4368.4   142.7  4563.4   142.4
  4673.4   140.7  4971.5  140.48  4982.3  134.25  4990.1  133.88  4994.2  129.67
  4996.3  129.59    5010  134.11  5038.6  135.25  5050.9  140.18  5223.5   140.4
  5268.5   142.3  5337.5   142.9  5713.4   142.1  8444.5  145.75    9222   146.7
#Mann= 5 , 1 , 0
  2602.6     .14       0  3495.2      .1       0  4971.5    .045       0
  5050.9     .07       0  8444.5      .2       0
#XS Ineff= 2 , 0
       0  3745.7   144.7               0
Permanent Ineff=
       F       F
Bank Sta=4971.5,5050.9
Exp/Cntr=0.3,0.1

Type RM Length L Ch R = 1 ,12591.2 ,1114.9,969,906.9
BEGIN DESCRIPTION:
Cross Section 12591.2
END DESCRIPTION:
XS GIS Cut Line= 6
      2977548.56     13851453.92      2976071.55      13851330.8
      2975518.03     13851187.93      2974022.87     13851086.56
      2972648.08      13851200.6      2969638.76     13851948.18
#Sta/Elev= 30
  1355.6  145.23  1415.6  145.02  1460.6   143.3    1556  143.45  1930.6  142.61
  2220.6  143.95  2690.6  143.24  2720.6  142.31  2935.6   143.7  3495.2  143.48
  3534.4  142.66  4179.4  144.13  4557.9  141.45  4677.9  141.77  4732.9  139.37
  4822.9  138.25  4857.9  140.12    4919  140.61  4971.5  139.39  4982.3  133.16
  4990.1  132.79  4994.2  128.58  4996.3   128.5    5010  133.02  5038.6  134.16
  5050.9  139.09  5658.9  140.38  5703.9  141.37  8444.5   144.7  9391.2  146.74
#Mann= 6 , 1 , 0
  1355.6      .2       0    1556     .14       0  3495.2      .1       0
  4971.5    .045       0  5050.9     .07       0  8444.5      .2       0
#XS Ineff= 2 , 0
       0  4179.4  144.13               0
Permanent Ineff=
       F       F
Bank Sta=4971.5,5050.9
Exp/Cntr=0.3,0.1

Type RM Length L Ch R = 1 ,11622.2 ,53.9,53.3,53
BEGIN DESCRIPTION:
Cross Section 11622.2-Interpolated
END DESCRIPTION:
XS GIS Cut Line= 6
      2975909.57      13851001.2      2975292.17     13850442.08
      2974933.89     13850279.08      2973265.23     13850218.07
      2972830.63     13850341.09       2970697.8     13850648.61
#Sta/Elev= 30
  2540.2   144.6  2641.9     144  2670.8   142.3  2763.3   143.3    2843   141.5
  2865.4   143.2  2890.7   143.4  3011.9  142.77  3156.4   142.3  3196.9   140.6
  3257.6   140.4  3304.9     142  3373.1   142.4  3832.9   140.1  4493.6   140.8
  4553.7   139.2  4628.7   140.3  4774.5   138.7  4928.8   140.4  4974.6  138.55
  4987.1  129.13  4994.1  128.12  5010.5   128.4  5016.3  132.25  5023.5   132.9
  5037.3   138.1  5416.7  139.33  5579.5     141  6118.4   142.8  8043.2   143.6
#Mann= 5 , 1 , 0
  2540.2     .99       0  3011.9     .11       0  4974.6     .04       0
  5037.3     .08       0  5416.7      .2       0
#XS Ineff= 2 , 0
       0  3373.1   142.4               0
Permanent Ineff=
       F       F
Bank Sta=4974.6,5037.3
Exp/Cntr=0.5,0.3

Type RM Length L Ch R = 1 ,11568.9 ,53,53,53
BEGIN DESCRIPTION:
Upstream Section of Bridge/Culvert/Weir
END DESCRIPTION:
XS GIS Cut Line= 6
      2976056.07     13851092.25      2975315.98     13850416.19
      2974939.87     13850223.72      2973307.65     13850158.19
      2972816.91     13850296.38      2970623.45     13850615.36
#Sta/Elev= 30
  2336.3   144.2  2511.6   144.6  2671.6   142.1  2691.6   142.9  2741.6   141.8
  2761.6   141.8  2786.6     143  3011.9  142.12  3276.6   141.8  3376.3   142.4
    3820   139.3    3920   139.2    3940   138.5  4552.6   139.2  4739.2  137.33
  4820.4  137.63  4931.9  136.53  4974.6  138.52  4987.1   129.1  4989.4  128.29
  4994.1  128.09  5010.5  128.37    5013  129.47  5016.3  132.22  5023.5  132.87
  5036.9  138.07  5093.2  137.63  5416.7  139.35  5891.5   142.3  8121.4   144.1
#Mann= 5 , 1 , 0
  2336.3     .99       0  3011.9     .08       0  4974.6     .04       0
  5036.9     .08       0  5416.7      .2       0
#XS Ineff= 2 , 0
       0  4964.6  139.27  5046.9       0  139.45
Permanent Ineff=
       F       F
Bank Sta=4974.6,5036.9
Exp/Cntr=0.5,0.3

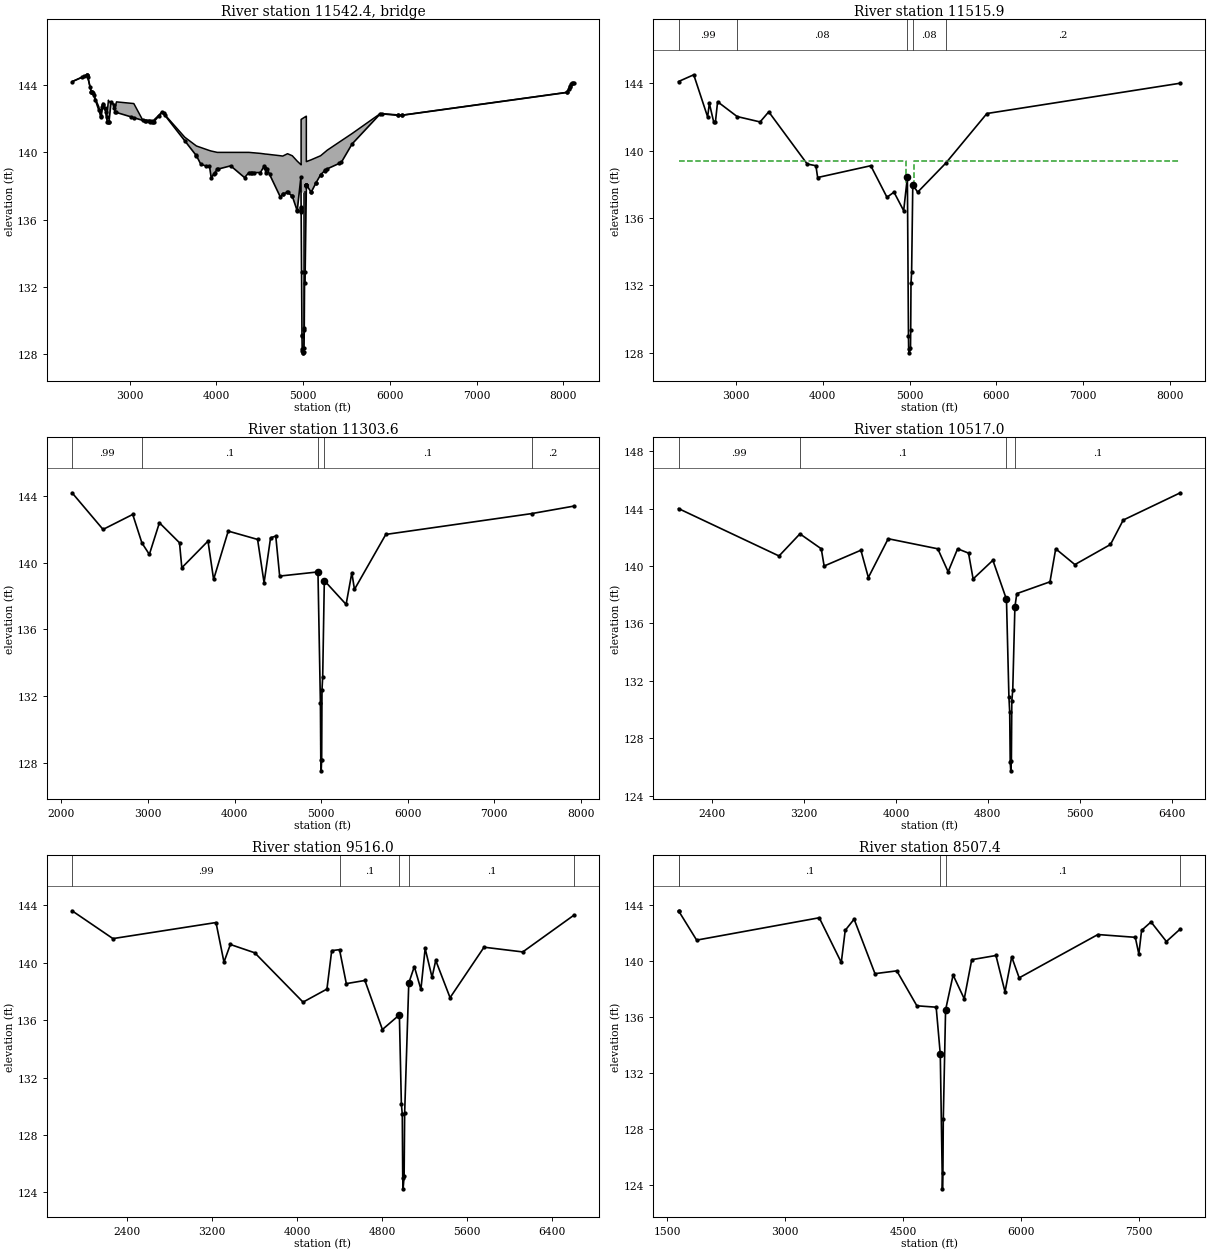
Type RM Length L Ch R = 3 ,11542.4 ,,,
BEGIN DESCRIPTION:
TENTH STREET
Structure ID: T00-8
END DESCRIPTION:
Bridge Culvert--1,0,-1,-1, 0
Deck Dist Width WeirC Skew NumUp NumDn MinLoCord MaxHiCord MaxSubmerge Is_Ogee
10,33,2.6,0, 60, 60, , , 0.95, 0, 1,1,,
  2336.3  2511.6  2556.6  2571.6  2645.2  2665.5  2671.6  2691.6  2726.6  2733.4
  2741.6  2755.6  2761.6  2786.6  2821.6  2825.3  2831.6  2848.4  3048.3  3151.6
  3276.6  3376.3  3635.7    3770    3820    3920    3940    4010    4165    4325
    4375  4507.6  4552.6  4562.6  4567.6  4587.6  4739.2  4764.5  4820.4    4875
  4931.9  4974.6 4976.77 4976.88 4977.11  4977.2  5023.5  5037.2  5037.3 5037.41
  5093.2  5201.6  5278.1  5439.8  5564.8  5891.5  6136.5  8043.6  8103.6  8121.4
   144.2  144.61  143.61  143.61   142.7   142.2  142.31  142.91  142.41  142.14
  142.41   143.1     143  143.01  142.81  142.66  142.64     143   142.9  141.91
  141.91  142.41   140.9  140.38  140.29  140.11  140.08     140     140     140
     140  139.94  139.91   139.9   139.9  139.89   139.8  139.78  139.92   139.8
  139.48  139.27  139.26  141.96  141.96  141.96  142.11  142.15  139.45  139.45
  139.56   139.8  140.13  140.69  141.12  142.31  142.21  143.57  144.14   144.1
   144.2   144.6   143.6   143.6   142.5  142.19   142.1   142.9   142.4  142.13
   141.8   141.8   141.8     143   142.8  142.65   142.4  142.37  142.06   141.9
   141.8   142.4  140.69   139.8   139.3   139.2   138.5     139   139.2   138.5
   138.8   138.8   139.2   139.1   138.8     139  137.33  137.52  137.63   137.4
  136.53  138.52  136.77  136.68   136.5  137.56  137.71  138.07  138.07  138.07
  137.63  138.67  139.02   139.4   140.5   142.3   142.2  143.56  144.13   144.1
  2336.3  2511.6  2556.6  2571.6  2645.2  2665.5  2671.6  2691.6  2726.6  2733.4
  2741.6  2755.6  2761.6  2786.6  2821.6  2825.3  2831.6  2848.4  3048.3  3151.6
  3276.6  3376.3  3635.7    3770    3820    3920    3940    4010    4165    4325
    4375  4507.6  4552.6  4562.6  4567.6  4587.6  4739.2  4764.5  4820.4    4875
  4931.9  4974.6 4976.77 4976.88 4977.11  4977.2  5023.5  5037.2  5037.3 5037.41
  5093.2  5201.6  5278.1  5439.8  5564.8  5891.5  6136.5  8043.6  8103.6  8121.4
   144.2  144.61  143.61  143.61   142.7   142.2  142.31  142.91  142.41  142.14
  142.41   143.1     143  143.01  142.81  142.66  142.64     143   142.9  141.91
  141.91  142.41   140.9  140.38  140.29  140.11  140.08     140     140     140
     140  139.94  139.91   139.9   139.9  139.89   139.8  139.78  139.92   139.8
  139.48  139.27  139.26  141.96  141.96  141.96  142.11  142.15  139.45  139.45
  139.56   139.8  140.13  140.69  141.12  142.31  142.21  143.57  144.14   144.1
  144.12  144.52  143.52  143.52  142.42  142.11  142.02  142.82  142.32  142.05
  141.72  141.72  141.72  142.92  142.72  142.57  142.32  142.29  141.98  141.82
  141.72  142.32  140.61  139.72  139.22  139.12  138.42  138.92  139.12  138.42
  138.72  138.72  139.12  139.02  138.72  138.92  137.25  137.44  137.55  137.32
  136.45  138.44  136.69   136.6  136.42  137.48  137.63  137.99  137.99  137.99
  137.55  138.59  138.94  139.32  140.42  142.22  142.12  143.48  144.05  144.02
Pier Skew, UpSta & Num, DnSta & Num=  ,4995.4, 2 ,4995.4, 2 , 0 , 0 , 0 ,,
       1       1
   127.1  138.62
       1       1
  127.02  138.54
Pier Skew, UpSta & Num, DnSta & Num=  ,5016.3, 2 ,5016.3, 2 , 0 , 0 , 0 ,,
       1       1
   130.8  138.68
       1       1
  130.72   138.6
Abutment Skew #Up #Dn= , 2 , 2
    4977  4987.1
  137.56   129.1
    4977  4987.1
  137.48  129.02
Abutment Skew #Up #Dn= , 2 , 2
  5013.1 5036.99
  129.55  138.03
  5013.1 5036.99
  129.47  137.95
BR Coef= 1 , 1 , 0 ,1.25, 0 ,,,0.8,0,2,0,
WSPro=,,,, 1 ,,,, 0 ,,,, 0 ,,,,-1 ,-1 ,-1 , 0 , 0 , 0 , 0 , 0
BR U #Sta/Elev= 132
  2336.3   144.2  2453.7  144.47    2475  144.52    2503  144.58  2506.8  144.59
  2511.6   144.6  2517.4  144.47  2543.6  143.89  2556.6   143.6  2559.9   143.6
  2570.5   143.6  2571.6   143.6  2577.7  143.51  2584.3  143.41  2604.6  143.11
  2645.2   142.5  2665.5  142.19  2671.6   142.1  2685.8  142.67  2688.9  142.79
  2691.6   142.9  2711.2  142.62  2726.6   142.4  2733.4  142.13  2741.6   141.8
  2755.6   141.8  2761.5   141.8  2761.6   141.8  2786.6     143  2821.6   142.8
  2825.3  142.65  2831.6   142.4  2848.4  142.37  3011.9  142.12  3048.3  142.06
  3151.6   141.9  3173.4  141.88  3193.8  141.87  3222.7  141.84  3239.4  141.83
  3254.7  141.82    3275   141.8  3276.6   141.8  3338.7  142.17  3376.3   142.4
  3390.5  142.31  3403.8  142.22  3635.7  140.69  3759.6  139.87    3770   139.8
    3820   139.3    3875   139.2    3920   139.2    3940   138.5    3970   138.7
  3983.3   138.8    4010     139    4015     139    4165   139.2    4325   138.5
    4375   138.8  4403.6   138.8    4406   138.8  4432.6   138.8  4507.6   138.8
  4552.6   139.2  4562.6   139.1  4567.6   138.8  4587.6     139  4612.6   138.7
  4739.2  137.33  4764.5  137.52  4765.2  137.52  4819.8  137.63  4820.4  137.63
  4874.9   137.4    4875   137.4  4931.9  136.53  4933.2  136.59  4974.6  138.52
 4976.77  136.77 4976.88  136.68 4976.99  136.59 4977.11   136.5  4977.2  136.43
  4981.6  132.88    4987  129.17  4987.1   129.1  4989.4  128.29  4991.2  128.19
  4994.1  128.09  4995.4   128.1  5008.3  128.15  5010.5  128.37    5013  129.47
  5013.1  129.55  5016.3  132.22  5023.5  132.87 5036.79  138.03  5036.9  138.07
    5037  138.07 5037.09  138.07  5037.2  138.07  5037.3  138.07 5037.41  138.07
    5093  137.63  5093.2  137.63  5148.2  138.19  5148.7  138.19  5201.6  138.67
  5201.7  138.67  5251.4  138.92    5253  138.93  5278.1  139.02  5416.7  139.35
  5439.8   139.4  5564.8   140.5  5891.5   142.3  5904.9  142.29  6090.7   142.2
  6091.5   142.2  6136.2   142.2  6136.5   142.2  8043.6  143.56  8046.1  143.59
  8061.2  143.76  8073.6   143.9  8076.4  143.92  8091.5  144.04  8103.6  144.13
  8106.7  144.12  8121.4   144.1
BR U #Mann= 5
  2336.3     .99  3011.9     .08  4974.6     .04  5036.9     .08  5416.7      .2
BR U Banks=4974.6,5036.9
BR D #Sta/Elev= 132
  2336.3  144.12  2453.7  144.39    2475  144.44    2503   144.5  2506.8  144.51
  2511.6  144.52  2517.4  144.39  2543.6  143.81  2556.6  143.52  2559.9  143.52
  2570.5  143.52  2571.6  143.52  2577.7  143.43  2584.3  143.33  2604.6  143.03
  2645.2  142.42  2665.5  142.11  2671.6  142.02  2685.8  142.59  2688.9  142.71
  2691.6  142.82  2711.2  142.54  2726.6  142.32  2733.4  142.05  2741.6  141.72
  2755.6  141.72  2761.5  141.72  2761.6  141.72  2786.6  142.92  2821.6  142.72
  2825.3  142.57  2831.6  142.32  2848.4  142.29  3011.9  142.04  3048.3  141.98
  3151.6  141.82  3173.4   141.8  3193.8  141.79  3222.7  141.76  3239.4  141.75
  3254.7  141.74    3275  141.72  3276.6  141.72  3338.7  142.09  3376.3  142.32
  3390.5  142.23  3403.8  142.14  3635.7  140.61  3759.6  139.79    3770  139.72
    3820  139.22    3875  139.12    3920  139.12    3940  138.42    3970  138.62
  3983.3  138.72    4010  138.92    4015  138.92    4165  139.12    4325  138.42
    4375  138.72  4403.6  138.72    4406  138.72  4432.6  138.72  4507.6  138.72
  4552.6  139.12  4562.6  139.02  4567.6  138.72  4587.6  138.92  4612.6  138.62
  4739.2  137.25  4764.5  137.44  4765.2  137.44  4819.8  137.55  4820.4  137.55
  4874.9  137.32    4875  137.32  4931.9  136.45  4933.2  136.51  4974.6  138.44
 4976.77  136.69 4976.88   136.6 4976.99  136.51 4977.11  136.42  4977.2  136.35
  4981.6   132.8    4987  129.09  4987.1  129.02  4989.4  128.21  4991.2  128.11
  4994.1  128.01  4995.4  128.02  5008.3  128.07  5010.5  128.29    5013  129.39
  5013.1  129.47  5016.3  132.14  5023.5  132.79 5036.79  137.95  5036.9  137.99
    5037  137.99 5037.09  137.99  5037.2  137.99  5037.3  137.99 5037.41  137.99
    5093  137.55  5093.2  137.55  5148.2  138.11  5148.7  138.11  5201.6  138.59
  5201.7  138.59  5251.4  138.84    5253  138.85  5278.1  138.94  5416.7  139.27
  5439.8  139.32  5564.8  140.42  5891.5  142.22  5904.9  142.21  6090.7  142.12
  6091.5  142.12  6136.2  142.12  6136.5  142.12  8043.6  143.48  8046.1  143.51
  8061.2  143.68  8073.6  143.82  8076.4  143.84  8091.5  143.96  8103.6  144.05
  8106.7  144.04  8121.4  144.02
BR D #Mann= 5
  2336.3     .99  3011.9     .08  4974.6     .04  5036.9     .08  5416.7      .2
BR D Banks=4974.6,5036.9
BC Design=,, 0 ,, 0 ,,,,,,
BC HTab HWMax=144.6

Type RM Length L Ch R = 1 ,11515.9 ,212.3,212.3,212.3
BEGIN DESCRIPTION:
Downstream Section of Bridge/Culvert/Weir
END DESCRIPTION:
XS GIS Cut Line= 6
      2976055.69     13851039.25       2975315.6     13850363.19
      2974939.49     13850170.72      2973307.27     13850105.19
      2972816.53     13850243.38      2970623.07     13850562.36
#Sta/Elev= 30
  2336.3   144.1  2511.6   144.5  2671.6     142  2691.6   142.8  2741.6   141.7
  2761.6   141.7  2786.6   142.9  3011.9  142.02  3276.6   141.7  3376.3   142.3
    3820   139.2    3920   139.1    3940   138.4  4552.6   139.1  4739.2  137.23
  4820.4  137.53  4931.9  136.43  4974.6  138.42  4987.1     129  4989.4  128.19
  4994.1  127.99  5010.5  128.27    5013  129.37  5016.3  132.12  5023.5  132.77
  5036.9  137.97  5093.2  137.53  5416.7  139.25  5891.5   142.2  8121.4     144
#Mann= 5 , 1 , 0
  2336.3     .99       0  3011.9     .08       0  4974.6     .04       0
  5036.9     .08       0  5416.7      .2       0
#XS Ineff= 2 , 0
       0    4964   139.4    5046       0   139.4
Permanent Ineff=
       F       F
Bank Sta=4974.6,5036.9
Exp/Cntr=0.5,0.3

Type RM Length L Ch R = 1 ,11303.6 ,14.9,786.6,1217.6
BEGIN DESCRIPTION:
Cross Section 11303.6-Interpolated
END DESCRIPTION:
XS GIS Cut Line= 6
       2976103.9      13850974.7      2975325.19     13850291.77
      2974362.23     13849887.16      2973738.55     13849879.23
      2973354.98     13850054.04      2970712.85     13850337.17
#Sta/Elev= 30
  2122.2   144.2  2480.1     142  2822.9   142.9  2928.9  141.19  3014.9   140.5
  3131.1   142.4  3363.3   141.2    3390   139.7  3692.4   141.3  3757.2     139
  3926.1   141.9  4265.2   141.4  4340.2   138.8  4415.4   141.5  4475.2   141.6
  4520.2   139.2  4962.7  139.45  4990.8   131.6  4995.3  128.15  4999.9  127.51
  5005.5  128.19  5009.2  132.37  5017.4  133.15  5036.1  138.93  5287.7   137.5
  5354.1   139.4  5384.3   138.4  5746.4   141.7  7430.5  142.95  7918.7   143.4
#Mann= 5 , 1 , 0
  2122.2     .99       0  2928.9      .1       0  4962.7     .04       0
  5036.1      .1       0  7430.5      .2       0
#XS Ineff= 2 , 0
       0  4475.2   141.6               0
Permanent Ineff=
       F       F
Bank Sta=4962.7,5036.1
Exp/Cntr=0.3,0.1

Type RM Length L Ch R = 1 ,10517.0 ,1263.6,1001,803.2
BEGIN DESCRIPTION:
Cross Section 10517.0
END DESCRIPTION:
XS GIS Cut Line= 6
      2976127.99     13850971.51      2975342.37     13850274.59
       2974368.1     13849874.66      2973752.99     13849253.52
      2972890.63      13849090.7      2972414.95     13849192.22
#Sta/Elev= 30
  2107.3     144  2982.3   140.7  3164.3  142.24  3350.1   141.2  3375.1     140
  3695.1   141.1  3760.1   139.2  3932.9   141.9  4364.6   141.2  4454.6   139.6
  4537.3   141.2  4632.3   140.9  4672.3   139.1  4844.4   140.4  4962.7  137.68
  4983.9  130.91  4990.8  129.83  4995.3  126.38  4999.9  125.74  5005.5  126.42
  5009.2   130.6  5017.4  131.38  5036.1  137.16  5052.7  138.08  5341.5   138.9
  5391.5   141.2  5558.4   140.1  5868.4   141.5  5979.3   143.2  6476.5   145.1
#Mann= 4 , 1 , 0
  2107.3     .99       0  3164.3      .1       0  4962.7     .04       0
  5036.1      .1       0
#XS Ineff= 2 , 0
       0  4537.3   141.2               0
Permanent Ineff=
       F       F
Bank Sta=4962.7,5036.1
Exp/Cntr=0.3,0.1

Type RM Length L Ch R = 1 ,9516.0  ,751.8,1008.6,736.9
BEGIN DESCRIPTION:
Cross Section 9516.0
END DESCRIPTION:
XS GIS Cut Line= 6
      2976918.98     13850073.66       2976146.5     13849076.86
      2974930.13     13848910.99      2974394.63     13848746.96
      2974356.03     13848568.46      2972872.83     13848381.29
#Sta/Elev= 30
  1880.3  143.63  2265.3  141.69  3236.4  142.81  3311.4  140.05  3371.4  141.28
  3601.4   140.7  4056.4  137.26  4281.4  138.17  4326.4  140.85    4400  140.92
    4464  138.55    4639  138.77    4804  135.35  4963.9  136.37  4982.6  130.18
  4991.3  129.43  4995.4  125.01    4999  124.24  5008.6  125.11  5013.6  129.52
  5052.4  138.59  5104.7  139.74  5166.7  138.15  5206.7     141  5271.7  138.99
  5306.4  140.17  5441.4  137.57  5761.4  141.09  6126.4  140.76  6607.7  143.32
#Mann= 5 , 1 , 0
  1880.3     .99       0    4400      .1       0  4963.9    .045       0
  5052.4      .1       0  6607.7      .2       0
Bank Sta=4963.9,5052.4
Exp/Cntr=0.3,0.1

Type RM Length L Ch R = 1 ,8507.4  ,1291.4,907,624.6
BEGIN DESCRIPTION:
Cross Section 8507.4
END DESCRIPTION:
XS GIS Cut Line= 6
      2977672.79     13849910.84      2976162.93     13848954.67
      2974874.17     13847843.84       2973585.1     13847782.09
      2973109.58      13848050.7      2972064.46     13848113.76
#Sta/Elev= 30
  1646.5   143.6  1646.6   143.6  1876.6   141.5  3433.8   143.1  3713.8   139.9
  3763.8   142.2  3876.8     143  4141.8   139.1  4418.9   139.3  4673.9   136.8
  4919.1   136.7  4971.3  133.35  4998.6   123.7  5004.9  124.82  5009.5  128.67
  5038.7  136.51  5134.1     139  5275.8   137.3  5370.8   140.1  5678.5   140.4
  5793.5   137.8  5878.5   140.3  5973.5   138.8  6973.5   141.9  7448.5   141.7
  7493.5   140.5  7528.5   142.2  7648.5   142.8  7843.5   141.4  8020.5   142.3
#Mann= 5 , 1 , 0
  1646.5      .2       0  1646.6      .1       0  4971.3     .04       0
  5038.7      .1       0  8020.5      .2       0
#XS Ineff= 2 , 0
       0                  5134.1       0     139
Permanent Ineff=
       F       F
Bank Sta=4971.3,5038.7
Exp/Cntr=0.3,0.1