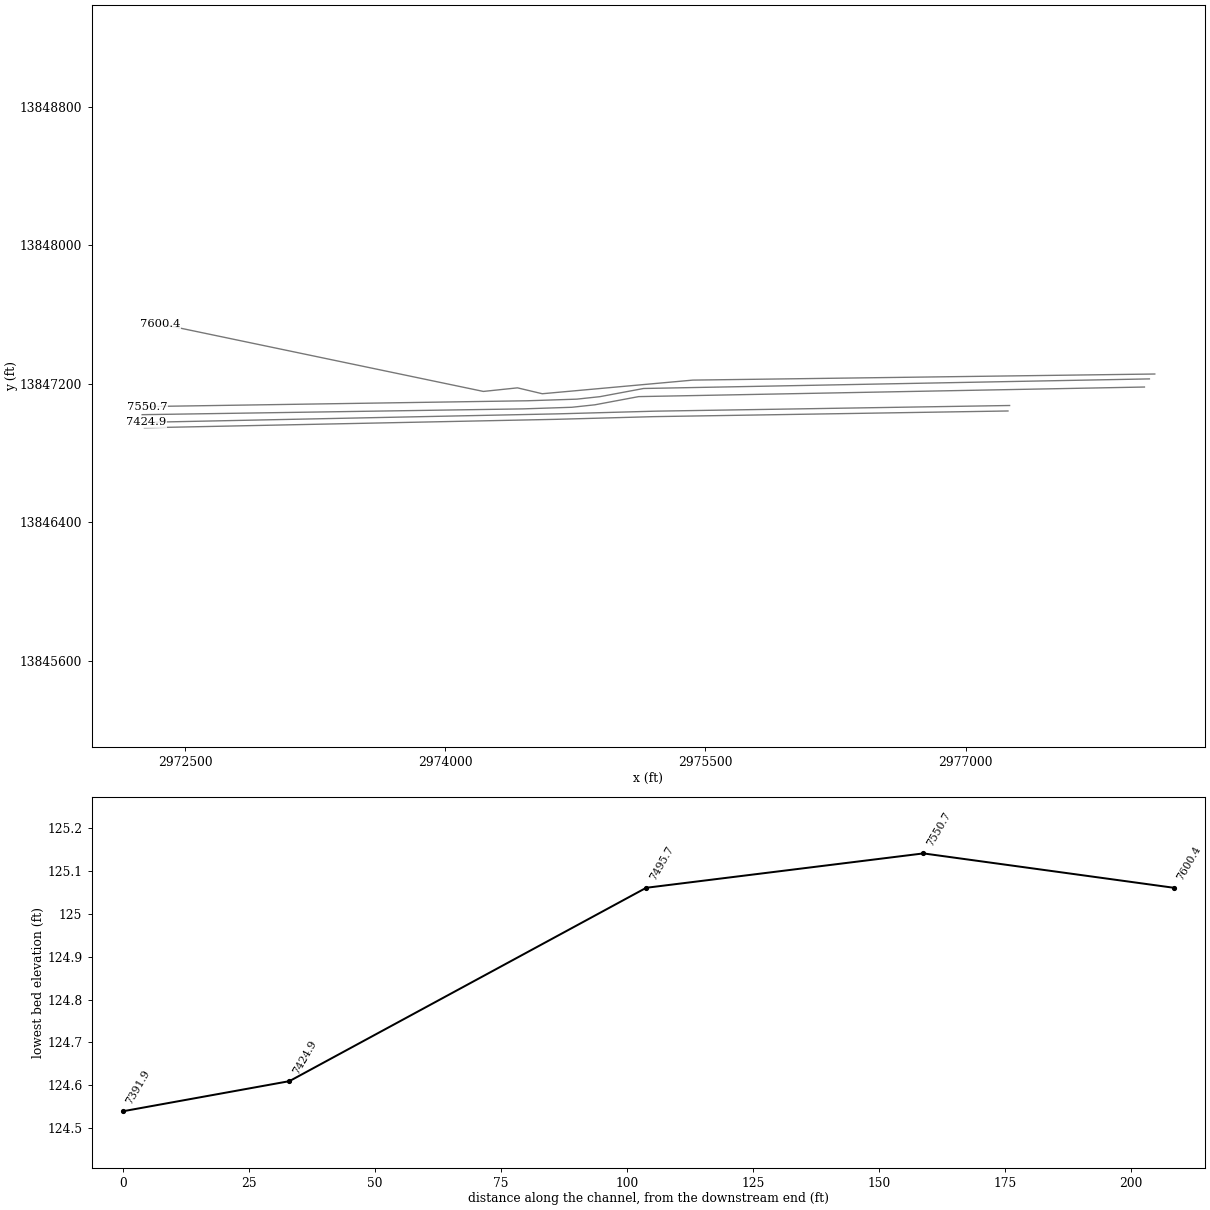
HEC-RAS study T100-00-00.PRJ: T100-00-00

--- T100-00-00.g01 (geometry) --- (continued)

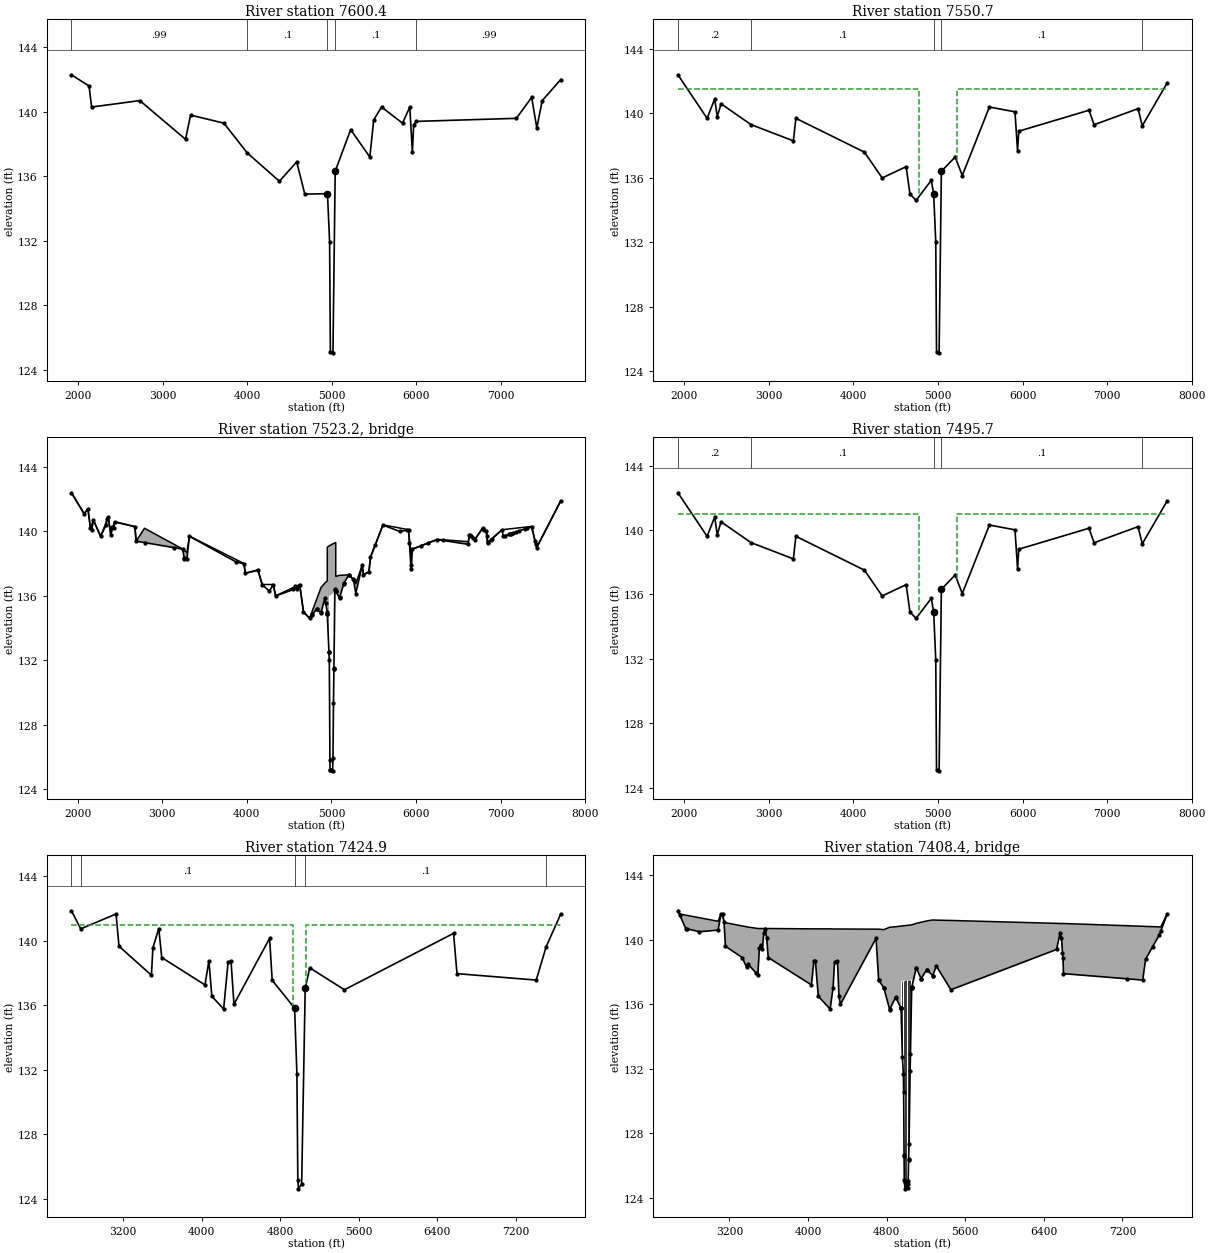
Type RM Length L Ch R = 1 ,7600.4  ,19.4,49.7,25.8
BEGIN DESCRIPTION:
Cross Section 7600.4-Interpolated
END DESCRIPTION:
XS GIS Cut Line= 6
      2978091.24     13847255.76      2975427.95     13847220.55
      2974559.85     13847141.79      2974416.66      13847175.8
       2974220.2     13847155.12      2972356.04     13847545.22
#Sta/Elev= 30
  1922.5   142.3    2131   141.6    2161   140.3    2731   140.7  3271.1   138.3
  3331.1   139.8  3725.1   139.3    4000  137.46  4381.2   135.7    4586   136.9
  4681.2   134.9  4949.6  134.93  4974.7  131.93  4983.6  125.14  5014.2  125.06
  5040.8  136.32  5223.6   138.9  5450.1   137.2  5496.2   139.5  5588.7   140.3
  5836.8   139.3  5922.7   140.3  5953.4   137.5  5968.7   139.2    6000  139.41
  7183.5   139.6  7363.3   140.9  7424.6     139  7488.4   140.7  7707.3     142
#Mann= 5 , 1 , 0
  1922.5     .99       0    4000      .1       0  4949.6     .04       0
  5040.8      .1       0    6000     .99       0
Bank Sta=4949.6,5040.8
Exp/Cntr=0.5,0.3

Type RM Length L Ch R = 1 ,7550.7  ,55,55,55
BEGIN DESCRIPTION:
Upstream Section of Bridge/Culvert/Weir
END DESCRIPTION:
XS GIS Cut Line= 6
      2978060.18     13847227.51      2975143.98     13847172.12
      2974891.96     13847124.86      2974758.79     13847110.54
      2974475.33     13847101.21      2972281.52     13847067.76
#Sta/Elev= 30
    1926  142.39    2271  139.69    2361  140.89    2391  139.79    2436  140.59
  2789.9   139.3    3291  138.29    3321  139.69    4131  137.59    4341  135.99
  4624.5  136.69  4669.5  134.99  4741.8   134.6  4921.8  135.84  4949.6  135.01
  4974.7  132.01  4983.6  125.22  5014.2  125.14  5040.8   136.4  5203.8  137.29
    5288  136.14  5608.8  140.39  5911.3  140.09  5941.3  137.69  5956.3  138.89
  6786.3  140.19  6846.3  139.29  7366.3  140.29  7415.7  139.22  7710.8  141.89
#Mann= 5 , 1 , 0
    1926      .2       0  2789.9      .1       0  4949.6     .04       0
  5040.8      .1       0  7415.7      .2       0
#XS Ineff= 2 , 0
       0    4780   141.5    5220       0   141.5
Permanent Ineff=
       F       F
Bank Sta=4949.6,5040.8
Exp/Cntr=0.5,0.3

Type RM Length L Ch R = 3 ,7523.2  ,,,
BEGIN DESCRIPTION:
FIRST STREET
Structure ID: T00-7
END DESCRIPTION:
Bridge Culvert--1,0,-1,-1, 0
Deck Dist Width WeirC Skew NumUp NumDn MinLoCord MaxHiCord MaxSubmerge Is_Ogee
10,35,2.6,0, 60, 60, , , 0.95, 0, 1,1,,
    1926    2076    2121    2151    2186    2271    2361    2391    2436    2676
    2691  2789.9    3241    3261    3291    3321    3966    3981    4131    4181
    4311    4341  4624.5  4669.5  4741.8  4876.2  4921.8 4950.59  4950.7 4970.51
  4970.6    5018 5029.19  5029.3  5040.8  5050.7 5050.81  5095.2  5203.8  5259.5
    5288  5363.3  5378.3  5443.3  5461.6  5608.8  5911.3  5941.3  5956.3  6251.3
  6616.3  6631.3  6696.3  6786.3  6831.3  6846.3  7016.3  7366.3  7426.3  7710.8
   142.4   141.1   141.4   140.2   140.7   139.7   140.9   139.8   140.6   140.3
   139.4   140.2  138.91   138.8  138.71  139.71  138.01  137.41  137.61  136.71
  136.71  136.01  136.71  135.01  134.62  136.52   136.8  136.93  139.03   139.1
   139.1  139.24  139.26  139.26  139.29  139.31  137.21  137.28  137.31  137.04
  136.75  137.91  137.31  137.51  138.41  140.41  140.11  138.49  138.91  139.51
  139.37  139.81  139.51  140.21  140.01  139.31  140.11  140.31     139   141.9
   142.4   141.1   141.4   140.2   140.7   139.7   140.9   139.8   140.6   140.3
   139.4  139.31   138.9   138.3   138.3   139.7     138   137.4   137.6   136.7
   136.7     136   136.7     135  134.61  134.95  135.85   134.9  134.89  132.52
     136  136.14  136.16  131.53  136.41  136.31  136.31  135.87   137.3  137.03
  136.15   137.9   137.3   137.5   138.4   140.4   140.1   137.7   138.9   139.5
   139.2   139.8   139.5   140.2     140   139.3   140.1   140.3     139   141.9
    1926    2076    2121    2151    2186    2271    2361    2391    2436    2676
    2691  2789.9    3241    3261    3291    3321    3966    3981    4131    4181
    4311    4341  4624.5  4669.5  4741.8  4876.2  4921.8 4950.59  4950.7 4970.51
  4970.6    5018 5029.19  5029.3  5040.8  5050.7 5050.81  5095.2  5203.8  5259.5
    5288  5363.3  5378.3  5443.3  5461.6  5608.8  5911.3  5941.3  5956.3  6251.3
  6616.3  6631.3  6696.3  6786.3  6831.3  6846.3  7016.3  7366.3  7426.3  7710.8
   142.4   141.1   141.4   140.2   140.7   139.7   140.9   139.8   140.6   140.3
   139.4   140.2  138.91   138.8  138.71  139.71  138.01  137.41  137.61  136.71
  136.71  136.01  136.71  135.01  134.62  136.52   136.8  136.93  139.03   139.1
   139.1  139.24  139.26  139.26  139.29  139.31  137.21  137.28  137.31  137.04
  136.75  137.91  137.31  137.51  138.41  140.41  140.11  138.49  138.91  139.51
  139.37  139.81  139.51  140.21  140.01  139.31  140.11  140.31     139   141.9
  142.37  141.07  141.37  140.17  140.67  139.67  140.87  139.77  140.57  140.27
  139.37  139.28  138.87  138.27  138.27  139.67  137.97  137.37  137.57  136.67
  136.67  135.97  136.67  134.97  134.58  134.92  135.82  134.87  134.86  132.49
  135.97  136.11  136.13   131.5  136.38  136.28  136.28  135.84  137.27     137
  136.12  137.87  137.27  137.47  138.37  140.37  140.07  137.67  138.87  139.47
  139.17  139.77  139.47  140.17  139.97  139.27  140.07  140.27  138.97  141.87
BR Coef= 1 , 1 , 0 ,1.25, 0 ,,,0.8,0,2,0,
WSPro=,,,, 1 ,,,, 0 ,,,, 0 ,,,,-1 ,-1 ,-1 , 0 , 0 , 0 , 0 , 0
BR U #Sta/Elev= 125
    1926   142.4    2076   141.1    2121   141.4    2151   140.2    2166   140.1
    2186   140.7    2271   139.7    2336   140.4    2346   140.8    2361   140.9
    2391   139.8    2406   140.3    2426   140.2    2436   140.6    2676   140.3
    2691   139.4  2789.9  139.31  3134.9     139    3241   138.9  3259.9  138.33
    3261   138.3    3291   138.3    3321   139.7    3876   138.1    3966     138
    3981   137.4    4131   137.6    4181   136.7    4266   136.3    4311   136.7
    4341     136    4551   136.4    4571   136.6  4589.5   136.4  4624.5   136.7
  4669.5     135  4741.8  134.61  4770.9  134.83  4773.3  134.85    4824  135.17
  4827.3  135.16  4876.2  134.95    4879  135.01  4921.8  135.85  4932.2  135.54
  4949.6  135.02 4950.59   134.9  4950.7  134.89 4950.81  134.88 4970.51  132.52
  4970.6  132.51  4970.7   132.5  4974.7  132.02    4982  125.83  4983.6  125.23
  4986.5  125.22  4999.7   125.2  5014.2  125.15    5018  125.96  5024.1  129.33
  5029.1  131.45 5029.19  131.49  5029.3  131.53  5040.8  136.41  5045.2  136.37
 5050.59  136.31  5050.7  136.31 5050.81  136.31  5095.2  135.87  5097.5  135.91
  5145.7  136.76  5150.6  136.81  5203.8   137.3  5204.9  137.29  5259.5  137.03
  5261.3  136.97    5288  136.15  5363.3   137.9  5378.3   137.3  5443.3   137.5
  5461.6   138.4  5516.8  139.15  5608.8   140.4  5806.3     140  5891.8  140.08
  5911.3   140.1  5921.8  139.26  5941.3   137.7  5946.3   137.9  5956.3   138.9
  6056.8   139.1  6146.8  139.29  6251.3   139.5  6321.8  139.44  6616.3   139.2
  6631.3   139.8  6636.8  139.77  6651.8  139.71  6671.8  139.61  6696.3   139.5
  6786.3   140.2  6796.8  140.15  6806.8  140.11  6831.3     140  6836.8  139.74
  6846.3   139.3  6851.8  139.33  6881.8  139.47  6896.8  139.54  7016.3   140.1
  7031.3   139.7  7051.8  139.74  7096.8  139.82  7106.8  139.84  7121.8  139.86
  7151.8  139.92  7181.8  139.97  7221.8  140.04  7286.8  140.16  7311.8   140.2
  7366.3   140.3  7406.8  139.42  7415.7  139.23  7426.3     139  7710.8   141.9
BR U #Mann= 5
    1926      .2  2789.9      .1  4949.6     .04  5040.8      .1  7415.7      .2
BR U Banks=4949.6,5040.8
BR D #Sta/Elev= 125
    1926  142.37    2076  141.07    2121  141.37    2151  140.17    2166  140.07
    2186  140.67    2271  139.67    2336  140.37    2346  140.77    2361  140.87
    2391  139.77    2406  140.27    2426  140.17    2436  140.57    2676  140.27
    2691  139.37  2789.9  139.28  3134.9  138.97    3241  138.87  3259.9   138.3
    3261  138.27    3291  138.27    3321  139.67    3876  138.07    3966  137.97
    3981  137.37    4131  137.57    4181  136.67    4266  136.27    4311  136.67
    4341  135.97    4551  136.37    4571  136.57  4589.5  136.37  4624.5  136.67
  4669.5  134.97  4741.8  134.58  4770.9   134.8  4773.3  134.82    4824  135.14
  4827.3  135.13  4876.2  134.92    4879  134.98  4921.8  135.82  4932.2  135.51
  4949.6  134.99 4950.59  134.87  4950.7  134.86 4950.81  134.85 4970.51  132.49
  4970.6  132.48  4970.7  132.47  4974.7  131.99    4982   125.8  4983.6   125.2
  4986.5  125.19  4999.7  125.17  5014.2  125.12    5018  125.93  5024.1   129.3
  5029.1  131.42 5029.19  131.46  5029.3   131.5  5040.8  136.38  5045.2  136.34
 5050.59  136.28  5050.7  136.28 5050.81  136.28  5095.2  135.84  5097.5  135.88
  5145.7  136.73  5150.6  136.78  5203.8  137.27  5204.9  137.26  5259.5     137
  5261.3  136.94    5288  136.12  5363.3  137.87  5378.3  137.27  5443.3  137.47
  5461.6  138.37  5516.8  139.12  5608.8  140.37  5806.3  139.97  5891.8  140.05
  5911.3  140.07  5921.8  139.23  5941.3  137.67  5946.3  137.87  5956.3  138.87
  6056.8  139.07  6146.8  139.26  6251.3  139.47  6321.8  139.41  6616.3  139.17
  6631.3  139.77  6636.8  139.74  6651.8  139.68  6671.8  139.58  6696.3  139.47
  6786.3  140.17  6796.8  140.12  6806.8  140.08  6831.3  139.97  6836.8  139.71
  6846.3  139.27  6851.8   139.3  6881.8  139.44  6896.8  139.51  7016.3  140.07
  7031.3  139.67  7051.8  139.71  7096.8  139.79  7106.8  139.81  7121.8  139.83
  7151.8  139.89  7181.8  139.94  7221.8  140.01  7286.8  140.13  7311.8  140.17
  7366.3  140.27  7406.8  139.39  7415.7   139.2  7426.3  138.97  7710.8  141.87
BR D #Mann= 5
    1926      .2  2789.9      .1  4949.6     .04  5040.8      .1  7415.7      .2
BR D Banks=4949.6,5040.8
BC Design=,, 0 ,, 0 ,,,,,,
BC HTab HWMax=142.39

Type RM Length L Ch R = 1 ,7495.7  ,70.8,70.8,70.8
BEGIN DESCRIPTION:
Downstream Section of Bridge/Culvert/Weir
END DESCRIPTION:
XS GIS Cut Line= 6
      2978031.56     13847180.55      2975115.36     13847125.16
      2974863.34      13847077.9      2974730.17     13847063.58
      2974446.71     13847054.25       2972252.9      13847020.8
#Sta/Elev= 30
    1926  142.31    2271  139.61    2361  140.81    2391  139.71    2436  140.51
  2789.9  139.22    3291  138.21    3321  139.61    4131  137.51    4341  135.91
  4624.5  136.61  4669.5  134.91  4741.8  134.52  4921.8  135.76  4949.6  134.93
  4974.7  131.93  4983.6  125.14  5014.2  125.06  5040.8  136.32  5203.8  137.21
    5288  136.06  5608.8  140.31  5911.3  140.01  5941.3  137.61  5956.3  138.81
  6786.3  140.11  6846.3  139.21  7366.3  140.21  7415.7  139.14  7710.8  141.81
#Mann= 5 , 1 , 0
    1926      .2       0  2789.9      .1       0  4949.6     .04       0
  5040.8      .1       0  7415.7      .2       0
#XS Ineff= 2 , 0
       0    4780     141    5220       0     141
Permanent Ineff=
       F       F
Bank Sta=4949.6,5040.8
Exp/Cntr=0.5,0.3

Type RM Length L Ch R = 1 ,7424.9  ,33,33,33
BEGIN DESCRIPTION:
Upstream Section of Bridge/Culvert/Weir
END DESCRIPTION:
XS GIS Cut Line= 4
       2977254.2     13847073.83      2975210.68     13847041.09
      2974648.94     13847025.56      2972275.18     13846976.63
#Sta/Elev= 30
  2676.1  141.86  2770.5  140.74  3130.1  141.66  3160.1  139.66  3490.1  137.86
  3505.1  139.56  3565.1  140.76  3595.1  138.96  4035.1  137.26  4075.1  138.76
  4105.1  136.56  4225.1  135.76  4270.1  138.66  4300.1  138.76  4330.1  136.06
  4692.9  140.15  4719.2  137.55  4947.2  135.82  4970.9  131.74  4980.2  125.15
    4987  124.61  5019.1  124.91  5055.4  137.06  5101.4  138.32  5454.7  136.96
  6565.2  140.46  6600.2  137.96  7406.7  137.56    7507  139.62  7656.1  141.66
#Mann= 5 , 1 , 0
  2676.1      .2       0  2770.5      .1       0  4947.2     .04       0
  5055.4      .1       0    7507      .2       0
#XS Ineff= 2 , 0
       0    4935     141    5064       0     141
Permanent Ineff=
       F       F
Bank Sta=4947.2,5055.4
Exp/Cntr=0.5,0.3

Type RM Length L Ch R = 3 ,7408.4  ,,,
BEGIN DESCRIPTION:
MISSOURI KANSAS TEXAS RAILROAD
Structure ID: T00-6
END DESCRIPTION:
Bridge Culvert--1,0,-1,-1, 0
Deck Dist Width WeirC Skew NumUp NumDn MinLoCord MaxHiCord MaxSubmerge Is_Ogee
10,13,2.6,0, 57, 57, , , 0.95, 0, 1,1,,
  2676.1  2695.5  2755.1  2895.1  3085.1  3115.1  3130.1  3145.1  3160.1  3330.1
  3375.1  3390.1  3490.1  3505.1  3520.1  3535.1  3550.1  3565.1  3580.1  3595.1
  4035.1  4060.1  4075.1  4105.1  4225.1  4255.1  4270.1  4300.1  4315.1  4330.1
  4692.9  4719.2  4771.6  4831.6  4891.7 4946.51  4946.6 5056.99  5057.1  5057.2
  5101.4  5151.3  5209.2  5270.1  5305.4  5454.7  6530.2  6565.2  6580.2  6590.2
  6595.2  6600.2  7406.7  7436.7  7575.9  7590.5  7656.1
   141.8   141.6  141.53  141.37  141.15  141.61  141.61  141.11  141.06  140.86
  140.81  140.79   140.7   140.7   140.7   140.7   140.7   140.7   140.7   140.7
  140.68  140.68  140.68  140.68  140.68  140.67  140.67  140.67  140.67  140.67
  140.66  140.66  140.63  140.78  140.81  140.85  140.85  140.93  140.93  140.93
  141.02  141.09  141.17  141.23  141.22   141.2  141.02  141.01  141.01  141.01
  141.01  141.01  140.84  140.83   140.8   140.8   141.6
   141.8  141.53   140.7   140.5   140.6   141.6   141.6   141.1   139.6   138.9
   138.3   138.5   137.8   139.5   139.7   139.4   140.4   140.7   140.1   138.9
   137.2   138.7   138.7   136.5   135.7     137   138.6   138.7   136.5     136
  140.09  137.49  137.03  135.67  136.44  135.77  137.45  137.53  137.05  137.05
  138.26  137.59  138.15  137.77  138.38   136.9   139.4   140.4   140.1   139.2
   138.9   137.9   137.5   138.8   140.3  140.54   141.6
  2676.1  2695.5  2755.1  2895.1  3085.1  3115.1  3130.1  3145.1  3160.1  3330.1
  3375.1  3390.1  3490.1  3505.1  3520.1  3535.1  3550.1  3565.1  3580.1  3595.1
  4035.1  4060.1  4075.1  4105.1  4225.1  4255.1  4270.1  4300.1  4315.1  4330.1
  4692.9  4719.2  4771.6  4831.6  4891.7 4946.51  4946.6 5056.99  5057.1  5057.2
  5101.4  5151.3  5209.2  5270.1  5305.4  5454.7  6530.2  6565.2  6580.2  6590.2
  6595.2  6600.2  7406.7  7436.7  7575.9  7590.5  7656.1
   141.8   141.6  141.53  141.37  141.15  141.61  141.61  141.11  141.06  140.86
  140.81  140.79   140.7   140.7   140.7   140.7   140.7   140.7   140.7   140.7
  140.68  140.68  140.68  140.68  140.68  140.67  140.67  140.67  140.67  140.67
  140.66  140.66  140.63  140.78  140.81  140.85  140.85  140.93  140.93  140.93
  141.02  141.09  141.17  141.23  141.22   141.2  141.02  141.01  141.01  141.01
  141.01  141.01  140.84  140.83   140.8   140.8   141.6
  141.76  141.49  140.66  140.46  140.56  141.56  141.56  141.06  139.56  138.86
  138.26  138.46  137.76  139.46  139.66  139.36  140.36  140.66  140.06  138.86
  137.16  138.66  138.66  136.46  135.66  136.96  138.56  138.66  136.46  135.96
  140.05  137.45  136.99  135.63   136.4  135.73  137.41  137.49  137.01  137.01
  138.22  137.55  138.11  137.73  138.34  136.86  139.36  140.36  140.06  139.16
  138.86  137.86  137.46  138.76  140.26   140.5  141.56
Pier Skew, UpSta & Num, DnSta & Num=  ,4960.8, 2 ,4960.8, 2 , 0 , 0 , 0 ,,
       1       1
  131.68  138.46
       1       1
  131.64  138.42
Pier Skew, UpSta & Num, DnSta & Num=  ,4973.7, 2 ,4973.7, 2 , 0 , 0 , 0 ,,
       1       1
   129.1  138.47
       1       1
  129.06  138.43
Pier Skew, UpSta & Num, DnSta & Num=  ,4987.8, 2 ,4987.8, 2 , 0 , 0 , 0 ,,
       1       1
  123.72  138.48
       1       1
  123.67  138.44
Pier Skew, UpSta & Num, DnSta & Num=  ,5000.9, 2 ,5000.9, 2 , 0 , 0 , 0 ,,
       1       1
   123.7  138.49
       1       1
  123.66  138.45
Pier Skew, UpSta & Num, DnSta & Num=  ,5015.6, 2 ,5015.6, 2 , 0 , 0 , 0 ,,
       1       1
  123.59   138.5
       1       1
  123.55  138.46
Pier Skew, UpSta & Num, DnSta & Num=  ,5028.8, 2 ,5028.8, 2 , 0 , 0 , 0 ,,
       1       1
  126.24  138.51
       1       1
   126.2  138.47
Pier Skew, UpSta & Num, DnSta & Num=  ,5042.8, 2 ,5042.8, 2 , 0 , 0 , 0 ,,
       1       1
  131.77  138.52
       1       1
  131.73  138.48
Abutment Skew #Up #Dn= , 2 , 2
  4946.4  4978.1
  137.45  126.61
  4946.4  4978.1
  137.41  126.57
Abutment Skew #Up #Dn= , 2 , 2
  5024.3 5057.19
   126.4  137.53
  5024.3 5057.19
  126.36  137.49
BR Coef= 1 , 1 , 0 ,1.25, 0 ,,,0.8,0,2,0,
WSPro=,,,, 1 ,,,, 0 ,,,, 0 ,,,,-1 ,-1 ,-1 , 0 , 0 , 0 , 0 , 0
BR U #Sta/Elev= 90
  2676.1   141.8  2695.5  141.53  2755.1   140.7  2770.5  140.68  2895.1   140.5
  3085.1   140.6  3115.1   141.6  3130.1   141.6  3145.1   141.1  3160.1   139.6
  3330.1   138.9  3375.1   138.3  3390.1   138.5  3470.5  137.94  3490.1   137.8
  3505.1   139.5  3520.1   139.7  3535.1   139.4  3550.1   140.4  3565.1   140.7
  3580.1   140.1  3595.1   138.9  4035.1   137.2  4060.1   138.7  4075.1   138.7
  4105.1   136.5  4225.1   135.7  4255.1     137  4270.1   138.6  4300.1   138.7
  4315.1   136.5  4330.1     136  4692.9  140.09  4719.2  137.49  4719.8  137.48
  4771.6  137.03  4772.9     137  4831.6  135.67  4832.3  135.68  4891.7  136.44
  4894.3  136.41  4946.4  135.77 4946.51  135.77  4946.6  135.77  4947.2  135.76
  4960.8  132.73  4970.9  131.68  4973.7  130.55    4978  126.68  4978.1  126.61
  4980.2  125.09    4987  124.55  4987.8  124.99  5000.9  124.69  5001.6  124.84
  5015.6  124.58  5019.1  124.85  5019.7  125.04  5024.2  126.37  5024.3   126.4
  5028.8  127.34  5039.4  131.87  5042.8  132.92  5055.4     137 5056.99  137.04
  5057.1  137.05  5057.2  137.05  5101.4  138.26  5102.3  138.25  5151.2  137.59
  5151.3  137.59  5209.2  138.15  5209.5  138.15  5269.8  137.77  5270.1  137.77
  5305.4  138.38  5454.7   136.9  6530.2   139.4  6565.2   140.4  6580.2   140.1
  6590.2   139.2  6595.2   138.9  6600.2   137.9  7246.8  137.58  7406.7   137.5
  7436.7   138.8    7507  139.56  7575.9   140.3  7590.5  140.54  7656.1   141.6
BR U #Mann= 5
  2676.1      .2  2770.5      .1  4947.2     .04  5055.4      .1    7507      .2
BR U Banks=4947.2,5055.4
BR D #Sta/Elev= 90
  2676.1  141.76  2695.5  141.49  2755.1  140.66  2770.5  140.64  2895.1  140.46
  3085.1  140.56  3115.1  141.56  3130.1  141.56  3145.1  141.06  3160.1  139.56
  3330.1  138.86  3375.1  138.26  3390.1  138.46  3470.5   137.9  3490.1  137.76
  3505.1  139.46  3520.1  139.66  3535.1  139.36  3550.1  140.36  3565.1  140.66
  3580.1  140.06  3595.1  138.86  4035.1  137.16  4060.1  138.66  4075.1  138.66
  4105.1  136.46  4225.1  135.66  4255.1  136.96  4270.1  138.56  4300.1  138.66
  4315.1  136.46  4330.1  135.96  4692.9  140.05  4719.2  137.45  4719.8  137.44
  4771.6  136.99  4772.9  136.96  4831.6  135.63  4832.3  135.64  4891.7   136.4
  4894.3  136.37  4946.4  135.73 4946.51  135.73  4946.6  135.73  4947.2  135.72
  4960.8  132.69  4970.9  131.64  4973.7  130.51    4978  126.64  4978.1  126.57
  4980.2  125.05    4987  124.51  4987.8  124.95  5000.9  124.65  5001.6   124.8
  5015.6  124.54  5019.1  124.81  5019.7     125  5024.2  126.33  5024.3  126.36
  5028.8   127.3  5039.4  131.83  5042.8  132.88  5055.4  136.96 5056.99     137
  5057.1  137.01  5057.2  137.01  5101.4  138.22  5102.3  138.21  5151.2  137.55
  5151.3  137.55  5209.2  138.11  5209.5  138.11  5269.8  137.73  5270.1  137.73
  5305.4  138.34  5454.7  136.86  6530.2  139.36  6565.2  140.36  6580.2  140.06
  6590.2  139.16  6595.2  138.86  6600.2  137.86  7246.8  137.54  7406.7  137.46
  7436.7  138.76    7507  139.52  7575.9  140.26  7590.5   140.5  7656.1  141.56
BR D #Mann= 5
  2676.1      .2  2770.5      .1  4947.2     .04  5055.4      .1    7507      .2
BR D Banks=4947.2,5055.4
BC Design=,, 0 ,, 0 ,,,,,,
BC HTab HWMax=141.86

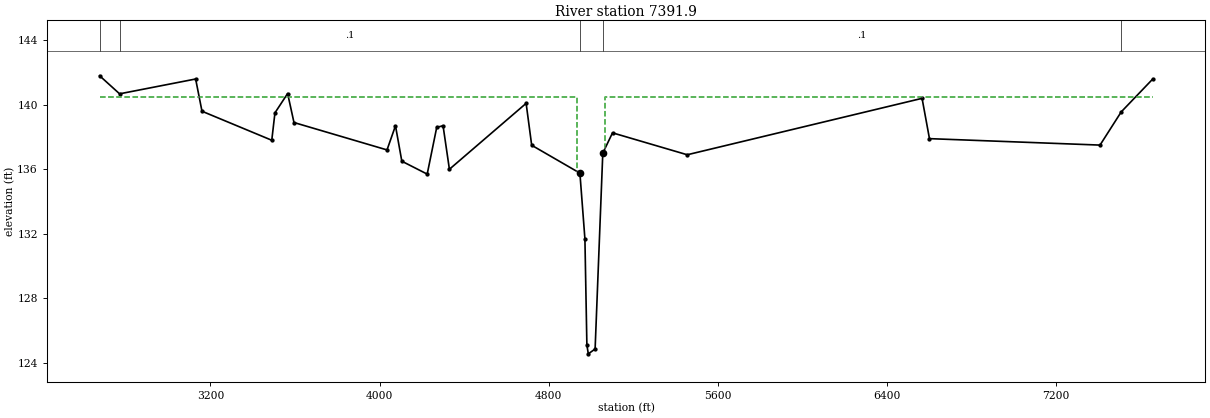
Type RM Length L Ch R = 1 ,7391.9  ,43.9,43.9,43.9
BEGIN DESCRIPTION:
Downstream Section of Bridge/Culvert/Weir
END DESCRIPTION:
XS GIS Cut Line= 4
      2977244.82     13847042.19       2975201.3     13847009.45
      2974639.56     13846993.92      2972265.81     13846944.99
#Sta/Elev= 30
  2676.1  141.79  2770.5  140.67  3130.1  141.59  3160.1  139.59  3490.1  137.79
  3505.1  139.49  3565.1  140.69  3595.1  138.89  4035.1  137.19  4075.1  138.69
  4105.1  136.49  4225.1  135.69  4270.1  138.59  4300.1  138.69  4330.1  135.99
  4692.9  140.08  4719.2  137.48  4947.2  135.75  4970.9  131.67  4980.2  125.08
    4987  124.54  5019.1  124.84  5055.4  136.99  5101.4  138.25  5454.7  136.89
  6565.2  140.39  6600.2  137.89  7406.7  137.49    7507  139.55  7656.1  141.59
#Mann= 5 , 1 , 0
  2676.1      .2       0  2770.5      .1       0  4947.2     .04       0
  5055.4      .1       0    7507      .2       0
#XS Ineff= 2 , 0
       0    4935   140.5    5064       0   140.5
Permanent Ineff=
       F       F
Bank Sta=4947.2,5055.4
Exp/Cntr=0.5,0.3