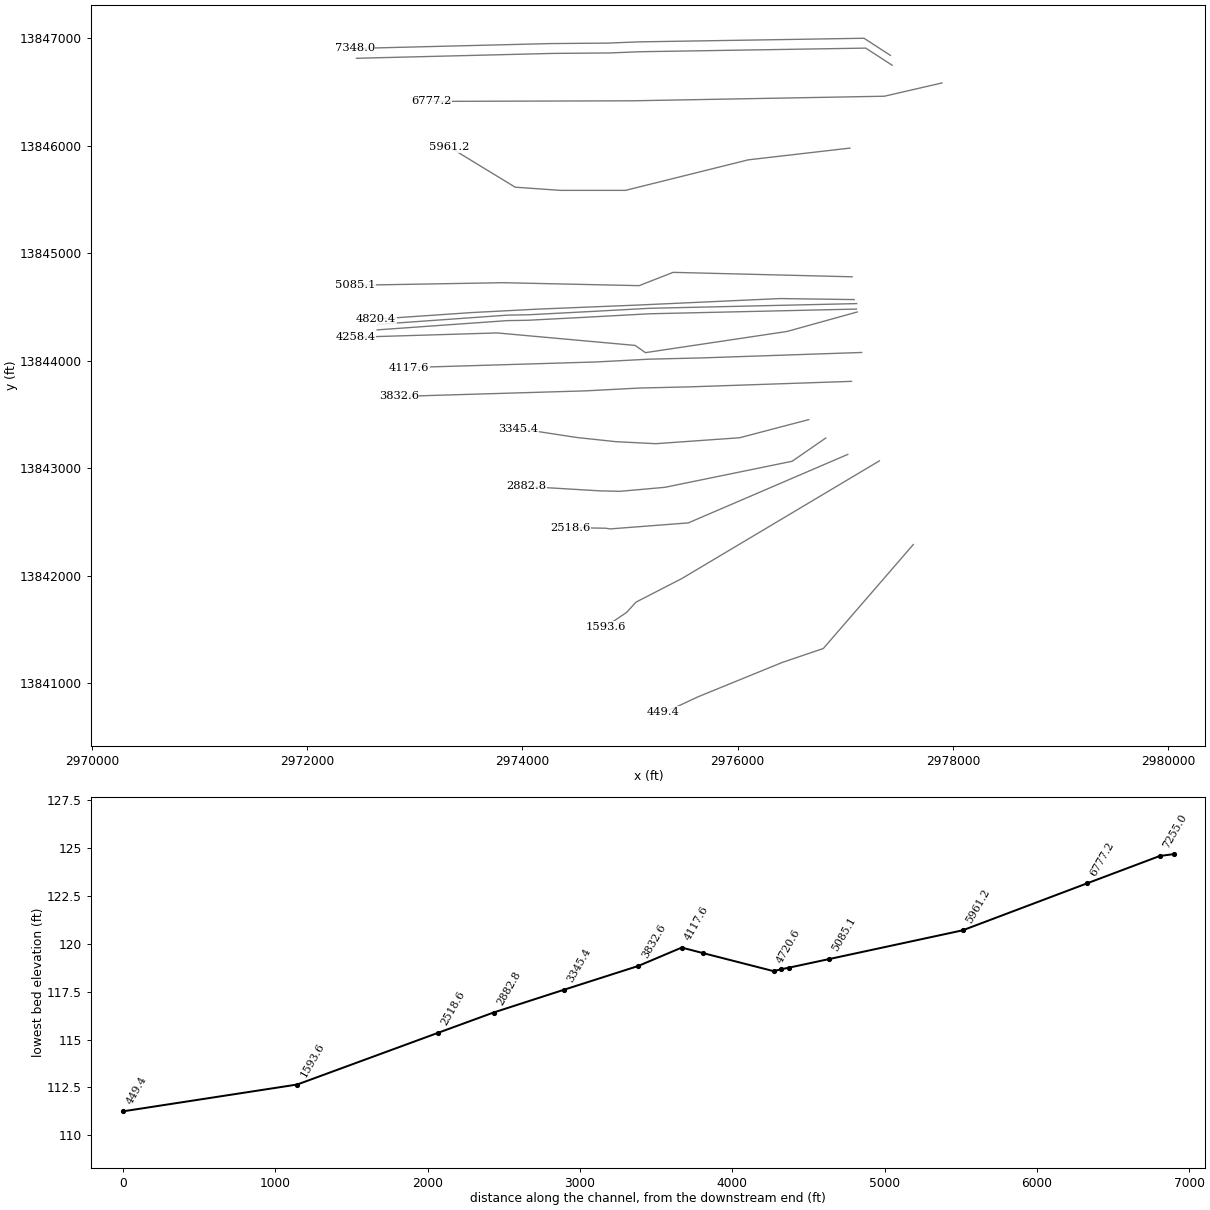
HEC-RAS study T100-00-00.PRJ: T100-00-00

--- T100-00-00.g01 (geometry) --- (continued)

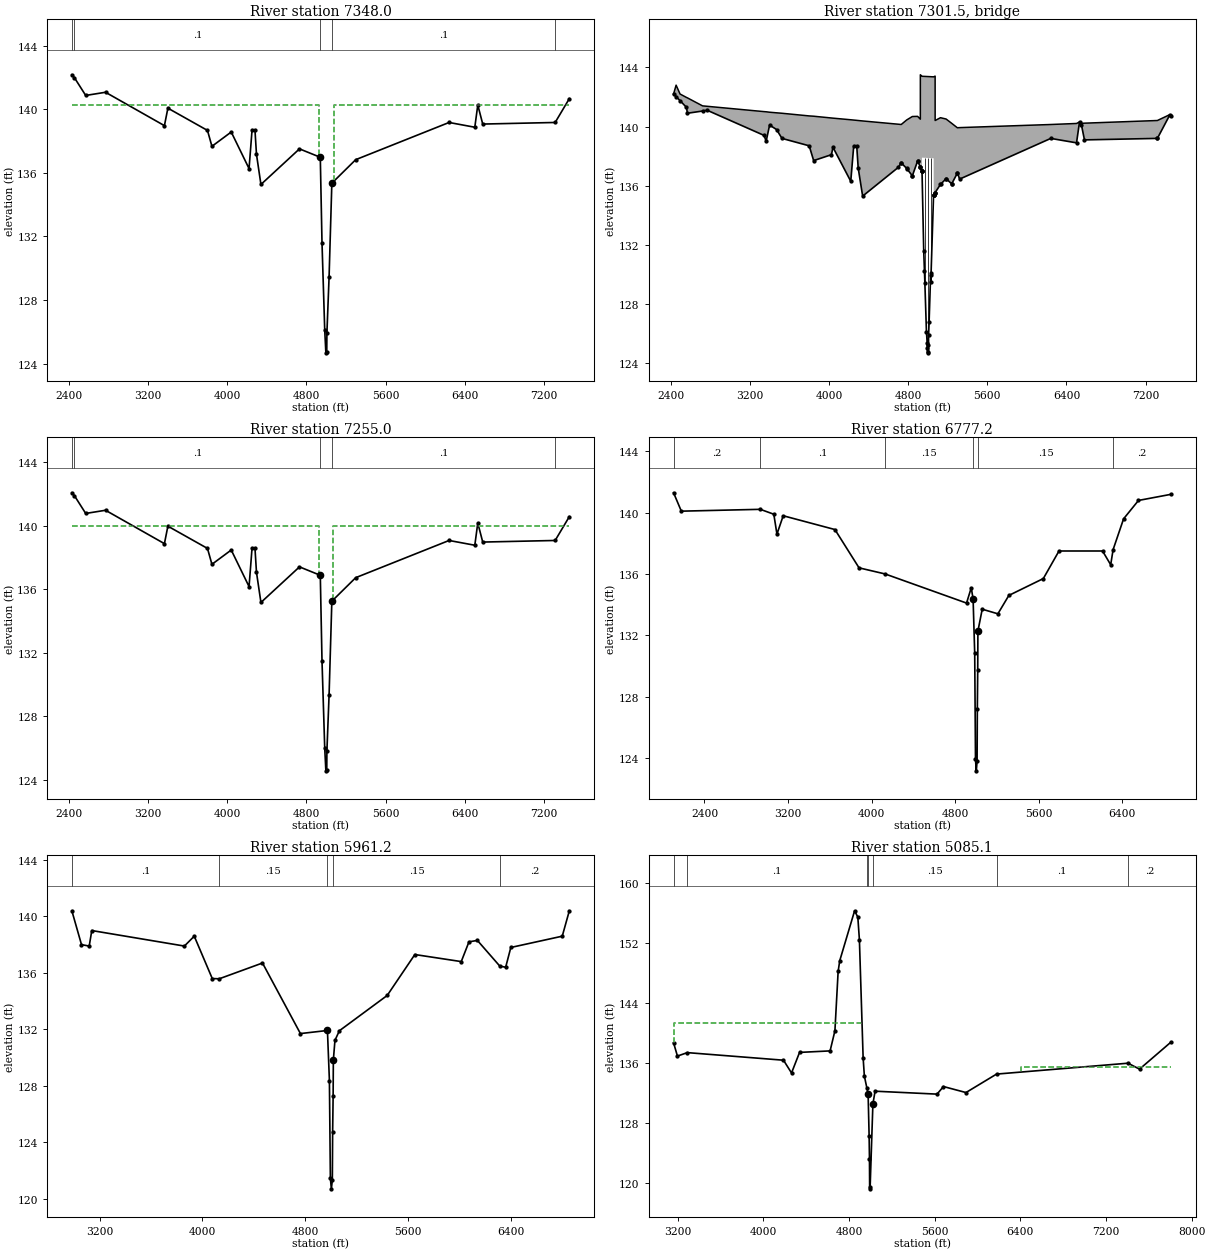
Type RM Length L Ch R = 1 ,7348.0  ,93,93,93
BEGIN DESCRIPTION:
Upstream Section of Bridge/Culvert/Weir
END DESCRIPTION:
XS GIS Cut Line= 6
      2977419.52      13846841.4      2977174.09     13847000.47
      2975078.76     13846966.78      2974790.95     13846955.33
      2974264.09     13846951.08      2972442.07     13846905.79
#Sta/Elev= 30
  2430.9  142.17  2456.5  141.99  2570.9  140.87    2771  141.07    3366  138.97
    3401  140.07    3801  138.67    3846  137.67    4041  138.57    4221  136.27
    4251  138.67    4281  138.67    4296  137.17    4341  135.27  4730.5  137.51
  4940.7  136.98    4958  131.59  4985.4  126.12  4997.1  124.68    5006  124.71
  5007.4   125.9  5029.4  129.44  5057.4  135.35  5298.4  136.83  6241.7  139.17
  6501.7  138.87  6531.7  140.27  6581.7  139.07  7313.3  139.17  7456.5  140.67
#Mann= 5 , 1 , 0
  2430.9      .2       0  2456.5      .1       0  4940.7     .04       0
  5057.4      .1       0  7313.3      .2       0
#XS Ineff= 2 , 0
       0    4930   140.3    5080       0   140.3
Permanent Ineff=
       F       F
Bank Sta=4940.7,5057.4
Exp/Cntr=0.5,0.3

Type RM Length L Ch R = 3 ,7301.5  ,,,
BEGIN DESCRIPTION:
U.S. ROUTE 90
Structure ID: T00-5
END DESCRIPTION:
Bridge Culvert--1,0,-1,-1, 0
Deck Dist Width WeirC Skew NumUp NumDn MinLoCord MaxHiCord MaxSubmerge Is_Ogee
10,73,2.6,0, 48, 48, , , 0.95, 0, 1,1,,
  2430.9  2456.5  2496.5  2560.9  2570.9  2723.4    2771    3346    3366    3401
    3471    3526    3801    3846    4026    4041    4221    4251    4281    4296
    4341  4700.7  4730.5  4786.4  4842.9  4896.4 4923.89    4924 4924.11 4940.11
  4940.2 5058.69  5058.8  5073.3 5073.41  5127.2    5184  5240.6  5297.6  5320.8
  6241.7  6501.7  6531.7  6551.7  6581.7  7318.4  7444.9  7456.5
   142.2   142.8   142.2  141.97  141.94   141.4  141.37  141.01     141  140.97
  140.93   140.9  140.72   140.7  140.58  140.57  140.46  140.44  140.42  140.41
  140.38  140.16  140.14  140.45  140.68  140.69   140.5   143.5   143.5   143.4
   143.4  143.36  143.36  143.41  140.41   140.6  140.51  140.22  139.92  139.93
  140.14  140.21  140.31  140.22  140.23  140.41  140.81   140.7
   142.2  142.02  141.75   141.3   140.9  141.05   141.1   139.4     139   140.1
   139.8   139.2   138.7   137.7   138.1   138.6   136.3   138.7   138.7   137.2
   135.3  137.24  137.54  137.17  136.67  137.68  137.26  137.26  137.26  137.02
   137.9  137.86  135.39  135.54  135.54  136.09  136.48  136.13  136.85  136.45
   139.2   138.9   140.3   140.1   139.1   139.2   140.8   140.7
  2430.9  2456.5  2496.5  2560.9  2570.9  2723.4    2771    3346    3366    3401
    3471    3526    3801    3846    4026    4041    4221    4251    4281    4296
    4341  4700.7  4730.5  4786.4  4842.9  4896.4 4923.89    4924 4924.11 4940.11
  4940.2 5058.69  5058.8  5073.3 5073.41  5127.2    5184  5240.6  5297.6  5320.8
  6241.7  6501.7  6531.7  6551.7  6581.7  7318.4  7444.9  7456.5
   142.2   142.8   142.2  141.97  141.94   141.4  141.37  141.01     141  140.97
  140.93   140.9  140.72   140.7  140.58  140.57  140.46  140.44  140.42  140.41
  140.38  140.16  140.14  140.45  140.68  140.69   140.5   143.5   143.5   143.4
   143.4  143.36  143.36  143.41  140.41   140.6  140.51  140.22  139.92  139.93
  140.14  140.21  140.31  140.22  140.23  140.41  140.81   140.7
   142.1  141.92  141.65   141.2   140.8  140.95     141   139.3   138.9     140
   139.7   139.1   138.6   137.6     138   138.5   136.2   138.6   138.6   137.1
   135.2  137.14  137.44  137.07  136.57  137.58  137.16  137.16  137.16  136.92
   137.8  137.76  135.29  135.44  135.44  135.99  136.38  136.03  136.75  136.35
   139.1   138.8   140.2     140     139   139.1   140.7   140.6
Pier Skew, UpSta & Num, DnSta & Num=  ,4969.6, 2 ,4969.6, 2 , 0 , 0 , 0 ,,
     1.4     1.4
  128.28  138.89
     1.4     1.4
  128.18  138.79
Pier Skew, UpSta & Num, DnSta & Num=  ,4999.4, 2 ,4999.4, 2 , 0 , 0 , 0 ,,
     1.4     1.4
  124.09  138.88
     1.4     1.4
  123.99  138.78
Pier Skew, UpSta & Num, DnSta & Num=  ,5029.4, 2 ,5029.4, 2 , 0 , 0 , 0 ,,
     1.4     1.4
  128.62  138.87
     1.4     1.4
  128.52  138.77
Abutment Skew #Up #Dn= , 2 , 2
    4940  4965.4
   137.9  130.22
    4940  4965.4
   137.8  130.12
Abutment Skew #Up #Dn= , 2 , 2
  5032.3 5058.89
  130.08  137.86
  5032.3 5058.89
  129.98  137.76
BR Coef= 1 , 1 , 0 ,1.25, 0 ,,,0.8,0,2,0,
WSPro=,,,, 1 ,,,, 0 ,,,, 0 ,,,,-1 ,-1 ,-1 , 0 , 0 , 0 , 0 , 0
BR U #Sta/Elev= 76
  2430.9   142.2  2456.5  142.02  2496.5  141.75  2560.9   141.3  2570.9   140.9
  2723.4  141.05    2771   141.1    3346   139.4    3366     139    3401   140.1
    3471   139.8    3526   139.2    3801   138.7    3846   137.7    4026   138.1
    4041   138.6    4221   136.3    4251   138.7    4281   138.7    4296   137.2
    4341   135.3  4700.7  137.24  4730.5  137.54  4731.1  137.54  4786.4  137.17
  4787.1  137.16  4842.9  136.67  4843.1  136.67  4896.1  137.67  4896.4  137.68
 4923.89  137.26    4924  137.26 4924.11  137.26    4940  137.02 4940.11  137.02
  4940.2  137.02  4940.7  137.01    4958  131.62  4965.4  130.22  4969.6  129.43
  4985.4  126.15  4992.7  125.39  4994.1  125.07  4997.1  124.71  4999.4  125.25
    5006  124.74  5007.4  125.93  5012.3  126.78  5027.6  129.96  5029.4  129.47
  5032.3  130.08  5057.4  135.38 5058.69  135.39  5058.8  135.39  5058.9   135.4
 5073.19  135.54  5073.3  135.54 5073.41  135.54  5127.2  136.09  5128.5   136.1
  5182.9  136.47    5184  136.48  5240.5  136.13  5240.6  136.13  5297.6  136.85
  5298.4  136.86  5320.8  136.45  6241.7   139.2  6501.7   138.9  6531.7   140.3
  6551.7   140.1  6581.7   139.1  7313.3   139.2  7318.4   139.2  7444.9   140.8
  7456.5   140.7
BR U #Mann= 5
  2430.9      .2  2456.5      .1  4940.7     .04  5057.4      .1  7313.3      .2
BR U Banks=4940.7,5057.4
BR D #Sta/Elev= 76
  2430.9   142.1  2456.5  141.92  2496.5  141.65  2560.9   141.2  2570.9   140.8
  2723.4  140.95    2771     141    3346   139.3    3366   138.9    3401     140
    3471   139.7    3526   139.1    3801   138.6    3846   137.6    4026     138
    4041   138.5    4221   136.2    4251   138.6    4281   138.6    4296   137.1
    4341   135.2  4700.7  137.14  4730.5  137.44  4731.1  137.44  4786.4  137.07
  4787.1  137.06  4842.9  136.57  4843.1  136.57  4896.1  137.57  4896.4  137.58
 4923.89  137.16    4924  137.16 4924.11  137.16    4940  136.92 4940.11  136.92
  4940.2  136.92  4940.7  136.91    4958  131.52  4965.4  130.12  4969.6  129.33
  4985.4  126.05  4992.7  125.29  4994.1  124.97  4997.1  124.61  4999.4  125.15
    5006  124.64  5007.4  125.83  5012.3  126.68  5027.6  129.86  5029.4  129.37
  5032.3  129.98  5057.4  135.28 5058.69  135.29  5058.8  135.29  5058.9   135.3
 5073.19  135.44  5073.3  135.44 5073.41  135.44  5127.2  135.99  5128.5     136
  5182.9  136.37    5184  136.38  5240.5  136.03  5240.6  136.03  5297.6  136.75
  5298.4  136.76  5320.8  136.35  6241.7   139.1  6501.7   138.8  6531.7   140.2
  6551.7     140  6581.7     139  7313.3   139.1  7318.4   139.1  7444.9   140.7
  7456.5   140.6
BR D #Mann= 5
  2430.9      .2  2456.5      .1  4940.7     .04  5057.4      .1  7313.3      .2
BR D Banks=4940.7,5057.4
BC Design=,, 0 ,, 0 ,,,,,,
BC HTab HWMax=142.17

Type RM Length L Ch R = 1 ,7255.0  ,477.8,477.8,477.8
BEGIN DESCRIPTION:
Downstream Section of Bridge/Culvert/Weir
END DESCRIPTION:
XS GIS Cut Line= 6
      2977435.41     13846749.77      2977189.99     13846908.83
      2975094.66     13846875.14      2974806.85     13846863.69
      2974279.99     13846859.44      2972457.96     13846814.15
#Sta/Elev= 30
  2430.9  142.07  2456.5  141.89  2570.9  140.77    2771  140.97    3366  138.87
    3401  139.97    3801  138.57    3846  137.57    4041  138.47    4221  136.17
    4251  138.57    4281  138.57    4296  137.07    4341  135.17  4730.5  137.41
  4940.7  136.88    4958  131.49  4985.4  126.02  4997.1  124.58    5006  124.61
  5007.4   125.8  5029.4  129.34  5057.4  135.25  5298.4  136.73  6241.7  139.07
  6501.7  138.77  6531.7  140.17  6581.7  138.97  7313.3  139.07  7456.5  140.57
#Mann= 5 , 1 , 0
  2430.9      .2       0  2456.5      .1       0  4940.7     .04       0
  5057.4      .1       0  7313.3      .2       0
#XS Ineff= 2 , 0
       0    4930     140    5070       0     140
Permanent Ineff=
       F       F
Bank Sta=4940.7,5057.4
Exp/Cntr=0.5,0.3

Type RM Length L Ch R = 1 ,6777.2  ,751.1,816,832.8
BEGIN DESCRIPTION:
Cross Section 6777.2-Interpolated
END DESCRIPTION:
XS GIS Cut Line= 4
      2977898.37     13846584.63       2977363.4      13846461.2
      2975020.93      13846418.6        2973150.     13846413.12
#Sta/Elev= 30
  2104.3   141.3  2178.6   140.1  2934.6  140.22    3064   139.9    3094   138.6
    3154   139.8  3649.1   138.9  3880.1   136.4  4130.2     136  4909.3   134.1
  4954.3   135.1    4972  134.37  4987.4  130.81  4994.9   123.9  5002.6  123.15
  5010.2  123.77  5012.5  127.19  5016.3  129.73    5018  132.27  5059.3   133.7
  5209.3   133.4  5314.3   134.6  5644.3   135.7  5794.3   137.5  6211.4   137.5
  6289.3   136.6  6312.4  137.59  6412.8   139.6  6555.4   140.8  6867.1   141.2
#Mann= 6 , 1 , 0
  2104.3      .2       0  2934.6      .1       0  4130.2     .15       0
    4972     .04       0    5018     .15       0  6312.4      .2       0
Bank Sta=4972,5018
Exp/Cntr=0.3,0.1

Type RM Length L Ch R = 1 ,5961.2  ,932.2,876.1,869.2
BEGIN DESCRIPTION:
Cross Section 5961.2
END DESCRIPTION:
XS GIS Cut Line= 6
      2977043.09     13845978.59      2976097.63     13845869.18
      2974957.96     13845585.32      2974352.11     13845585.32
      2973932.68     13845614.98      2973322.24     13845987.27
#Sta/Elev= 30
  2984.6   140.4  3059.6     138  3119.6   137.9  3139.6     139  3859.6   137.9
  3936.4   138.6  4076.4   135.6  4130.2  135.58    4467   136.7    4762   131.7
    4972  131.92  4987.4  128.36  4994.9  121.45  5002.6   120.7  5010.2  121.32
  5012.5  124.74  5016.3  127.28    5018  129.82  5030.5  131.22  5064.9   131.9
  5436.7   134.4  5651.7   137.3  6012.6   136.8  6072.6   138.2    6138   138.3
  6312.4  136.48    6358   136.4    6398   137.8    6798   138.6    6853   140.4
#Mann= 5 , 1 , 0
  2984.6      .1       0  4130.2     .15       0    4972     .04       0
    5018     .15       0  6312.4      .2       0
#XS Ineff= 2 , 0
       0    4467   136.7               0
Permanent Ineff=
       F       F
Bank Sta=4972,5018
Exp/Cntr=0.3,0.1

Type RM Length L Ch R = 1 ,5085.1  ,275.3,264.7,206.6
BEGIN DESCRIPTION:
Cross Section 5085.1-Interpolated
END DESCRIPTION:
XS GIS Cut Line= 5
      2977063.74     13844781.32      2975400.49     13844822.56
      2975084.34     13844698.84      2973819.72     13844726.33
      2972443.54     13844702.61
#Sta/Elev= 30
  3162.9  138.66  3198.9  136.89  3291.3  137.35  4189.2  136.34  4264.2  134.64
  4339.2  137.38  4624.3  137.58  4669.3  140.26  4699.3  148.16  4714.3   149.6
  4853.1  156.25  4883.2   155.4  4897.9  152.39  4932.7  136.67  4944.2  134.23
  4967.3  132.66 4979.15  131.89 4988.65  126.23 4991.85  123.18 4993.65   119.2
 4998.05  119.39 5023.85  130.51  5044.3  132.21  5622.8  131.82  5682.8  132.83
  5892.9  132.03  6178.3  134.49  7405.9  135.94  7513.3  135.15  7807.5  138.76
#Mann= 7 , 1 , 0
  3162.9      .2       0  3291.3      .1       0  4967.3     .15       0
 4979.15     .04       0 5023.85     .15       0  6178.3      .1       0
  7405.9      .2       0
#XS Ineff= 2 , 0
       0  4921.1  141.24    6403       0  135.42
Permanent Ineff=
       F       F
Bank Sta=4979.15,5023.85
Exp/Cntr=0.3,0.1

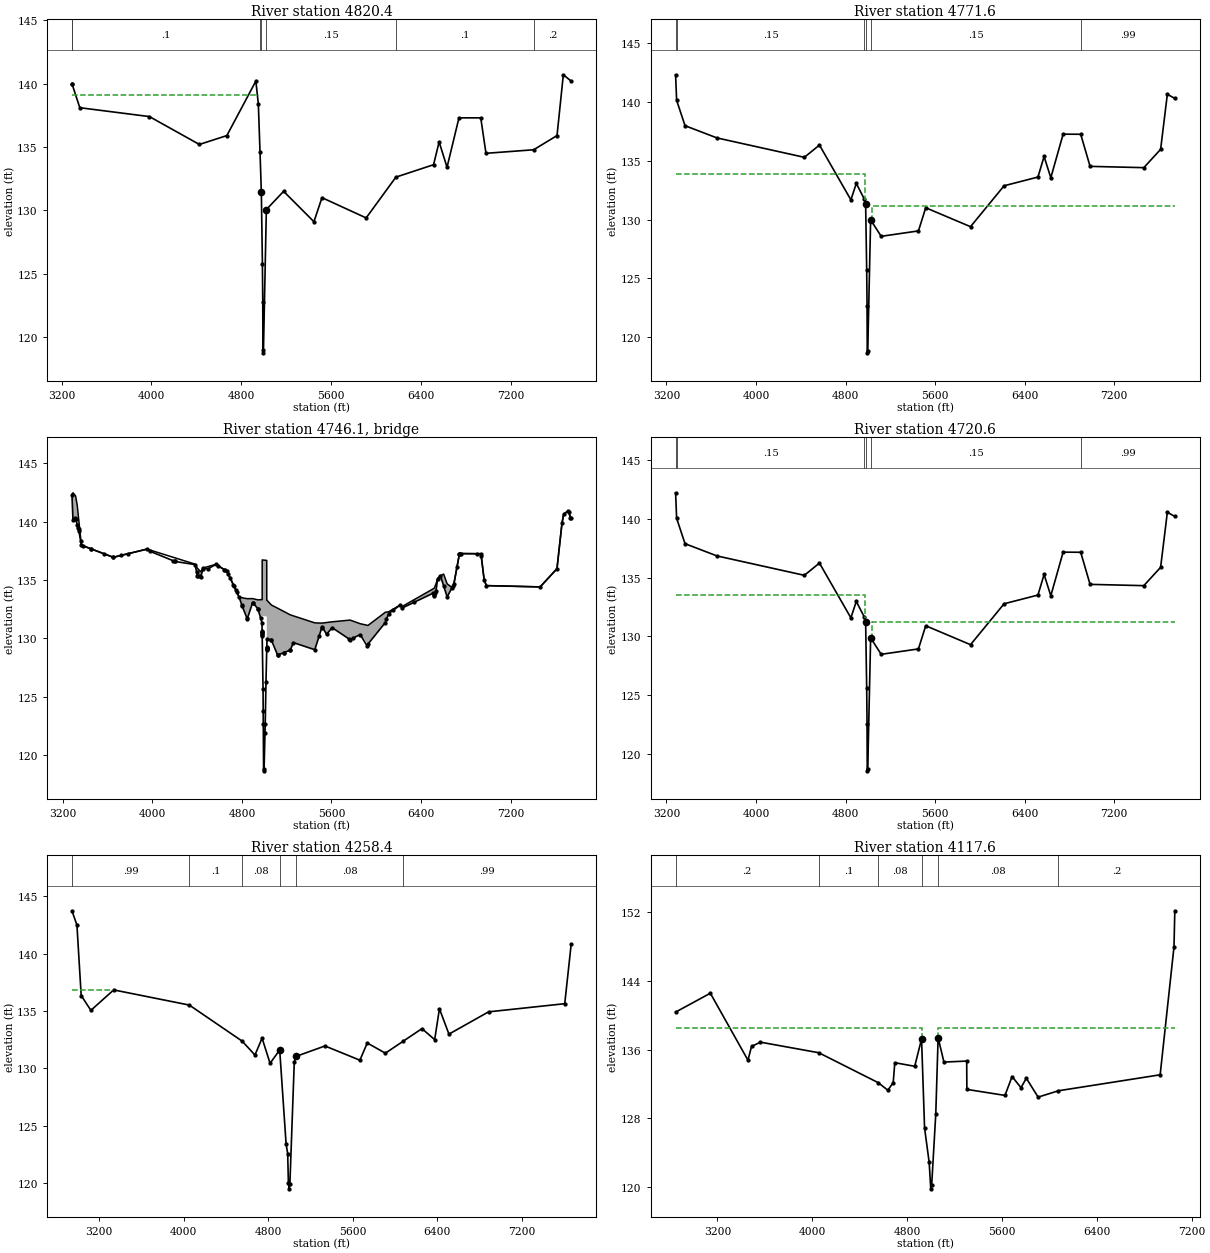
Type RM Length L Ch R = 1 ,4820.4  ,47.2,48.8,52
BEGIN DESCRIPTION:
Cross Section 4820.4-Interpolated
END DESCRIPTION:
XS GIS Cut Line= 6
      2977082.91     13844569.27      2976392.47     13844578.74
      2975074.71     13844518.43       2974138.4      13844480.3
      2973523.62     13844448.15      2972638.89     13844387.37
#Sta/Elev= 30
  3291.2     140  3291.3     140  3361.3   138.1  3981.7   137.4  4426.8   135.2
  4671.8   135.9  4930.3   140.2  4952.4   138.4  4967.3  134.62 4979.15  131.44
 4988.65  125.78 4991.85  122.73 4993.65  118.75 4998.05  118.94 5023.85  130.06
  5177.6   131.5  5447.9   129.1  5519.5     131  5913.3   129.4  6178.3  132.62
  6513.9   133.6  6563.6   135.4  6634.1   133.4  6740.4   137.3  6934.6   137.3
  6981.2   134.5  7405.9  134.78  7614.3   135.9  7670.5   140.7  7740.4   140.2
#Mann= 7 , 1 , 0
  3291.2      .2       0  3291.3      .1       0  4967.3     .15       0
 4979.15     .04       0 5023.85     .15       0  6178.3      .1       0
  7405.9      .2       0
#XS Ineff= 2 , 0
       0  4945.1   139.1  6934.6       0   137.3
Permanent Ineff=
       F       F
Bank Sta=4979.15,5023.85
Exp/Cntr=0.5,0.3

Type RM Length L Ch R = 1 ,4771.6  ,51,51,51
BEGIN DESCRIPTION:
Upstream Section of Bridge/Culvert/Weir
END DESCRIPTION:
XS GIS Cut Line= 6
      2977105.85     13844531.89      2975179.14     13844488.09
      2974637.69     13844458.43      2974054.72     13844427.92
      2973861.52     13844424.54      2972652.53     13844338.49
#Sta/Elev= 30
    3282  142.32  3291.3  140.15  3366.3  137.99  3651.3  136.95  4431.8   135.3
  4566.8  136.34  4847.7  131.68  4895.8  133.08  4967.3  131.75  4979.2  131.36
  4988.7   125.7  4991.9  122.65  4993.7  118.67  4998.1  118.86  5023.9  129.98
  5118.2  128.58  5450.9  129.04  5515.9  131.01  5915.9   129.4  6215.9  132.88
    6518  133.62    6573  135.37    6633  133.56    6743  137.27    6900  137.26
  6983.7  134.53  7463.7  134.42  7613.7  135.98  7673.7  140.66  7740.5  140.31
#Mann= 6 , 1 , 0
    3282      .2       0  3291.3     .15       0  4967.3     .15       0
  4979.2     .04       0  5023.9     .15       0    6900     .99       0
#XS Ineff= 2 , 0
       0    4970   133.9    5032       0   131.2
Permanent Ineff=
       F       F
Bank Sta=4979.2,5023.9
Exp/Cntr=0.5,0.3

Type RM Length L Ch R = 3 ,4746.1  ,,,
BEGIN DESCRIPTION:
STOCKDICK ROAD
Structure ID: T00-4
END DESCRIPTION:
Bridge Culvert--1,0,-1,-1, 0
Deck Dist Width WeirC Skew NumUp NumDn MinLoCord MaxHiCord MaxSubmerge Is_Ogee
10,31,2.6,0, 60, 60, , , 0.95, 0, 1,1,,
    3282  3291.3  3314.2  3329.2  3366.3  3651.3  3951.3  4381.8  4401.8  4431.8
  4456.8  4566.8  4666.8  4775.5  4847.7  4895.8  4942.7  4979.2  4980.5  4980.6
 4980.89    4981  5021.8 5021.91 5021.99  5022.1  5023.9  5063.1  5118.2  5231.3
  5259.8  5450.9  5515.9  5555.9  5605.9  5765.9  5855.9  5925.7  6080.9  6110.9
  6215.9  6230.9    6518    6533    6548    6573  6601.5    6633  6676.7    6693
    6743  6933.7  6963.7  6983.7  7463.7  7613.7  7658.7  7673.7  7713.7  7740.5
   142.3  142.46   142.2   141.4  137.98  136.94  137.64  136.35  136.01   135.7
  136.03  136.33  135.75  133.52  133.39   133.4  133.29  133.31  133.31  133.31
  133.31  136.71  136.67  133.27  133.27  133.27  133.25  132.85  132.58  132.01
  131.92  131.32   131.3  131.35  131.41  131.56  131.25   131.1  132.23  132.27
  132.87  132.72  134.29  134.66  135.11  135.36   135.5  134.66  134.35  134.65
  137.26  137.24  134.98  134.51   134.4  135.96  139.87  140.64   140.9  140.29
   142.3  140.13   140.2  139.72  137.97  136.93  137.63  136.31  135.37  135.28
  136.02  136.32  135.74  133.51  131.66  133.06  132.53  131.34  130.57  131.91
  131.91  131.91  131.87  131.87  131.87  129.21  129.96  129.84  128.56  128.98
  129.63  129.02  130.99  130.34  130.91  129.88  130.32   129.5  131.35  132.12
  132.86  132.59   133.6  134.03   135.1  135.35  134.49  133.54  134.34  134.64
  137.25  137.24  134.98  134.51   134.4  135.96  139.87  140.64   140.9  140.29
    3282  3291.3  3314.2  3329.2  3366.3  3651.3  3951.3  4381.8  4401.8  4431.8
  4456.8  4566.8  4666.8  4775.5  4847.7  4895.8  4942.7  4979.2  4980.5  4980.6
 4980.89    4981  5021.8 5021.91 5021.99  5022.1  5023.9  5063.1  5118.2  5231.3
  5259.8  5450.9  5515.9  5555.9  5605.9  5765.9  5855.9  5925.7  6080.9  6110.9
  6215.9  6230.9    6518    6533    6548    6573  6601.5    6633  6676.7    6693
    6743  6933.7  6963.7  6983.7  7463.7  7613.7  7658.7  7673.7  7713.7  7740.5
   142.3  142.46   142.2   141.4  137.98  136.94  137.64  136.35  136.01   135.7
  136.03  136.33  135.75  133.52  133.39   133.4  133.29  133.31  133.31  133.31
  133.31  136.71  136.67  133.27  133.27  133.27  133.25  132.85  132.58  132.01
  131.92  131.32   131.3  131.35  131.41  131.56  131.25   131.1  132.23  132.27
  132.87  132.72  134.29  134.66  135.11  135.36   135.5  134.66  134.35  134.65
  137.26  137.24  134.98  134.51   134.4  135.96  139.87  140.64   140.9  140.29
   142.2  140.03   140.1  139.62  137.87  136.83  137.53  136.21  135.27  135.18
  135.92  136.22  135.64  133.41  131.56  132.96  132.43  131.24  130.47  131.81
  131.81  131.81  131.77  131.77  131.77  129.11  129.86  129.74  128.46  128.88
  129.53  128.92  130.89  130.24  130.81  129.78  130.22   129.4  131.25  132.02
  132.76  132.49   133.5  133.93     135  135.25  134.39  133.44  134.24  134.54
  137.15  137.14  134.88  134.41   134.3  135.86  139.77  140.54   140.8  140.19
BR Coef= 1 , 1 , 0 ,1.25, 0 ,,,0.8,0,2,0,
WSPro=,,,, 1 ,,,, 0 ,,,, 0 ,,,,-1 ,-1 ,-1 , 0 , 0 , 0 , 0 , 0
BR U #Sta/Elev= 136
    3282   142.3  3291.3  140.13  3299.2  140.19  3311.3  140.29  3314.2   140.2
  3329.2  139.72    3337  139.48  3341.3  139.34  3344.2  139.18  3359.2  138.36
  3366.3  137.97  3383.1  137.91  3449.2  137.67  3453.7  137.65  3567.4  137.24
  3644.4  136.96  3651.3  136.93    3721  137.09  3779.3  137.23  3951.3  137.63
  3981.8  137.44  4184.4  136.65  4199.4  136.59  4201.8  136.58  4381.8  136.31
  4394.5  135.71  4401.8  135.37  4409.5  135.35  4424.5   135.3  4431.8  135.28
  4454.5  135.95  4456.8  136.02  4496.8  135.95  4566.8  136.32  4589.5  136.19
  4641.5  135.89  4649.5  135.84  4666.8  135.74  4679.6  135.48  4694.6  135.17
  4724.6  134.55  4729.5  134.45  4744.2  134.15  4754.6  133.94  4775.5  133.51
  4799.7  132.83  4800.7   132.8  4847.7  131.66  4849.8  131.72  4895.4  133.05
  4895.8  133.06  4942.7  132.53  4943.5   132.5  4967.3  131.73  4979.2  131.34
 4980.41  130.62  4980.5  130.57  4980.6  130.51  4980.7  130.45 4980.89  130.33
    4981  130.27 4981.11   130.2  4988.7  125.68  4990.3  123.74  4991.9  122.63
  4993.7  118.65  4998.1  118.84  5006.3  121.92  5008.2   122.7  5014.9  126.23
 5021.59     129  5021.7  129.05  5021.8  129.09 5021.91  129.14 5021.99  129.17
  5022.1  129.21  5022.2  129.26  5023.9  129.96  5062.9  129.84  5063.1  129.84
  5118.2  128.56    5119  128.56  5173.7  128.77  5173.8  128.77  5231.2  128.98
  5231.3  128.98  5259.8  129.63  5450.9  129.02  5490.1  130.21    5512  130.87
  5515.9  130.99  5555.9  130.34  5605.9  130.91  5760.5  129.91  5765.9  129.88
  5790.5     130  5855.9  130.32  5915.9  129.38  5925.7   129.5  6080.9  131.35
    6091  131.61  6110.9  132.12    6151   132.4  6215.9  132.86  6230.9  132.59
  6335.2  133.07    6503  133.84  6511.3  133.71    6518   133.6  6528.5   133.9
    6533  134.03    6548   135.1    6573  135.35  6601.5  134.49    6633  133.54
  6676.7  134.34  6686.6  134.52    6693  134.64  6721.8  136.14  6742.8  137.24
    6743  137.25  6751.9  137.25  6756.8  137.25    6900  137.24  6933.7  137.24
  6938.7  137.02  6963.7  134.98  6983.7  134.51  7463.7   134.4  7613.7  135.96
  7658.7  139.87  7673.7  140.64  7713.7   140.9  7718.7  140.81  7733.7   140.3
  7740.5  140.29
BR U #Mann= 6
    3282      .2  3291.3     .15  4967.3     .15  4979.2     .04  5023.9     .15
    6900     .99
BR U Banks=4979.2,5023.9
BR D #Sta/Elev= 136
    3282   142.2  3291.3  140.03  3299.2  140.09  3311.3  140.19  3314.2   140.1
  3329.2  139.62    3337  139.38  3341.3  139.24  3344.2  139.08  3359.2  138.26
  3366.3  137.87  3383.1  137.81  3449.2  137.57  3453.7  137.55  3567.4  137.14
  3644.4  136.86  3651.3  136.83    3721  136.99  3779.3  137.13  3951.3  137.53
  3981.8  137.34  4184.4  136.55  4199.4  136.49  4201.8  136.48  4381.8  136.21
  4394.5  135.61  4401.8  135.27  4409.5  135.25  4424.5   135.2  4431.8  135.18
  4454.5  135.85  4456.8  135.92  4496.8  135.85  4566.8  136.22  4589.5  136.09
  4641.5  135.79  4649.5  135.74  4666.8  135.64  4679.6  135.38  4694.6  135.07
  4724.6  134.45  4729.5  134.35  4744.2  134.05  4754.6  133.84  4775.5  133.41
  4799.7  132.73  4800.7   132.7  4847.7  131.56  4849.8  131.62  4895.4  132.95
  4895.8  132.96  4942.7  132.43  4943.5   132.4  4967.3  131.63  4979.2  131.24
 4980.41  130.52  4980.5  130.47  4980.6  130.41  4980.7  130.35 4980.89  130.23
    4981  130.17 4981.11   130.1  4988.7  125.58  4990.3  123.64  4991.9  122.53
  4993.7  118.55  4998.1  118.74  5006.3  121.82  5008.2   122.6  5014.9  126.13
 5021.59   128.9  5021.7  128.95  5021.8  128.99 5021.91  129.04 5021.99  129.07
  5022.1  129.11  5022.2  129.16  5023.9  129.86  5062.9  129.74  5063.1  129.74
  5118.2  128.46    5119  128.46  5173.7  128.67  5173.8  128.67  5231.2  128.88
  5231.3  128.88  5259.8  129.53  5450.9  128.92  5490.1  130.11    5512  130.77
  5515.9  130.89  5555.9  130.24  5605.9  130.81  5760.5  129.81  5765.9  129.78
  5790.5   129.9  5855.9  130.22  5915.9  129.28  5925.7   129.4  6080.9  131.25
    6091  131.51  6110.9  132.02    6151   132.3  6215.9  132.76  6230.9  132.49
  6335.2  132.97    6503  133.74  6511.3  133.61    6518   133.5  6528.5   133.8
    6533  133.93    6548     135    6573  135.25  6601.5  134.39    6633  133.44
  6676.7  134.24  6686.6  134.42    6693  134.54  6721.8  136.04  6742.8  137.14
    6743  137.15  6751.9  137.15  6756.8  137.15    6900  137.14  6933.7  137.14
  6938.7  136.92  6963.7  134.88  6983.7  134.41  7463.7   134.3  7613.7  135.86
  7658.7  139.77  7673.7  140.54  7713.7   140.8  7718.7  140.71  7733.7   140.2
  7740.5  140.19
BR D #Mann= 6
    3282      .2  3291.3     .15  4967.3     .15  4979.2     .04  5023.9     .15
    6900     .99
BR D Banks=4979.2,5023.9
BC Design=,, 0 ,, 0 ,,,,,,
BC HTab HWMax=142.32

Type RM Length L Ch R = 1 ,4720.6  ,462.2,462.2,462.2
BEGIN DESCRIPTION:
Downstream Section of Bridge/Culvert/Weir
END DESCRIPTION:
XS GIS Cut Line= 6
      2977104.11     13844480.91       2975177.4     13844437.11
      2974635.95     13844407.45      2974052.98     13844376.94
      2973859.78     13844373.56      2972650.78     13844287.52
#Sta/Elev= 30
    3282  142.22  3291.3  140.05  3366.3  137.89  3651.3  136.85  4431.8   135.2
  4566.8  136.24  4847.7  131.58  4895.8  132.98  4967.3  131.65  4979.2  131.26
  4988.7   125.6  4991.9  122.55  4993.7  118.57  4998.1  118.76  5023.9  129.88
  5118.2  128.48  5450.9  128.94  5515.9  130.91  5915.9   129.3  6215.9  132.78
    6518  133.52    6573  135.27    6633  133.46    6743  137.17    6900  137.16
  6983.7  134.43  7463.7  134.32  7613.7  135.88  7673.7  140.56  7740.5  140.21
#Mann= 6 , 1 , 0
    3282      .2       0  3291.3     .15       0  4967.3     .15       0
  4979.2     .04       0  5023.9     .15       0    6900     .99       0
#XS Ineff= 2 , 0
       0    4970   133.5    5032       0   131.2
Permanent Ineff=
       F       F
Bank Sta=4979.2,5023.9
Exp/Cntr=0.5,0.3

Type RM Length L Ch R = 1 ,4258.4  ,59.1,140.8,163.1
BEGIN DESCRIPTION:
Cross Section 4258.4-Interpolated
END DESCRIPTION:
XS GIS Cut Line= 6
      2977110.46     13844453.71      2976458.92     13844272.72
      2975142.86     13844075.64      2975047.17     13844142.88
      2973764.73     13844258.98      2972451.34     13844219.27
#Sta/Elev= 30
    2944  143.72  2991.2  142.48  3031.6  136.34  3123.3  135.05  3339.3  136.83
  4055.1  135.51  4555.3  132.37  4676.4  131.16  4743.8  132.63  4819.6  130.44
  4910.6   131.6  4971.2  123.41  4986.1  122.58  4992.9  120.04  4999.3  119.51
    5007  119.92  5048.6  130.56    5068  131.05    5339  131.95  5669.8  130.71
  5739.6  132.21  5910.8  131.32  6075.8  132.34  6257.2  133.46  6377.6   132.5
  6422.6  135.19  6512.6  132.98  6887.8  134.92  7608.7  135.63  7669.6   140.8
#Mann= 6 , 1 , 0
    2944     .99       0  4055.1      .1       0  4555.3     .08       0
  4910.6     .04       0    5068     .08       0  6075.8     .99       0
#XS Ineff= 2 , 0
       0  3325.6  136.82  6422.6       0  135.19
Permanent Ineff=
       F       F
Bank Sta=4910.6,5068
Exp/Cntr=0.5,0.3

Type RM Length L Ch R = 1 ,4117.6  ,285,285,285
BEGIN DESCRIPTION:
Upstream Section of Bridge/Culvert/Weir
END DESCRIPTION:
XS GIS Cut Line= 5
      2977152.33     13844077.22      2975662.83     13844026.46
      2975178.14     13844014.92      2974684.79     13843988.95
      2972944.79     13843936.84
#Sta/Elev= 30
  2847.5  140.38  3140.5  142.58  3457.8  134.78  3487.8  136.38  3562.8  136.88
  4055.1  135.65  4555.3  132.17  4637.8  131.28  4682.8  132.18  4696.1  134.49
    4864  134.07  4921.8  137.25  4947.1  126.89  4986.1  122.87  4999.3   119.8
    5007  120.21  5041.7  128.54  5061.4   137.4  5110.4  134.56  5302.5  134.68
  5303.8  131.38  5625.2  130.68  5685.2  132.88  5760.2  131.58  5805.2  132.68
  5904.8  130.48  6075.8  131.22  6933.9  133.08  7050.5  147.98  7057.5  152.18
#Mann= 6 , 1 , 0
  2847.5      .2       0  4055.1      .1       0  4555.3     .08       0
  4921.8     .04       0  5061.4     .08       0  6075.8      .2       0
#XS Ineff= 2 , 0
       0  4921.8   138.5  5061.4       0   138.5
Permanent Ineff=
       F       F
Bank Sta=4921.8,5061.4
Exp/Cntr=0.5,0.3

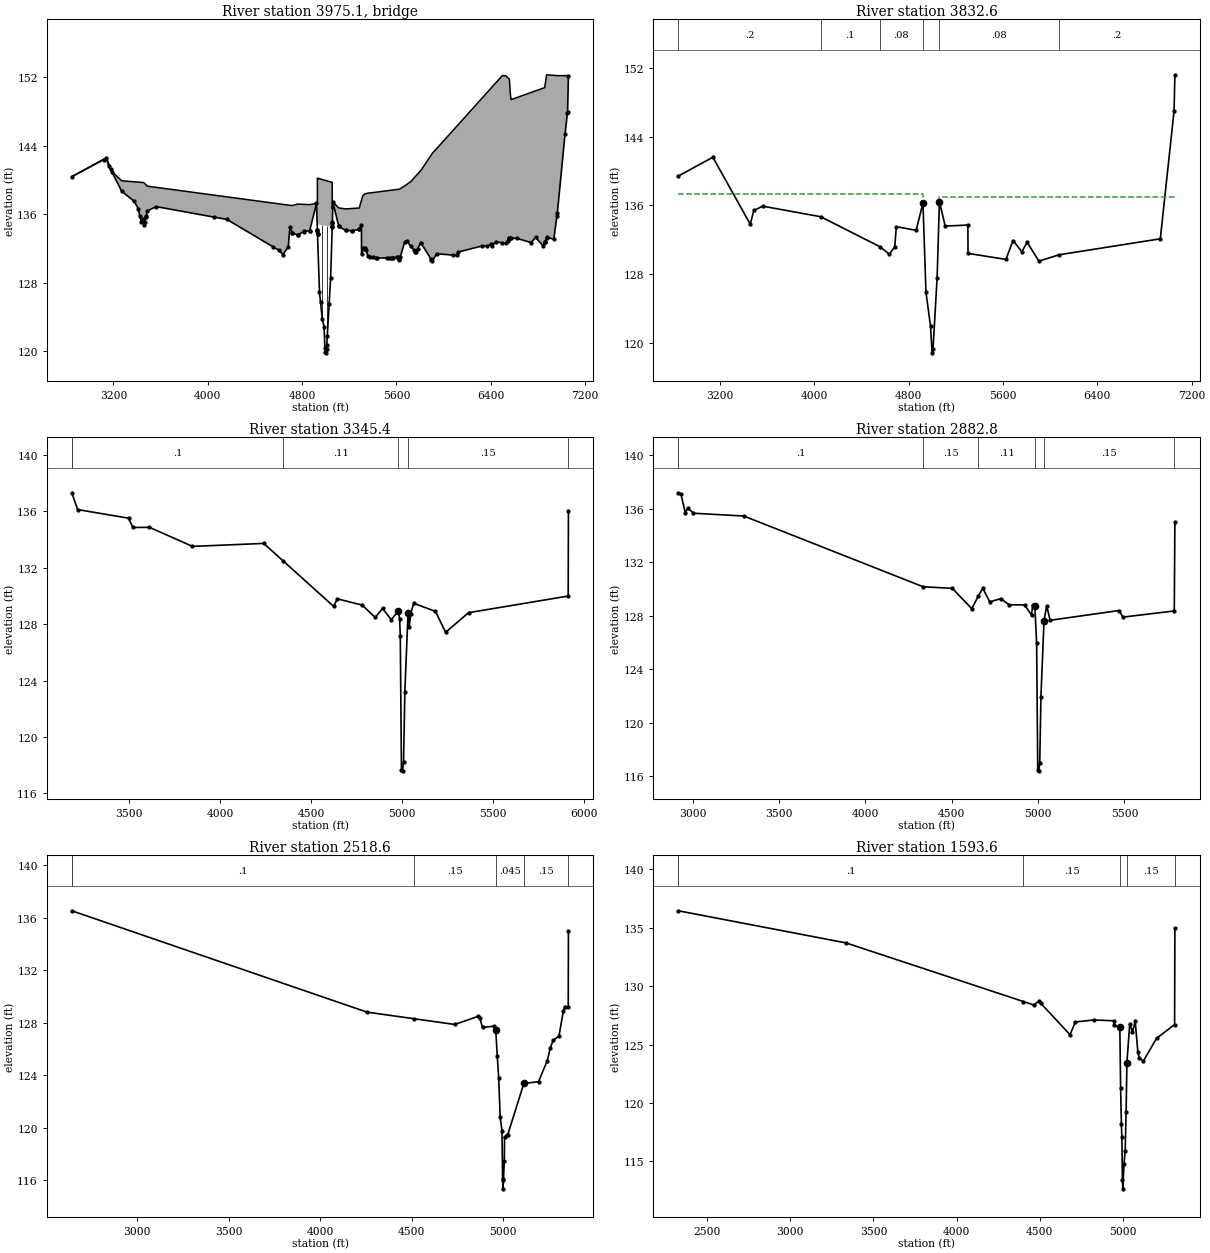
Type RM Length L Ch R = 3 ,3975.1  ,,,
BEGIN DESCRIPTION:
I-10
Structure ID: T00-3
END DESCRIPTION:
Bridge Culvert--1,0,-1,-1, 0
Deck Dist Width WeirC Skew NumUp NumDn MinLoCord MaxHiCord MaxSubmerge Is_Ogee
10,265,2.6,0, 60, 60, , , 0.95, 0, 1,1,,
  2847.5  3140.5  3185.5  3270.5  3377.8  3412.8  3437.8  3447.8  3457.8  3487.8
  3562.8  4162.3  4637.8  4682.8  4696.1  4715.7  4761.7    4864  4921.8 4929.29
  4929.4 4930.51  4930.6    5055 5055.11  5061.4  5110.4  5168.2  5284.4  5302.5
  5303.8  5313.8  5333.8  5358.8  5625.2  5670.2  5721.7  5760.2  5805.2  5904.8
  5939.8  6109.8  6124.8  6409.8  6439.8  6496.9  6524.8  6556.9  6566.2  6571.9
  6739.8  6778.9  6843.9  6856.5  6872.1  6933.9  6963.9  7028.9  7050.5  7057.5
   140.4  142.61  141.01  139.92   139.8  139.76  139.73  139.72  139.71  139.29
  139.15  138.04  137.16  137.08  137.06  137.02   137.2  137.13  137.28  137.12
  140.22  140.22  140.22  139.73  136.63  137.43  136.75  136.63  136.74  137.61
  137.68  138.16   138.4  138.47  138.94  139.33  139.83  140.43  141.09  143.14
  143.67  146.27   146.5  150.87  151.33   152.2   152.2   151.8   149.9   149.4
  150.23  150.42  150.74   150.8   152.3  152.23   152.2   152.2   152.2   152.2
   140.4   142.6     141   138.7   137.5   136.6   135.1   135.5   134.8   136.4
   136.9   135.4   131.3   132.2  134.51  133.85  133.57  134.09  137.27   134.2
  134.16   133.7  134.82  134.54  134.59  137.42  134.58  134.13  134.24   134.7
   131.4     132   132.1   131.1   130.7   132.8  132.27   131.6   132.7   130.5
   131.4   131.2   131.6   132.3   132.8  132.67   132.6   133.2   133.2   133.2
   132.7   133.3   132.3  132.72  133.24   133.1   136.2   145.4     148   152.2
  2847.5  3140.5  3185.5  3270.5  3377.8  3412.8  3437.8  3447.8  3457.8  3487.8
  3562.8  4162.3  4637.8  4682.8  4696.1  4715.7  4761.7    4864  4921.8 4929.29
  4929.4 4930.51  4930.6    5055 5055.11  5061.4  5110.4  5168.2  5284.4  5302.5
  5303.8  5313.8  5333.8  5358.8  5625.2  5670.2  5721.7  5760.2  5805.2  5904.8
  5939.8  6109.8  6124.8  6409.8  6439.8  6496.9  6524.8  6556.9  6566.2  6571.9
  6739.8  6778.9  6843.9  6856.5  6872.1  6933.9  6963.9  7028.9  7050.5  7057.5
   140.4  142.61  141.01  139.92   139.8  139.76  139.73  139.72  139.71  139.29
  139.15  138.04  137.16  137.08  137.06  137.02   137.2  137.13  137.28  137.12
  140.22  140.22  140.22  139.73  136.63  137.43  136.75  136.63  136.74  137.61
  137.68  138.16   138.4  138.47  138.94  139.33  139.83  140.43  141.09  143.14
  143.67  146.27   146.5  150.87  151.33   152.2   152.2   151.8   149.9   149.4
  150.23  150.42  150.74   150.8   152.3  152.23   152.2   152.2   152.2   152.2
  139.45  141.65  140.05  137.75  136.55  135.65  134.15  134.55  133.85  135.45
  135.95  134.45  130.35  131.25  133.56   132.9  132.62  133.14  136.32  133.25
  133.21  132.75  133.87  133.59  133.64  136.47  133.63  133.18  133.29  133.75
  130.45  131.05  131.15  130.15  129.75  131.85  131.32  130.65  131.75  129.55
  130.45  130.25  130.65  131.35  131.85  131.72  131.65  132.25  132.25  132.25
  131.75  132.35  131.35  131.77  132.29  132.15  135.25  144.45  147.05  151.25
Pier Skew, UpSta & Num, DnSta & Num=  ,4971.2, 2 ,4971.2, 2 , 0 , 0 , 0 ,,
     1.4     1.4
  122.68  135.66
     1.4     1.4
  121.73  134.71
Pier Skew, UpSta & Num, DnSta & Num=  ,5013.3, 2 ,5013.3, 2 , 0 , 0 , 0 ,,
     1.4     1.4
  120.65  135.49
     1.4     1.4
   119.7  134.54
Abutment Skew #Up #Dn= , 2 , 2
  4930.4  4956.1
  134.82  125.72
  4930.4  4956.1
  133.87  124.77
Abutment Skew #Up #Dn= , 2 , 2
  5028.7 5056.19
  125.47  134.99
  5028.7 5056.19
  124.52  134.04
BR Coef= 1 , 1 , 0 ,1.25, 0 ,,,0.8,-1,2,0,
WSPro=,,,, 1 ,,,, 0 ,,,, 0 ,,,,-1 ,-1 ,-1 , 0 , 0 , 0 , 0 , 0
BR U #Sta/Elev= 135
  2847.5   140.4  3120.5   142.4  3140.5   142.6  3160.5   141.6  3175.5   141.3
  3185.5     141  3270.5   138.7  3377.8   137.5  3412.8   136.6  3422.8   135.8
  3437.8   135.1  3442.8   135.2  3447.8   135.5  3457.8   134.8    3465  135.12
  3477.8   135.7    3480  135.85  3487.8   136.4  3562.8   136.9  4055.1  135.67
  4162.3   135.4  4555.3  132.19  4602.8   131.8  4637.8   131.3  4682.8   132.2
  4696.1  134.51  4715.7  133.85  4716.2  133.85  4761.7  133.57  4761.8  133.57
  4812.4  133.99    4813     134  4863.4  134.09    4864  134.09  4921.8  137.27
 4929.29   134.2  4929.4  134.16 4929.51  134.11  4930.4  133.75 4930.51   133.7
  4930.6  133.67  4947.1  126.91  4956.1  125.72  4971.2  123.72  4986.1  122.89
  4992.9  120.35  4995.4  119.94  4999.3  119.82  5005.7  120.14    5007  120.23
  5008.7  120.71  5013.3  121.82  5028.7  125.47  5041.7  128.56 5054.89  134.49
    5055  134.54 5055.11  134.59 5055.99  134.99  5056.1  135.04  5056.2  135.08
  5061.4  137.42  5110.1   134.6  5110.4  134.58  5168.2  134.13  5168.4  134.13
  5222.6  134.09    5223  134.09  5283.9  134.23  5284.4  134.24  5302.5   134.7
  5303.8   131.4  5313.8     132  5316.7  132.01  5333.8   132.1  5341.7  131.78
  5358.8   131.1  5371.7  131.06  5401.7  130.98  5430.2   130.9  5431.7   130.9
  5521.7   130.9  5535.2   130.9  5551.7  130.92  5561.7  130.93  5566.7  130.94
  5606.7  130.99  5615.2     131  5621.7  130.81  5625.2   130.7  5631.7     131
  5670.2   132.8  5685.2   132.9  5721.7  132.27  5746.7  131.83  5760.2   131.6
  5761.7  131.63  5780.2     132  5805.2   132.7  5806.7  132.67  5891.7  130.79
  5895.9   130.7  5904.8   130.5  5939.8   131.4  6075.8  131.24  6109.8   131.2
  6124.8   131.6  6324.8   132.3  6369.8   132.3  6399.8   132.5  6409.8   132.3
  6439.8   132.8  6496.9  132.67  6524.8   132.6  6541.9  132.94  6551.6  133.14
  6554.8   133.2  6556.9   133.2  6566.2   133.2  6571.9   133.2  6619.8   133.2
  6739.8   132.7  6778.9   133.3  6843.9   132.3  6856.5  132.72  6857.1  132.74
  6857.6  132.76  6872.1  133.24  6873.9   133.3  6933.9   133.1  6959.9  135.79
  6963.9   136.2  7028.9   145.4  7048.9   147.8  7050.5     148  7057.5   152.2
BR U #Mann= 6
  2847.5      .2  4055.1      .1  4555.3     .08  4921.8     .04  5061.4     .08
  6075.8      .2
BR U Banks=4921.8,5061.4
BR D #Sta/Elev= 135
  2847.5  139.45  3120.5  141.45  3140.5  141.65  3160.5  140.65  3175.5  140.35
  3185.5  140.05  3270.5  137.75  3377.8  136.55  3412.8  135.65  3422.8  134.85
  3437.8  134.15  3442.8  134.25  3447.8  134.55  3457.8  133.85    3465  134.17
  3477.8  134.75    3480   134.9  3487.8  135.45  3562.8  135.95  4055.1  134.72
  4162.3  134.45  4555.3  131.24  4602.8  130.85  4637.8  130.35  4682.8  131.25
  4696.1  133.56  4715.7   132.9  4716.2   132.9  4761.7  132.62  4761.8  132.62
  4812.4  133.04    4813  133.05  4863.4  133.14    4864  133.14  4921.8  136.32
 4929.29  133.25  4929.4  133.21 4929.51  133.16  4930.4   132.8 4930.51  132.75
  4930.6  132.72  4947.1  125.96  4956.1  124.77  4971.2  122.77  4986.1  121.94
  4992.9   119.4  4995.4  118.99  4999.3  118.87  5005.7  119.19    5007  119.28
  5008.7  119.76  5013.3  120.87  5028.7  124.52  5041.7  127.61 5054.89  133.54
    5055  133.59 5055.11  133.64 5055.99  134.04  5056.1  134.09  5056.2  134.13
  5061.4  136.47  5110.1  133.65  5110.4  133.63  5168.2  133.18  5168.4  133.18
  5222.6  133.14    5223  133.14  5283.9  133.28  5284.4  133.29  5302.5  133.75
  5303.8  130.45  5313.8  131.05  5316.7  131.06  5333.8  131.15  5341.7  130.83
  5358.8  130.15  5371.7  130.11  5401.7  130.03  5430.2  129.95  5431.7  129.95
  5521.7  129.95  5535.2  129.95  5551.7  129.97  5561.7  129.98  5566.7  129.99
  5606.7  130.04  5615.2  130.05  5621.7  129.86  5625.2  129.75  5631.7  130.05
  5670.2  131.85  5685.2  131.95  5721.7  131.32  5746.7  130.88  5760.2  130.65
  5761.7  130.68  5780.2  131.05  5805.2  131.75  5806.7  131.72  5891.7  129.84
  5895.9  129.75  5904.8  129.55  5939.8  130.45  6075.8  130.29  6109.8  130.25
  6124.8  130.65  6324.8  131.35  6369.8  131.35  6399.8  131.55  6409.8  131.35
  6439.8  131.85  6496.9  131.72  6524.8  131.65  6541.9  131.99  6551.6  132.19
  6554.8  132.25  6556.9  132.25  6566.2  132.25  6571.9  132.25  6619.8  132.25
  6739.8  131.75  6778.9  132.35  6843.9  131.35  6856.5  131.77  6857.1  131.79
  6857.6  131.81  6872.1  132.29  6873.9  132.35  6933.9  132.15  6959.9  134.84
  6963.9  135.25  7028.9  144.45  7048.9  146.85  7050.5  147.05  7057.5  151.25
BR D #Mann= 6
  2847.5      .2  4055.1      .1  4555.3     .08  4921.8     .04  5061.4     .08
  6075.8      .2
BR D Banks=4921.8,5061.4
BC Design=,, 0 ,, 0 ,,,,,,
BC HTab HWMax=152.18

Type RM Length L Ch R = 1 ,3832.6  ,487.2,487.2,487.2
BEGIN DESCRIPTION:
Downstream Section of Bridge/Culvert/Weir
END DESCRIPTION:
XS GIS Cut Line= 5
      2977057.63     13843808.42      2975568.13     13843757.66
      2975083.44     13843746.12      2974590.09     13843720.15
       2972850.1     13843668.04
#Sta/Elev= 30
  2847.5  139.42  3140.5  141.62  3457.8  133.82  3487.8  135.42  3562.8  135.92
  4055.1  134.69  4555.3  131.21  4637.8  130.32  4682.8  131.22  4696.1  133.53
    4864  133.11  4921.8  136.29  4947.1  125.93  4986.1  121.91  4999.3  118.84
    5007  119.25  5041.7  127.58  5061.4  136.44  5110.4   133.6  5302.5  133.72
  5303.8  130.42  5625.2  129.72  5685.2  131.92  5760.2  130.62  5805.2  131.72
  5904.8  129.52  6075.8  130.26  6933.9  132.12  7050.5  147.02  7057.5  151.22
#Mann= 6 , 1 , 0
  2847.5      .2       0  4055.1      .1       0  4555.3     .08       0
  4921.8     .04       0  5061.4     .08       0  6075.8      .2       0
#XS Ineff= 2 , 0
       0  4921.8   137.3  5061.4       0     137
Permanent Ineff=
       F       F
Bank Sta=4921.8,5061.4
Exp/Cntr=0.5,0.3

Type RM Length L Ch R = 1 ,3345.4  ,434.9,462.6,366.3
BEGIN DESCRIPTION:
Cross Section 3345.4-Interpolated
END DESCRIPTION:
XS GIS Cut Line= 6
      2976659.81     13843452.32      2976018.27     13843283.84
      2975239.24     13843228.57      2974868.52     13843247.16
      2974504.65     13843286.28      2973961.73     13843369.69
#Sta/Elev= 30
  3185.2  137.31  3217.2  136.12  3497.2  135.51  3521.2  134.85  3612.4  134.86
  3848.8  133.51  4240.8  133.72  4348.3  132.47  4624.8  129.26  4645.8  129.79
  4781.8  129.35  4853.8  128.47  4893.8  129.11  4941.8  128.32  4981.2  128.93
  4988.1  128.34  4991.5  127.15    4998  117.68    5004   117.6  5009.6  118.22
  5016.5  123.16  5034.3  128.82    5041  127.82    5049  128.74    5065  129.48
    5185   128.9    5241  127.42  5366.9  128.81  5914.9  129.99  5916.2     136
#Mann= 6 , 1 , 0
  3185.2      .2       0  3185.2      .1       0  4348.3     .11       0
  4981.2     .04       0  5034.3     .15       0  5914.9      .2       0
Bank Sta=4981.2,5034.3
Exp/Cntr=0.3,0.1

Type RM Length L Ch R = 1 ,2882.8  ,344.1,364.2,442.3
BEGIN DESCRIPTION:
Cross Section 2882.8
END DESCRIPTION:
XS GIS Cut Line= 6
      2976818.58      13843281.2      2976506.34     13843065.09
       2975323.8     13842822.61       2974907.4     13842785.51
      2974721.88     13842789.63      2974038.55      13842830.5
#Sta/Elev= 30
    2917  137.21    2933   137.1    2957  135.73    2973  136.06    3005  135.68
  3296.7  135.47  4334.5  130.18  4503.9  130.06  4615.9  128.54  4654.3  129.49
  4679.9  130.07  4719.9  129.05  4783.9  129.29  4831.9  128.83  4921.9  128.82
  4961.9  128.06  4968.9  128.83  4981.2  128.74  4991.5  125.96    4998  116.49
    5004  116.41  5009.6  117.03  5016.5  121.97  5034.3  127.63    5050  128.77
  5069.3  127.67  5467.5   128.4  5491.5  127.91  5788.4  128.37    5792     135
#Mann= 7 , 1 , 0
    2917      .2       0    2917      .1       0  4334.5     .15       0
  4654.3     .11       0  4981.2    .045       0  5034.3     .15       0
  5788.4      .2       0
Bank Sta=4981.2,5034.3
Exp/Cntr=0.3,0.1

Type RM Length L Ch R = 1 ,2518.6  ,672.6,925,704.7
BEGIN DESCRIPTION:
Cross Section 2518.6-Interpolated
END DESCRIPTION:
XS GIS Cut Line= 5
      2977023.66     13843129.03      2975541.27     13842491.53
      2974815.12     13842435.68      2974774.17     13842441.98
      2974442.55     13842447.88
#Sta/Elev= 30
  2641.8  136.53  4255.5  128.81  4511.4  128.31  4735.5  127.87  4863.5  128.49
  4871.5  128.35  4887.5  127.65  4951.5  127.74  4959.5  127.45  4967.5   125.5
  4975.5  123.83  4983.7  120.79  4993.6  119.78  4996.8  116.11  4999.2  115.35
  5001.5     116  5006.3  117.45  5007.7  119.31  5023.7  119.42  5025.2  119.48
  5113.2  123.38  5193.2  123.51  5241.2  125.11  5257.2  126.06  5273.2  126.66
  5305.2  126.99  5329.2  128.91  5337.2  129.23  5355.8  129.21  5356.8     135
#Mann= 6 , 1 , 0
  2641.8      .2       0  2641.8      .1       0  4511.4     .15       0
  4959.5    .045       0  5113.2     .15       0  5355.8      .2       0
Bank Sta=4959.5,5113.2
Exp/Cntr=0.3,0.1

Type RM Length L Ch R = 1 ,1593.6  ,1056.9,1144.2,484.2
BEGIN DESCRIPTION:
Cross Section 1593.6
END DESCRIPTION:
XS GIS Cut Line= 5
      2977317.31     13843068.85      2975480.47     13841973.32
      2975055.82     13841754.81      2974968.12     13841658.62
      2974770.35     13841525.22
#Sta/Elev= 30
  2327.3  136.46  3335.3  133.71  4401.5  128.69  4463.3   128.4    4498  128.75
    4506  128.54    4682  125.85    4714  126.94    4826  127.11  4943.6  127.04
  4948.5  126.64  4981.4  126.49    4986   121.3  4990.6  118.19  4993.6  117.08
  4996.8  113.41  4999.2  112.65  5006.3  114.75  5013.4  115.92  5019.2  119.24
  5023.8  123.46    5041  126.79  5057.4  126.09  5073.8  126.99  5089.8  124.35
  5097.8  123.89  5121.8  123.57  5201.8  125.53  5310.5  126.72  5312.3     135
#Mann= 6 , 1 , 0
  2327.3      .2       0  2327.3      .1       0  4401.5     .15       0
  4981.4     .05       0  5023.8     .15       0  5310.5      .2       0
Bank Sta=4981.4,5023.8
Exp/Cntr=0.3,0.1

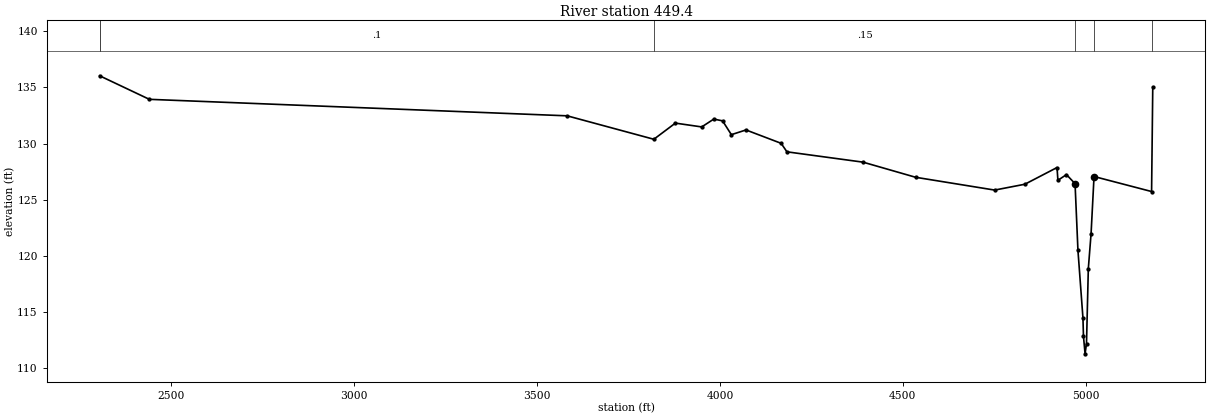
Type RM Length L Ch R = 1 ,449.4   ,0,0,0
BEGIN DESCRIPTION:
Cross Section 449.4
END DESCRIPTION:
XS GIS Cut Line= 6
       2977632.2     13842290.44      2976796.09     13841323.17
      2976416.34     13841194.11      2975628.89     13840872.53
      2975426.87     13840777.71      2975308.03     13840733.88
#Sta/Elev= 30
  2303.5  136.04  2439.5  133.94    3582  132.47  3819.1  130.38    3878  131.82
    3950  131.48  3983.1  132.18  4007.1  132.02  4031.1  130.79  4071.1  131.21
  4167.1  130.02  4183.1  129.26  4391.1  128.34  4535.1  126.99  4751.1  125.85
  4833.7  126.37  4921.7  127.86  4924.1  126.72  4947.5  127.23    4971  126.42
  4978.9  120.48  4992.6  114.44    4994  112.82  4998.4  111.25  5002.3  112.16
  5007.3  118.85  5014.8  121.96  5022.9  127.06  5180.3  125.72  5183.5     135
#Mann= 6 , 1 , 0
  2303.5      .2       0  2303.5      .1       0  3819.1     .15       0
    4971     .05       0  5022.9     .15       0  5180.3      .2       0
#XS Ineff= 2 , 0
       0  3983.1  132.18               0
Permanent Ineff=
       F       F
Bank Sta=4971,5022.9
Exp/Cntr=0.3,0.1

Chan Stop Cuts=-1
Use User Specified Reach Order=0
User Specified Reach Order=T100-00-00      ,T100-00-00_0004